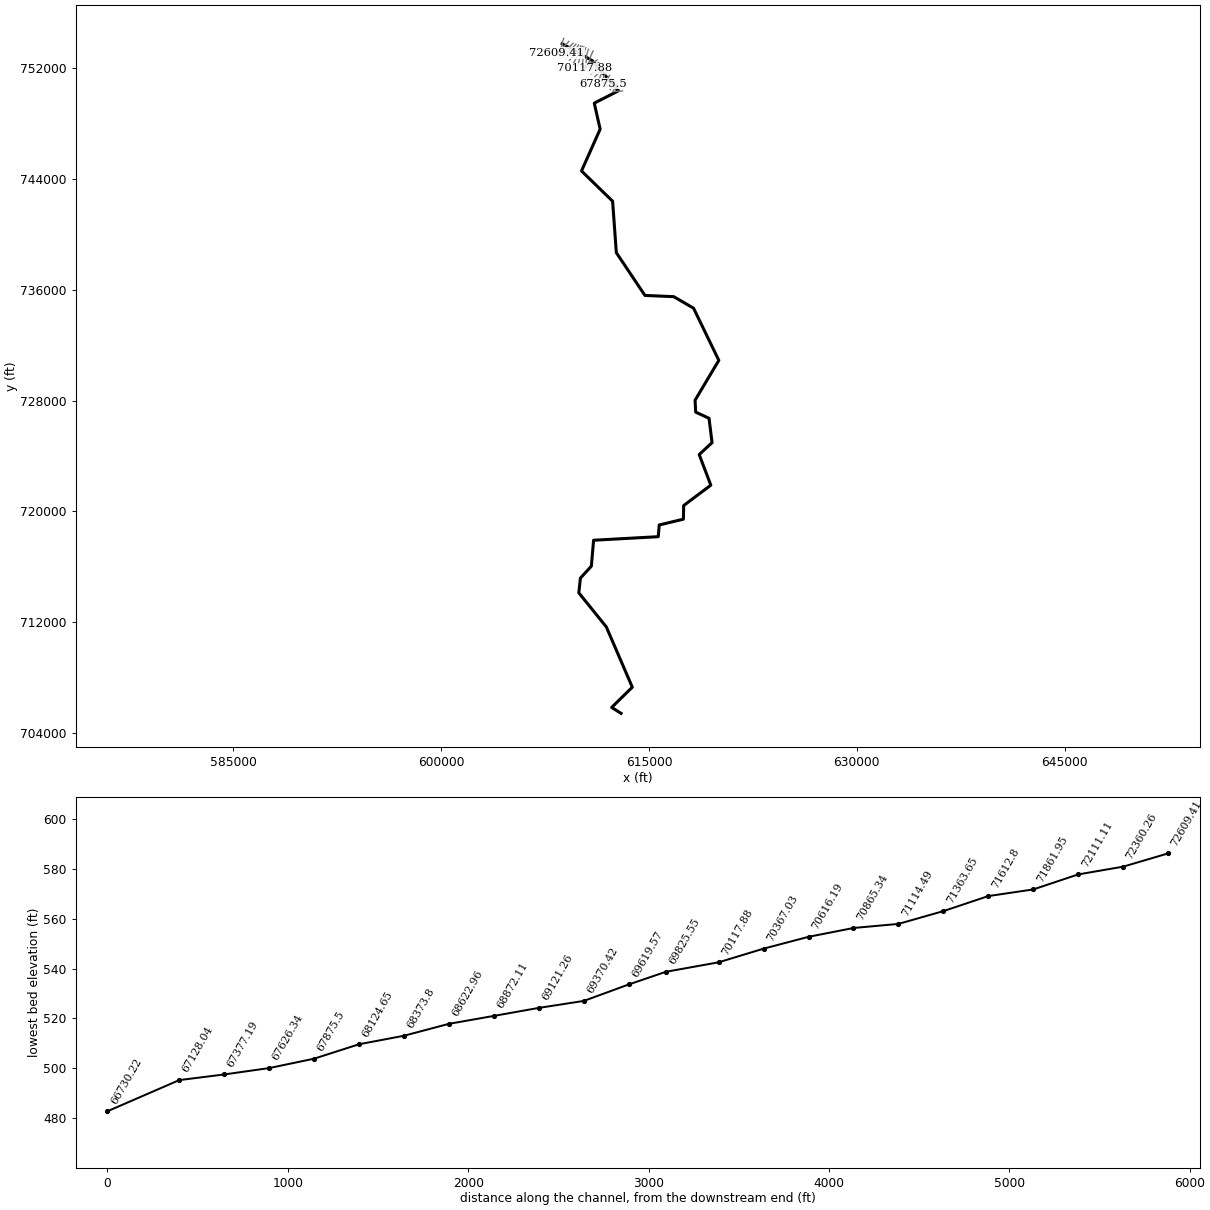
--- 3120_ras.prj (project) ---

Proj Title=3120
Current Plan=p01
Default Exp/Contr=0.3,0.1
English Units
Geom File=g01
Flow File=f01
Plan File=p01
Y Axis Title=Elevation
X Axis Title(PF)=Main Channel Distance
X Axis Title(XS)=Station
BEGIN DESCRIPTION:
RFD model 3120 exported to HEC-RAS
END DESCRIPTION:

--- 3120_ras.p01 (plan) ---

Plan Title=Plan 01
Program Version=4.10
Short Identifier=Plan 01
Geom File=g01
Flow File=f01
Subcritical Flow
Calc Critical at every XS
Secant Critical Depth

--- 3120_ras.f01 (steady flow) ---

Flow Title=Flow 01
Program Version=5.01
Number of Profiles= 6
Profile Names=10yr,25yr,50yr,100yr,100plus,500yr
River Rch & RM=3120,126,72609.41
 5074.08 8286.0711369.97 14198.320729.5222533.36
River Rch & RM=3120,126,72360.26
 5078.57 8294.3211382.1314214.4220753.0622558.63
River Rch & RM=3120,126,72111.11
 5082.37 8301.3311392.4614228.1420773.0822580.18
River Rch & RM=3120,126,71861.95
 5085.26 8306.6411400.3114238.5520788.2822596.52
River Rch & RM=3120,126, 71612.8
 5097.34 8329.0511433.48 14282.720852.7422666.29
River Rch & RM=3120,126,71363.65
  5105.2 8343.6211455.0314311.37 20894.622711.52
River Rch & RM=3120,126,71114.49
 5243.18 8588.0911807.99 14771.621566.5323404.84
River Rch & RM=3120,126,70865.34
  5245.9  8593.111815.3814781.4221580.8723420.22
River Rch & RM=3120,126,70616.19
 5247.46 8595.9711819.6214787.0421589.0823429.01
River Rch & RM=3120,126,70367.03
 5277.68 8651.7111901.9214896.37 21748.7 23600.1
River Rch & RM=3120,126,70117.88
 5502.75 9045.5212466.5315628.29 22817.324680.51
River Rch & RM=3120,126,69825.55
  5504.2 9048.1712470.4215633.43 22824.8 24688.4
River Rch & RM=3120,126,69619.57
 5506.97 9053.2112477.8215643.22 22839.124703.46
River Rch & RM=3120,126,69370.42
  5516.5 9070.6412503.4415677.1422888.6324755.79
River Rch & RM=3120,126,69121.26
  5517.4 9072.2912505.8815680.3822893.36 24760.8
River Rch & RM=3120,126,68872.11
 5524.68  9085.712525.6815706.6722931.7524801.63
River Rch & RM=3120,126,68622.96
 5526.97 9089.9312531.9215714.9722943.8624814.52
River Rch & RM=3120,126, 68373.8
 5637.73 9288.0112819.5916091.99 23494.3 25381.8
River Rch & RM=3120,126,68124.65
 5640.89 9293.7512828.0116103.1223510.5625398.83
River Rch & RM=3120,126, 67875.5
 5659.73 9327.7712877.6816168.5323606.0525498.06
River Rch & RM=3120,126,67626.34
 5661.45 9330.8912882.2616174.5623614.8725507.27
River Rch & RM=3120,126,67377.19
 5665.54 9338.3212893.1416188.9423635.8525529.21
River Rch & RM=3120,126,67128.04
 5733.57 9460.5213071.09 16422.723977.1425881.51
River Rch & RM=3120,126,66730.22
 5741.05 9474.1213091.0216449.0324015.5825921.63
River Rch & RM=3120,126,66380.58
 5762.25 9512.9113148.0916524.66   2412626037.64
River Rch & RM=3120,126,66131.42
 5766.78 9521.2513160.4216541.0324149.9126062.92
River Rch & RM=3120,126,65882.27
 5769.41  9526.113167.5916550.5724163.8426077.66
River Rch & RM=3120,126,65633.12
  5783.7 9552.4613206.5316602.3624239.4426157.65
River Rch & RM=3120,126,65383.96
 5785.58 9555.9213211.6516609.1724249.3826168.17
River Rch & RM=3120,126,65134.81
 5788.83 9561.9213220.5116620.96 24266.626186.39
River Rch & RM=3120,126,64885.66
 5794.08 9571.6813235.0116640.3124294.8626216.52
River Rch & RM=3120,126, 64636.5
 5820.61  9620.913308.0116737.6624436.9826367.67
River Rch & RM=3120,126,64387.35
 5830.17  9638.813334.6816773.3724489.1226423.57
River Rch & RM=3120,126, 64138.2
 5833.55 9645.1113344.0616785.9124507.4326443.12
River Rch & RM=3120,126,63889.04
 5839.17  9655.7 13359.916807.1924538.4926476.63
River Rch & RM=3120,126,63639.89
 5841.55 9660.2513366.7416816.4124551.9626491.28
River Rch & RM=3120,126,63390.74
 5848.72  9673.913387.2616844.0824592.3626535.22
River Rch & RM=3120,126,63141.58
 5853.32 9682.6213400.3516861.7124618.09 26563.1
River Rch & RM=3120,126,62892.43
 5859.67 9694.6413418.3816885.96 24653.526601.42
River Rch & RM=3120,126,62643.28
 5902.56 9775.1413538.5217047.0424888.6826853.81
River Rch & RM=3120,126,62394.12
 5912.45 9794.2513567.4917086.3524946.0726916.93
River Rch & RM=3120,126,62144.97
 5914.73 9798.6713574.1717095.4224959.3126931.49
River Rch & RM=3120,126,61895.82
  5989.1 9938.7413783.6717376.7725370.0927373.03
River Rch & RM=3120,126,61646.66
 5995.83  9951.8 13803.517403.7425409.4627416.41
River Rch & RM=3120,126,61397.51
 5997.64 9955.3213808.8417411.0225420.0827428.11
River Rch & RM=3120,126,61148.36
 5999.78 9959.4613815.1417419.5725432.5827441.87
River Rch & RM=3120,126, 60899.2
 6031.2210019.72 13906.117542.6525612.2827637.71
River Rch & RM=3120,126,60650.05
 6033.6210024.4113913.2517552.4125626.5227653.49
River Rch & RM=3120,126, 60400.9
 6046.0710048.4213949.6117601.7325698.5327732.34
River Rch & RM=3120,126,60151.74
 6051.4710058.9113965.5617623.4625730.2427767.28
River Rch & RM=3120,126,59902.59
 6057.5710070.8613983.8217648.3925766.6527807.68
River Rch & RM=3120,126,59653.44
 6083.1810120.4614059.1117750.7325916.0727971.78
River Rch & RM=3120,126,59155.13
 6090.2810134.3914080.3917779.8125958.5228018.89
River Rch & RM=3120,126,58656.82
 6129.6310211.7914198.8617941.8826195.1428281.85
River Rch & RM=3120,126,58407.67
 6130.2910213.1314200.9317944.7426199.3228286.61
River Rch & RM=3120,126,58158.52
 6152.9610258.6314271.25 18041.726340.8828446.23
River Rch & RM=3120,126,57909.36
 6154.4610261.6714275.9918048.2426350.4328457.08
River Rch & RM=3120,126,57660.21
 6157.3810267.5814285.1518060.9326368.9628478.11
River Rch & RM=3120,126,57411.06
 6158.6910270.2414289.2918066.6626377.32 28487.6
River Rch & RM=3120,126, 57161.9
 6214.7410380.5914458.3218298.0926715.2128862.96
River Rch & RM=3120,126,56912.75
 6218.4710388.3114470.4318314.9726739.8528891.29
River Rch & RM=3120,126, 56663.6
 6241.0510434.2214541.8618413.9926884.4229055.64
River Rch & RM=3120,126,56414.44
  6246.510445.6614559.9618439.3626921.47 29098.7
River Rch & RM=3120,126,56165.29
 6257.9210469.6314597.8318492.4726999.0129188.74
River Rch & RM=3120,126,55916.14
 6265.8810486.5214624.6618530.2227054.13 29253.2
River Rch & RM=3120,126,55666.98
 6268.4210492.0114633.4518542.6727072.2929274.67
River Rch & RM=3120,126,55417.83
 6269.29 10493.914636.4718546.9427078.5429282.04
River Rch & RM=3120,126,55168.68
 6282.3710522.1714681.7418611.0427172.1229392.64
River Rch & RM=3120,126,54919.52
 6283.3810524.3714685.2818616.0627179.4629401.35
River Rch & RM=3120,126,54670.37
 6284.0310525.8314687.6618619.4827184.4429407.38
River Rch & RM=3120,126,54421.22
 6294.0410547.8714723.2318670.1427258.4129495.72
River Rch & RM=3120,126,54172.06
 6296.9210554.35 14733.8 18685.327280.5329522.47
River Rch & RM=3120,126,53922.91
 6299.3910559.9714742.99 18698.527299.8129545.87
River Rch & RM=3120,126,53673.76
 6300.2610561.9114746.1618703.0527306.4529553.89
River Rch & RM=3120,126,53175.45
 6342.1110652.2814890.8718907.9927605.6729907.29
River Rch & RM=3120,126,52677.14
 6345.6310660.4814904.4218927.6327634.3429942.54
River Rch & RM=3120,126,52178.84
 6349.6810669.9814920.1918950.5127667.7529983.76
River Rch & RM=3120,126,51680.53
 6362.6310700.1914970.1819022.9827773.55 30113.9
River Rch & RM=3120,126,51431.38
 6364.7710705.3714978.87 19035.727792.1230137.12
River Rch & RM=3120,126,51182.22
 6366.3510709.2114985.3119045.1327805.8930154.36
River Rch & RM=3120,126,50933.07
 6371.5310721.7415006.3619075.9727850.9230210.71
River Rch & RM=3120,126,50683.92
 6372.0610723.0415008.5719079.2127855.6430216.67
River Rch & RM=3120,126,50434.76
 6372.6410724.4915011.0119082.81 27860.930223.29
River Rch & RM=3120,126,50185.61
 6374.23 10728.415017.6319092.53 27875.130241.18
River Rch & RM=3120,126,49936.46
 6377.4610736.3615031.0819112.3227903.98 30277.6
River Rch & RM=3120,126, 49687.3
 6378.32 10738.515034.7219117.6927911.8330287.53
River Rch & RM=3120,126,49438.15
 6378.8910739.9315037.1519121.2727917.0530294.15
River Rch & RM=3120,126,   49189
 6380.7810744.6515045.1519133.0827934.2930315.99
River Rch & RM=3120,126,48939.84
 6381.5910746.6515048.5519138.0927941.6230325.25
River Rch & RM=3120,126,48192.38
 6392.4710774.0515095.2619207.1728042.47 30453.5
River Rch & RM=3120,126,47444.92
 6396.3210783.7715111.8219231.6928078.2630499.06
River Rch & RM=3120,126,47154.73
 6400.7410794.8915130.7919259.7528119.24 30551.2
River Rch & RM=3120,126,46697.46
 6401.6310797.1415134.6319265.4328127.5330561.75
River Rch & RM=3120,126,   45950
 6751.0611546.1616333.19 20964.530608.1733477.07
River Rch & RM=3120,126,45497.52
 6752.1711548.8916337.84 20971.430618.24 33489.8
River Rch & RM=3120,126,44953.39
 6756.6211559.9416356.6620999.2730658.9433541.33
River Rch & RM=3120,126,44781.32
 6756.8411560.4916357.5921000.6530660.9533543.87
River Rch & RM=3120,126,44540.03
 6764.6111579.9416390.8121049.9930732.98 33635.4
River Rch & RM=3120,126,44298.74
 6769.9611593.1716413.3221083.3330781.6733696.99
River Rch & RM=3120,126,44057.46
  6770.511594.5216415.6321086.7630786.6733703.34
River Rch & RM=3120,126,43625.15
 6856.2111798.9716758.8221590.7131522.4434619.49
River Rch & RM=3120,126,43092.31
 6861.7111812.6916782.2721625.5731573.3334684.16
River Rch & RM=3120,126,42609.74
 6863.0411816.0116787.9521634.0231585.6734699.85
River Rch & RM=3120,126,42127.17
  6866.511824.6416802.7121655.9831617.7334740.63
River Rch & RM=3120,126,41644.59
 6867.72 11827.716807.9321663.7531629.0834755.06
River Rch & RM=3120,126,40679.45
 6870.5911834.87 16820.221681.9931655.7134788.91
River Rch & RM=3120,126,39939.75
11837.7920420.6229064.0637481.6154723.1555685.34
River Rch & RM=3120,126,39478.08
 11858.620472.8929153.7337615.2354918.24 55915.5
River Rch & RM=3120,126,38098.66
11880.2420527.0929246.62 37753.655120.2656153.59
River Rch & RM=3120,126, 36699.9
11890.5820553.3829291.9537821.37 55219.256270.94
River Rch & RM=3120,126, 35505.8
 12313.121502.1730850.1740076.8258512.15 59950.7
River Rch & RM=3120,126,33808.88
12322.7421526.6830892.5640140.4358605.0460061.03
River Rch & RM=3120,126,32850.11
12340.1321571.1930969.7140256.4358774.3960262.74
River Rch & RM=3120,126,   32075
12346.9421588.7531000.2540302.4658841.5960343.05
River Rch & RM=3120,126,30490.64
12379.7921674.4931150.0240528.8259172.0760739.93
River Rch & RM=3120,126,29640.35
12387.4121694.6531185.42 40582.559250.4560834.59
River Rch & RM=3120,126, 28137.3
12402.6921735.4531257.28 40691.759409.8961027.75
River Rch & RM=3120,126,26651.83
12414.0621766.0431311.3540774.0759530.1561173.98
River Rch & RM=3120,126,26029.32
12415.7921770.7431319.6740786.7759548.6961196.57
River Rch & RM=3120,126,23872.98
12659.5722366.3432336.0442300.6261758.91 63781.1
River Rch & RM=3120,126,21450.47
 12696.422467.2732515.9642576.6362161.8864275.41
River Rch & RM=3120,126,   19408
12817.3922783.3433070.4443418.9563391.6765758.79
River Rch & RM=3120,126,19282.41
12817.7322784.3133072.1943421.64 63395.665763.67
River Rch & RM=3120,126,14471.57
12898.4223011.2233481.1344054.2264319.1766909.91
River Rch & RM=3120,126,11742.49
13335.7624130.6135437.0447023.8668654.8372115.27
River Rch & RM=3120,126,7485.295
13534.5424717.3836518.7148727.4871142.1275276.65
Boundary for River Rch & Prof#=3120,126,1
Up Type= 0
Dn Type= 2
Boundary for River Rch & Prof#=3120,126,2
Up Type= 0
Dn Type= 2
Boundary for River Rch & Prof#=3120,126,2
Up Type= 0
Dn Type= 2
Boundary for River Rch & Prof#=3120,126,2
Up Type= 0
Dn Type= 2
Boundary for River Rch & Prof#=3120,126,2
Up Type= 0
Dn Type= 2
Boundary for River Rch & Prof#=3120,126,2
Up Type= 0
Dn Type= 2

--- 3120_ras.g01 (geometry) ---

Geom Title=3120
Program Version=4.10

River Reach=3120,126
Reach XY= 30
608737.874633493 753748.39636439610887.706934214752543.784886767
612799.376195846750353.873701937611053.213556379749462.034488541
611476.351628212747585.441727543610131.578382522744569.004486001
612376.218303265742385.038890224 612644.70565954738671.003638962
614709.251810761735585.798912187616788.947369456735496.500257347
618218.130538642734664.476524927 620042.16005361730898.508386408
 618328.43909803728023.636612755618371.361185789727163.489884396
619334.976987661726719.081235372619553.192588928724961.547935689
618624.914339841724101.803736762619465.017631472721892.678512056
 617506.56083855720421.953426053 617482.65366304719437.249998149
615739.777909516719019.811336987615671.750539779718174.323914883
611003.739658029717917.613148291610843.050233333 716047.38745385
610051.583247126715183.649989347609937.915116129714122.045778331
611922.195822566711662.042894019613798.421639055 707312.48274581
612309.509454162705853.741731444612985.953813018705422.461775228

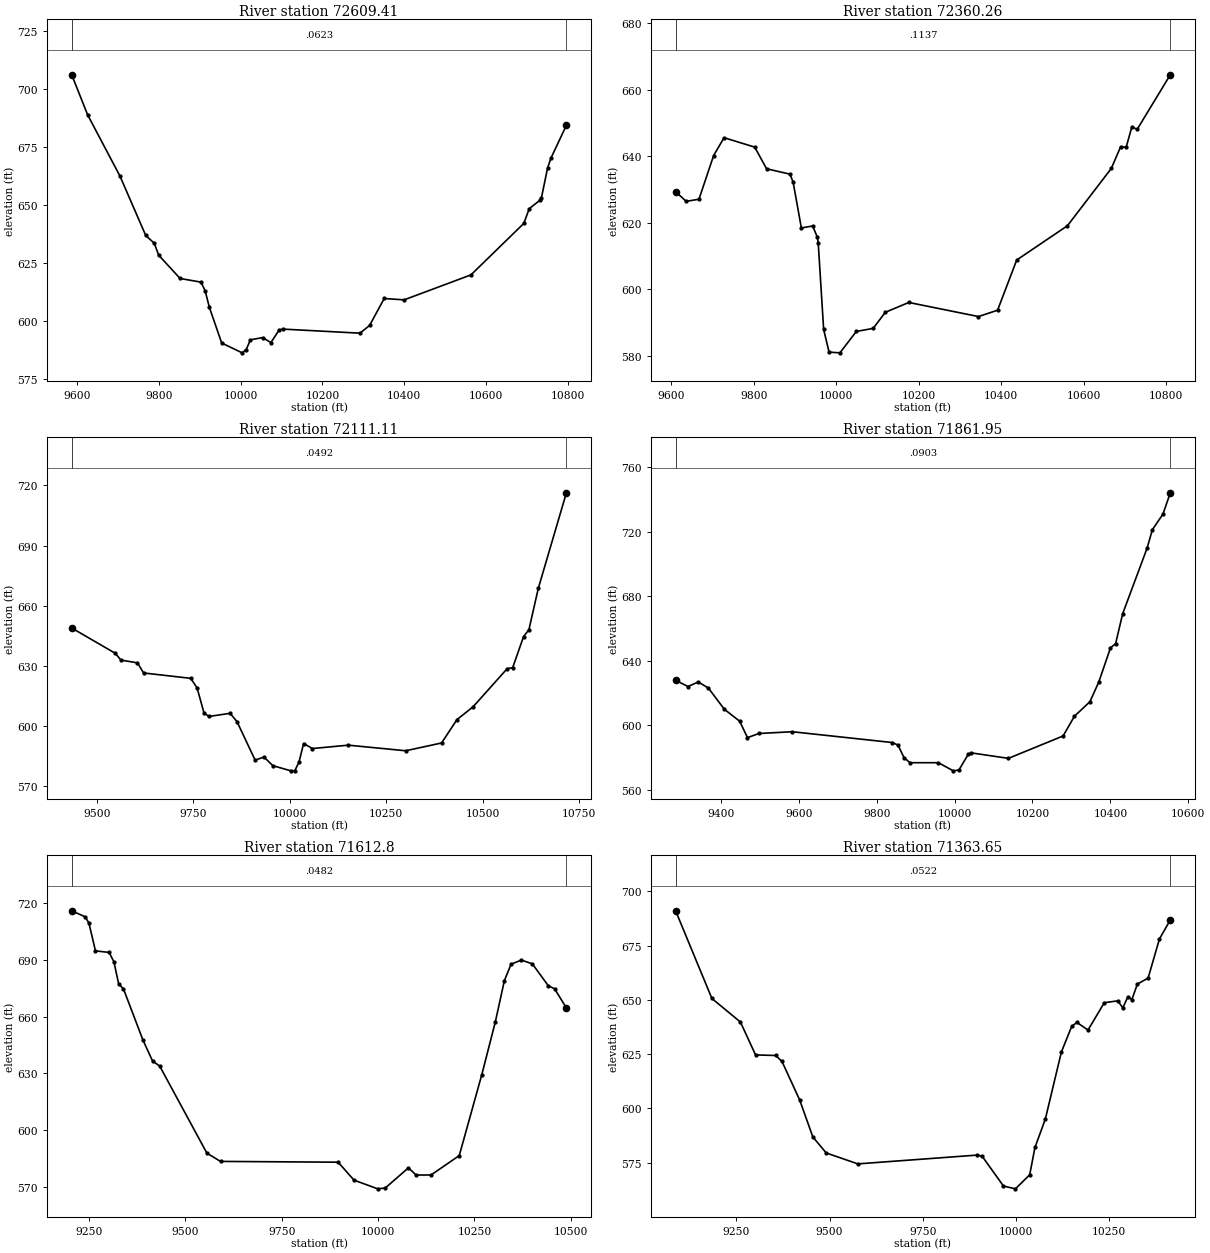
Type RM Length L Ch R = 1 ,72609.41,249.153300,249.153300,249.153300
XS GIS Cut Line= 6
608855.262197272754140.091866044 608759.49812416753910.917710203
608738.319532676753682.439945238608703.390128963753567.074889469
608571.985502894753353.494049837608344.727813258753076.623189353
#Sta/Elev= 30
9586.564  706.03 9625.52688.74389704.823662.25369767.557636.76689788.682633.3316
9799.244 628.2339851.646618.18719903.025616.60139913.135612.76079923.244605.7627
9953.433590.347510003.53586.113410013.55587.547510023.56591.713410053.63592.6993
10073.81590.532810094.19596.038810104.38596.341110291.61594.5927 10315.2597.9167
10350.98609.547910399.68608.967610563.15619.729310692.45 641.93810705.74648.2896
10732.33651.9887 10735.5652.926510750.68665.884310758.91670.113110796.63684.2528
#Mann= 3 , 0 , 0
9586.564  0.0623       09586.564  0.0623       010796.63  0.0623       0
#XS Ineff= 2 , 0
       0                               0
Bank Sta=9586.564,10796.63
Exp/Cntr=0.3,0.1

Type RM Length L Ch R = 1 ,72360.26,249.153400,249.153400,249.153400
XS GIS Cut Line= 6
609221.408916611753925.313064187609104.902605938753791.432263281
609042.621974547753727.299350619608896.767824307753597.739737611
608838.919232913753539.507011208608409.325787884753045.603369853
#Sta/Elev= 30
9610.761629.33219636.256626.4063 9667.33627.0393 9702.92640.1984 9728.16645.5605
9802.473642.72149831.181636.20819888.093634.5862 9895.66632.0919 9915.48618.3935
9942.866618.99039954.406615.54759956.321613.90849969.482587.84859982.643 581.018
10008.95580.802910048.66587.240310089.48588.160610118.93593.004810175.86595.9677
10344.61591.723910390.96 593.63210437.32608.742910560.21619.056610666.55636.3071
10689.13642.829410702.59642.684810716.06648.733410729.53648.130410809.51664.5011
#Mann= 3 , 0 , 0
9610.761  0.1137       09610.761  0.1137       010809.51  0.1137       0
#XS Ineff= 2 , 0
       0                               0
Bank Sta=9610.761,10809.51
Exp/Cntr=0.3,0.1

Type RM Length L Ch R = 1 ,72111.11,249.153300,249.153300,249.153300
XS GIS Cut Line= 6
609526.080197199753786.613502031609407.344889704753665.526218911
609261.420341823753543.814980004608952.390295508753359.255034734
 608834.73223959753272.924683936608533.877651962752985.793811359
#Sta/Elev= 30
9434.929648.91489548.079636.28679562.385 632.9329605.337631.54579621.183626.5057
9743.444 623.8249759.873619.03159777.563606.72199790.167604.79639845.379606.3896
9863.257602.25869910.274583.01959933.216584.58739956.104580.276410003.01577.6989
10013.22577.762810023.99582.111510035.97 591.32710058.72588.821410151.83590.4977
10300.53587.709210393.44591.589410433.35603.255710475.09609.627110563.45628.6531
10577.72629.145210605.88644.5902 10619.9648.142110644.02668.627610716.95716.3542
#Mann= 3 , 0 , 0
9434.929  0.0492       09434.929  0.0492       010716.95  0.0492       0
#XS Ineff= 2 , 0
       09809.714                       0
Bank Sta=9434.929,10716.95
Exp/Cntr=0.3,0.1

Type RM Length L Ch R = 1 ,71861.95,249.153400,249.153400,249.153400
XS GIS Cut Line= 6
  609726.2928022753719.342066754609592.067259288753566.010459815
609482.190051354753455.877440021609251.441342307753253.114680294
609019.949662547753064.747223602608791.110420303 752862.27114537
#Sta/Elev= 30
9283.352627.93699315.211623.97129341.388626.83079367.565623.03439408.451609.9059
9447.999602.45459467.935592.28619497.306594.85039583.059 595.9449840.168589.2415
9854.571587.65939869.986579.9043  9885.4576.72729958.223 576.729 9996.68571.6828
10010.95572.160410035.07581.941910042.96582.808810138.22579.429810278.63593.3099
10307.82 605.58310347.47614.5487 10370.4 626.82110400.33647.974110413.55650.6032
10431.59669.093410494.36709.804210507.95721.294210535.13730.936510554.01744.1937
#Mann= 3 , 0 , 0
9283.352  0.0903       09283.352  0.0903       010554.01  0.0903       0
#XS Ineff= 2 , 0
       09789.763                       0
Bank Sta=9283.352,10554.01
Exp/Cntr=0.3,0.1

Type RM Length L Ch R = 1 , 71612.8,249.153300,249.153300,249.153300
XS GIS Cut Line= 6
609920.817753405 753653.77117476609763.953319546753443.090834035
609633.665267446753289.546314647609562.108148125753213.296344254
609476.780501693753128.634091071609041.505597536752723.688300829
#Sta/Elev= 30
9205.018715.98989240.182 712.7649249.681709.46049266.626694.80619302.118693.9695
9314.506688.99839326.893677.3014 9339.28674.72179389.464647.84499414.745636.6014
9433.315633.89449555.745587.8834 9591.11583.52049896.322 583.105  9937.3573.6321
    9999 569.02410018.57569.468210078.74580.147410098.41576.309110137.31576.3504
 10210.5586.596510269.04629.423610303.84657.058310327.59679.086610344.92687.7704
 10371.5689.933210400.06687.946810441.83676.299310457.84674.763210488.47664.6246
#Mann= 3 , 0 , 0
9205.018  0.0482       09205.018  0.0482       010488.47  0.0482       0
#XS Ineff= 2 , 0
       09862.062                       0
Bank Sta=9205.018,10488.47
Exp/Cntr=0.3,0.1

Type RM Length L Ch R = 1 ,71363.65,249.153400,249.153400,249.153400
XS GIS Cut Line= 6
610085.880691517753598.021440694609882.378581155753270.761271356
609735.767997828753063.171264566609650.165215141 752961.76968087
609396.100091349752703.905494237609265.291058704752561.070865706
#Sta/Elev= 30
9086.784  690.999184.183650.61869260.753639.78289301.421624.6416 9355.33624.3752
9372.388621.63099419.768603.92759455.303586.84299491.251579.50289576.002574.4857
9895.827578.52669909.576578.03779966.889564.2949    9999562.999110037.31569.4545
10051.56582.095310079.33595.110710122.36625.946910150.15637.786510164.04639.5969
10193.91636.094310237.57648.666110273.89649.539410287.45646.276510301.01651.4709
 10311.6650.055610326.41 657.25410355.25660.010210385.63677.997810414.81686.7624
#Mann= 3 , 0 , 0
9086.784  0.0522       09086.784  0.0522       010414.81  0.0522       0
#XS Ineff= 2 , 0
       09859.595                       0
Bank Sta=9086.784,10414.81
Exp/Cntr=0.3,0.1

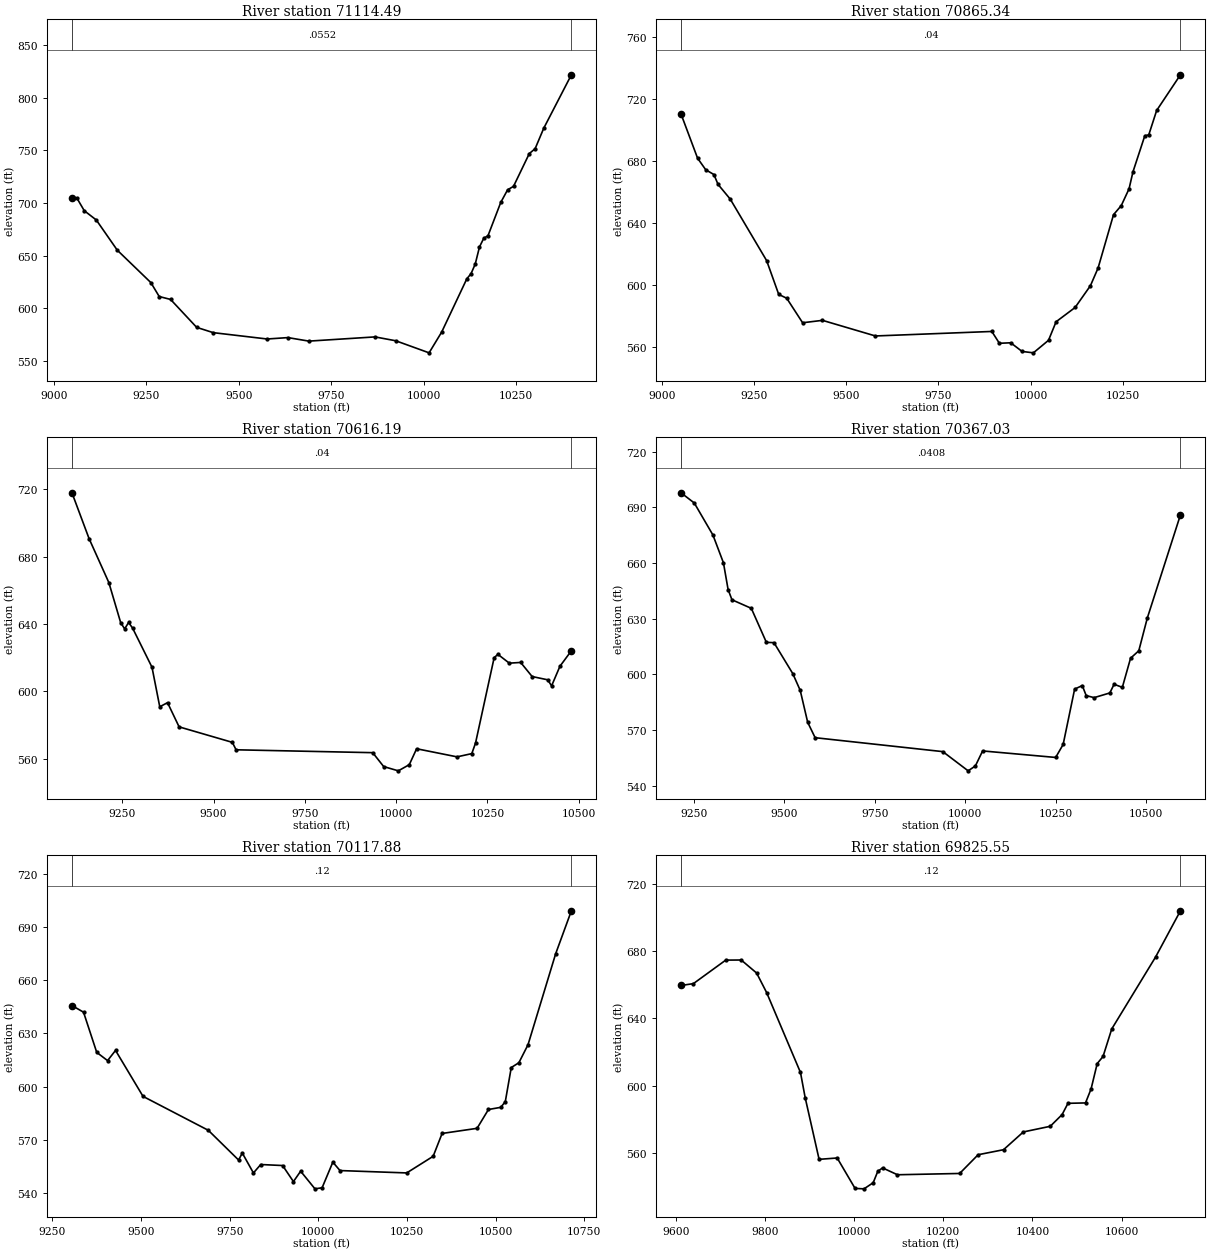
Type RM Length L Ch R = 1 ,71114.49,249.153300,249.153300,249.153300
XS GIS Cut Line= 6
610191.297486185753562.417092825610064.313616375753327.885152485
609753.569220901752717.008878563609689.128729263752596.702370904
609638.450059135752507.328809475 609554.96412514752371.813895377
#Sta/Elev= 30
9048.914704.89219061.781704.99129082.212692.74959114.756683.93819171.527655.2818
9262.217624.5599 9284.89611.30979315.628608.55199386.159582.05129431.022577.0314
9576.828571.01389632.907572.3388 9689.53568.99949868.439572.99859924.518569.3278
10014.62557.878210048.66577.576910116.72628.167110128.06632.990510139.43642.1443
10150.93658.411510162.43666.577210173.92669.028510208.41700.597210226.94712.5833
10242.94715.864210285.63 746.97710301.33751.572610324.68771.0256 10399.4821.7336
#Mann= 3 , 0 , 0
9048.914  0.0552       09048.914  0.0552       0 10399.4  0.0552       0
#XS Ineff= 2 , 0
       09848.463                       0
Bank Sta=9048.914,10399.4
Exp/Cntr=0.3,0.1

Type RM Length L Ch R = 1 ,70865.34,249.153300,249.153300,249.153300
XS GIS Cut Line= 6
610300.812436904753525.428599534610185.730091872753278.914598113
 610113.04804923753093.603041348610051.225602699752898.609028889
609935.166927095752434.824358443609862.945005794752245.569480342
#Sta/Elev= 30
9050.602710.26269095.636681.72149117.841674.26079140.047671.1979 9151.15664.8713
9184.458655.32119283.196615.70329316.034593.91739337.726 591.4479380.936575.6375
9434.882577.18929578.666 567.1259894.901570.02899915.422 562.4059946.204562.7276
9976.986557.151310007.77556.243310048.86564.324110069.48576.289810121.07585.4793
10162.73599.529110183.55610.947910225.47645.329210246.56651.203910267.66662.0043
 10278.3672.971710310.46696.223110321.18696.775510342.62 712.51210407.25735.5294
#Mann= 3 , 0 , 0
9050.602    0.04       09050.602    0.04       010407.25    0.04       0
#XS Ineff= 2 , 0
       0 9851.26        10077.71       0
Bank Sta=9050.602,10407.25
Exp/Cntr=0.3,0.1

Type RM Length L Ch R = 1 ,70616.19,249.153400,249.153400,249.153400
XS GIS Cut Line= 6
610441.025598061753457.576485026 610336.48540587753196.918054357
610287.185147069753024.886306982610254.546469432752847.809171519
610212.947786335752396.495491145610131.974194058752135.291750023
#Sta/Elev= 30
9112.322717.92369159.187 690.7069213.331664.59179245.817640.72959256.646637.0638
9267.475640.84899278.304 637.5529331.533 614.2649352.802590.76729374.071  593.21
9405.776578.83229551.519569.63039561.853565.20749935.971563.49729966.041555.2382
10006.13552.7027 10036.2556.373510056.24565.825810166.93561.011510207.35562.9363
10217.56569.191410268.58 619.95310278.88621.914910310.05616.689310341.21617.1079
 10372.6608.734410415.23606.792610425.89603.188910448.72614.829810480.09624.0625
#Mann= 3 , 0 , 0
9112.322    0.04       09112.322    0.04       010480.09    0.04       0
#XS Ineff= 2 , 0
       09862.054         10070.9       0
Bank Sta=9112.322,10480.09
Exp/Cntr=0.3,0.1

Type RM Length L Ch R = 1 ,70367.03,249.153300,249.153300,249.153300
XS GIS Cut Line= 6
 610639.33284366 753355.65320796610540.905407842753086.256972977
610498.164278481752890.216270593610466.643746124752368.309611104
610407.226777205 752205.36896543610307.253159284752037.830712513
#Sta/Elev= 30
9214.771697.79549251.462692.28699303.022675.02659332.052660.07179344.946645.6601
9355.598640.14499409.127 635.5279450.755617.19699471.702617.03859523.704600.3678
9544.309591.31239564.914574.13589585.518565.82659938.493558.320410008.49547.9694
10028.49550.6095 10048.5558.6969 10250.4 555.18310271.08 562.16510302.82592.0099
10324.03593.924310334.76588.519810356.66587.409710400.11589.936610411.91594.6156
10434.68592.951910457.44 608.64210480.21612.675510503.73 630.30210595.33685.8924
#Mann= 3 , 0 , 0
9214.771  0.0408       09214.771  0.0408       010595.33  0.0408       0
#XS Ineff= 2 , 0
       09881.887         10082.8       0
Bank Sta=9214.771,10595.33
Exp/Cntr=0.3,0.1

Type RM Length L Ch R = 1 ,70117.88,292.327800,292.327800,292.327800
XS GIS Cut Line= 6
610967.669242386753233.810922949  610789.3315207752843.113296905
 610748.44985026752698.977794855610714.232546276752490.362909165
610686.900563507752422.033694926 610357.28264243751990.906507633
#Sta/Elev= 30
9305.141645.69469337.803641.95059375.016 619.3329405.559614.68829428.067620.4284
9505.598 594.5529689.699575.45329775.051558.72129785.534562.64779816.878551.4421
9837.508556.18829899.196555.62089929.707546.57799950.048552.4246  9990.4542.4981
10010.56543.106110040.82557.519710061.01552.788810249.14 551.45410323.72560.8224
10348.95573.680410447.51576.562310479.65587.168210514.36588.383110527.13 591.589
10543.95610.790510565.45613.501710591.19623.611810669.18674.8604 10713.5699.0448
#Mann= 3 , 0 , 0
9305.141    0.12       09305.141    0.12       0 10713.5    0.12       0
#XS Ineff= 2 , 0
       09886.884        10130.82       0
Bank Sta=9305.141,10713.5
Exp/Cntr=0.3,0.1

Type RM Length L Ch R = 1 ,69825.55,205.978900,205.978900,205.978900
XS GIS Cut Line= 6
611267.132436501752578.700578452611054.269008041752453.137997861
610863.753528117752415.591909027610766.121308376752356.987916163
610637.937892167752235.625918664610385.197834699751942.597545689
#Sta/Elev= 30
 9611.35659.52489639.101660.62739711.763674.60129746.438674.66729781.039666.9287
9803.559655.28299879.476607.8366 9889.98592.91019921.264556.23049961.865557.0304
10001.99538.949410022.12538.701510042.68542.346610052.95549.079110063.69551.1502
10097.12547.068810236.71547.836310278.18558.967610335.17561.946810379.62572.5033
10440.02575.859910466.68582.8299 10479.8589.512310519.16589.7471 10531.7598.0791
 10545.4613.117210558.52617.344210578.05633.7033 10676.6676.516810732.23703.9126
#Mann= 3 , 0 , 0
 9611.35    0.12       0 9611.35    0.12       010732.23    0.12       0
#XS Ineff= 2 , 0
       09930.715        10177.18       0
Bank Sta=9611.35,10732.23
Exp/Cntr=0.3,0.1

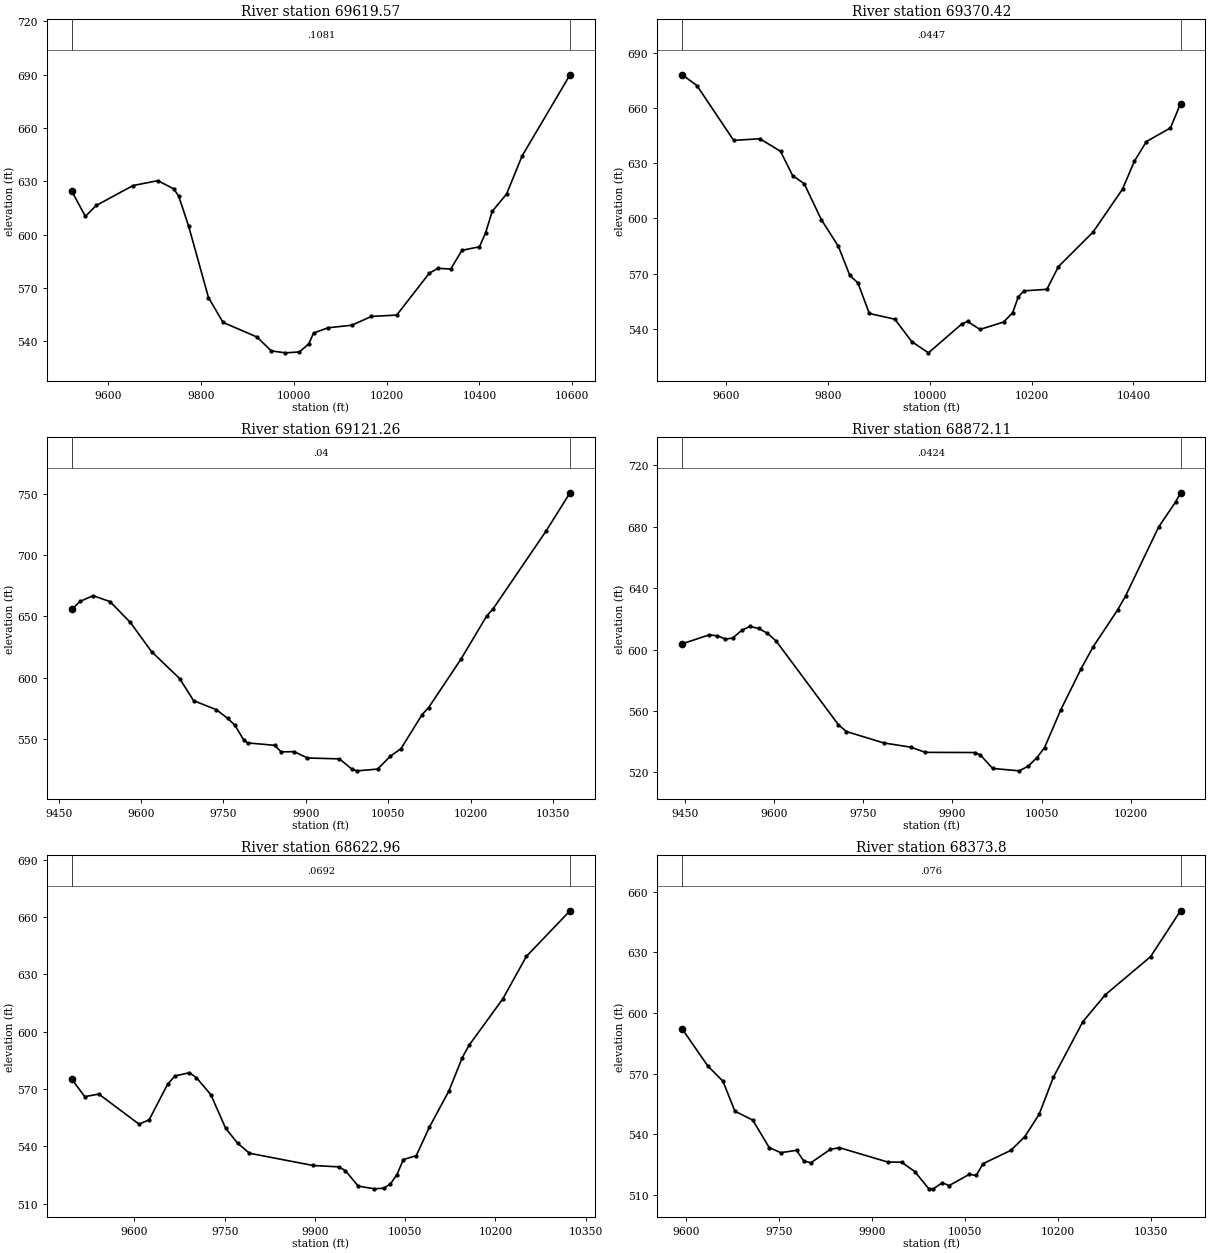
Type RM Length L Ch R = 1 ,69619.57,249.153400,249.153400,249.153400
XS GIS Cut Line= 6
 611369.57395859752392.576751406 611247.29915217752323.400112203
611096.616449264752261.880706872610729.298171542752165.691045771
 610593.87854103752084.772283987610419.422870891751932.623258872
#Sta/Elev= 30
9521.296624.32449550.345610.28559573.841 616.4399653.144627.62249706.616 630.366
9741.012625.75679751.691621.61369773.047604.79239815.817564.68839847.279550.7182
9920.357542.52469951.236534.72269981.872533.626310011.99534.136210032.17538.7079
 10042.3544.698710072.99547.674310124.81549.147210167.16554.078310221.75554.8527
10291.79578.312510310.45  581.11 10338.2580.717610362.47591.253910400.12593.2079
 10413.3601.008310427.57613.1313 10458.6622.846710492.11644.273710595.46689.8616
#Mann= 3 , 0 , 0
9521.296  0.1081       09521.296  0.1081       010595.46  0.1081       0
#XS Ineff= 2 , 0
       09873.726                       0
Bank Sta=9521.296,10595.46
Exp/Cntr=0.3,0.1

Type RM Length L Ch R = 1 ,69370.42,249.153300,249.153300,249.153300
XS GIS Cut Line= 6
611459.008966049752227.316411538611377.371073647752173.092628388
611255.715184234752102.669012979610862.895135762751916.642811224
 610762.12629314751864.023501728610598.472920682751764.686660451
#Sta/Elev= 30
9513.915678.06139542.737672.1379 9614.69642.42949666.228 643.308 9706.72636.5143
9730.419623.34359753.309618.88399786.872 599.3969820.434584.8253 9842.81569.1144
9858.828564.98449881.131548.42249931.429545.29369964.388533.15029997.346527.0327
10063.17542.809710074.14544.060610098.44539.749210144.73543.7422 10162.7548.8601
10173.79557.418410184.88560.692210229.96 561.53410252.53573.844910320.68592.6469
10378.46615.9348 10401.6630.986310425.28641.760110472.63649.207210492.39662.3464
#Mann= 3 , 0 , 0
9513.915  0.0447       09513.915  0.0447       010492.39  0.0447       0
#XS Ineff= 2 , 0
       09898.938                       0
Bank Sta=9513.915,10492.39
Exp/Cntr=0.3,0.1

Type RM Length L Ch R = 1 ,69121.26,249.153400,249.153400,249.153400
XS GIS Cut Line= 6
611566.355222408752080.215964784611414.326487813751954.102521558
611315.986126583751881.121127844611217.387953053751816.385958727
611049.943798553751718.626229927610817.550879637751571.378703231
#Sta/Elev= 30
9474.172655.89839489.204662.28289512.654666.89219543.496 662.1029580.631645.0778
9619.297621.28029670.298599.44759695.788581.39019737.335574.00539758.053566.9066
9770.895561.39949787.675548.96039794.184 546.9979843.214545.03359855.177539.7133
9879.102539.83769903.028534.71279961.316 533.9929984.522525.43249993.738524.2477
 10030.8525.674310053.93536.133510073.42542.326310111.84570.059110123.59575.7075
10182.34615.054410229.34650.310610241.09656.2167 10337.9719.801410381.16750.6983
#Mann= 3 , 0 , 0
9474.172    0.04       09474.172    0.04       010381.16    0.04       0
#XS Ineff= 2 , 0
       09857.272                       0
Bank Sta=9474.172,10381.16
Exp/Cntr=0.3,0.1

Type RM Length L Ch R = 1 ,68872.11,249.153300,249.153300,249.153300
XS GIS Cut Line= 6
611663.074174686751987.551100325611571.148636477751890.607237263
611471.921465787751780.290784619611292.532088844751574.637834039
   611207.758536751481.914033259 611099.11861221751369.227510595
#Sta/Elev= 30
 9446.12603.75299490.978609.49819504.759608.9452 9518.54606.83859530.521607.4059
9546.102612.50989559.587615.0263 9574.12613.70489588.912 610.6169603.865605.4417
9708.311551.05739721.761546.62489784.436539.19819830.215536.43579854.249533.0738
9937.032532.94779946.922531.36049967.505522.606110012.16521.036410026.98523.9983
 10041.8529.541710054.71  536.1510081.81 560.598 10115.9587.313110136.15601.6265
10177.41625.672710191.17 635.10810246.51679.776110274.84 695.96310283.18702.0059
#Mann= 3 , 0 , 0
 9446.12  0.0424       0 9446.12  0.0424       010283.18  0.0424       0
#XS Ineff= 2 , 0
       09785.934                       0
Bank Sta=9446.12,10283.18
Exp/Cntr=0.3,0.1

Type RM Length L Ch R = 1 ,68622.96,249.153300,249.153300,249.153300
XS GIS Cut Line= 6
611763.231457386751891.592027079611671.987120826751772.378414939
611593.319228775 751646.76950037611545.646235617751548.972456423
611463.214606392751339.950183286611364.488714867751171.338649947
#Sta/Elev= 30
9496.204575.13479517.599566.05219540.921567.40579607.811551.68049624.562553.9283
9655.202572.50329667.186576.84019691.154578.56199703.139575.98639727.107567.0864
9751.655549.54069771.474541.74779791.293536.47489896.822530.08039939.883529.3463
9950.606527.36419972.051519.2835    9999517.863910014.86518.215110025.54 520.489
10036.22525.212410046.89533.170310068.38535.193910090.11550.035910122.69569.0621
10144.92586.515310156.11592.890510212.34  617.2410251.37639.387810323.92663.2274
#Mann= 3 , 0 , 0
9496.204  0.0692       09496.204  0.0692       010323.92  0.0692       0
#XS Ineff= 2 , 0
       09807.665                       0
Bank Sta=9496.204,10323.92
Exp/Cntr=0.3,0.1

Type RM Length L Ch R = 1 , 68373.8,249.153400,249.153400,249.153400
XS GIS Cut Line= 6
611944.205856738751718.203380993611819.476134001751526.289102675
611712.861058812751300.736106634611650.063390462751183.539847319
611612.223410886751127.294476307611532.774819336751032.235106941
#Sta/Elev= 30
9594.169592.03969635.025573.90159659.634566.29099679.004551.44689707.729547.0687
9734.156533.52079752.857530.95979778.374532.14339789.959526.82349801.544525.9866
9832.832532.60689847.277533.45149925.604526.33189947.733526.28539969.126521.5889
9991.511 513.183    9999513.0912 10013.4516.089110024.35514.690910057.18520.2806
10068.13519.7115 10079.2 525.52810123.87532.105810146.39538.845210169.49549.8816
10192.58568.275210240.22595.782410276.54609.107510349.28627.859810397.58650.5583
#Mann= 3 , 0 , 0
9594.169   0.076       09594.169   0.076       010397.58   0.076       0
#XS Ineff= 2 , 0
       09862.975                       0
Bank Sta=9594.169,10397.58
Exp/Cntr=0.3,0.1

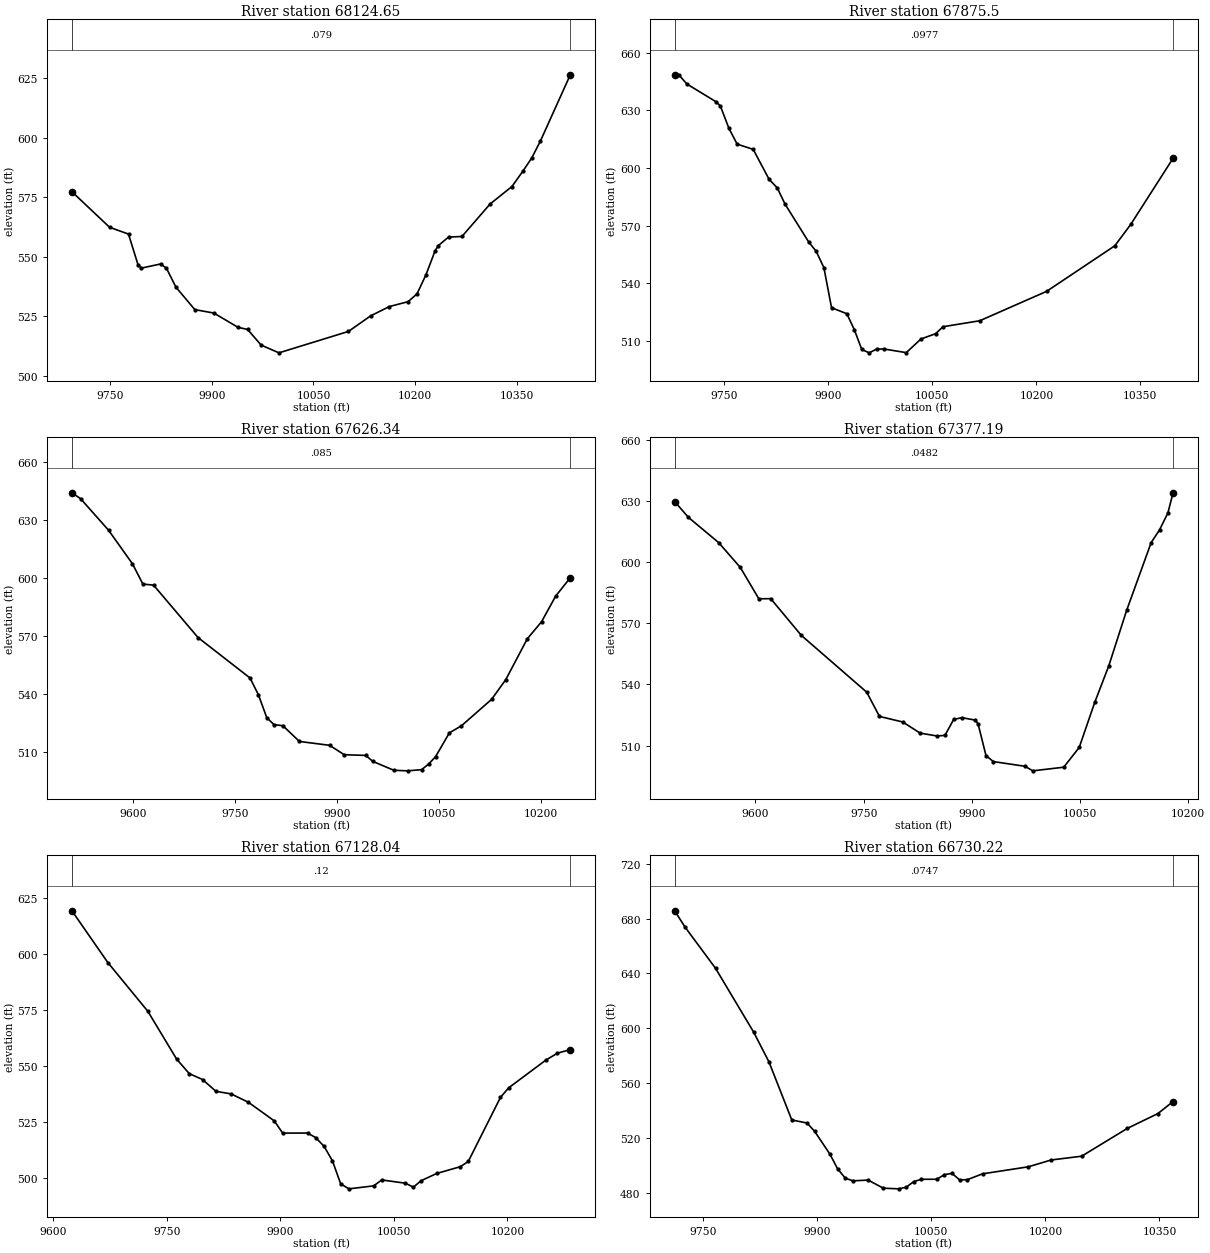
Type RM Length L Ch R = 1 ,68124.65,249.153300,249.153300,249.153300
XS GIS Cut Line= 6
612166.667844365751454.710318959611952.595860721751236.269311395
611945.624656969751229.075717654 611816.88283033751105.882703677
611731.152869042751031.227289199611630.436490959750951.508985307
#Sta/Elev= 30
9693.152577.36919748.752562.42889776.754559.56729790.756546.72769795.545545.2584
9824.119547.0075 9832.76545.24849846.762537.29299874.764527.83719902.767526.4029
9938.416 520.4179952.704519.49239972.774512.9138    9999509.6851 10101.7518.6851
10134.45525.229510162.13529.1286 10189.7531.177110202.96534.462310216.22542.5291
10229.48552.452110234.23554.682110249.46558.315210269.26558.554710310.92572.2202
10343.14579.550210359.75586.1772 10372.5591.599210385.25598.703510429.33626.4816
#Mann= 3 , 0 , 0
9693.152   0.079       09693.152   0.079       010429.33   0.079       0
#XS Ineff= 2 , 0
       09878.949                       0
Bank Sta=9693.152,10429.33
Exp/Cntr=0.3,0.1

Type RM Length L Ch R = 1 , 67875.5,249.153400,249.153400,249.153400
XS GIS Cut Line= 6
612369.679324775751178.465397926612291.061987671751125.448671749
612152.838313878 751053.61096984611925.992738844750971.810428331
611830.622627653750932.022419688611719.680786869750877.740578859
#Sta/Elev= 30
 9678.38648.46039684.433648.40249696.146643.63369738.179634.41169744.355 632.199
9756.408620.8377 9768.46612.42219791.694609.66899814.714594.03399826.224589.7417
9837.734581.1333 9871.53561.63269882.569556.64839893.608548.18569904.646527.3676
9926.724 524.2429937.513 515.9159948.234505.65849958.955503.90789969.675505.8574
9980.396505.896810012.41504.0129 10033.6511.111110054.79513.861110065.38517.4847
10118.36520.5802 10214.7 535.85310313.13559.551710336.07  570.6410397.14605.0443
#Mann= 3 , 0 , 0
 9678.38  0.0977       0 9678.38  0.0977       010397.14  0.0977       0
#XS Ineff= 2 , 0
       0                               0
Bank Sta=9678.38,10397.14
Exp/Cntr=0.3,0.1

Type RM Length L Ch R = 1 ,67626.34,249.153300,249.153300,249.153300
XS GIS Cut Line= 6
612535.841912697751043.303292825 612346.03225148750883.090288208
 612240.63153159750817.377501754612166.466894982 750791.15697678
611992.726379144750750.077631121 611894.89624816750717.897453051
#Sta/Elev= 30
9510.576644.08449523.271  641.059564.569624.67969599.717607.29099615.006596.8137
9630.667596.28469696.051569.16279772.616 548.1969784.962539.51749797.284527.5941
9807.868524.07279820.958523.48759845.257515.35249889.635513.34889911.141508.4846
9942.796508.11969953.246505.02929984.131500.422510004.58500.136810025.02500.7483
10035.24503.634510045.46507.423710065.91519.821110083.45523.409510128.05537.1772
10148.88547.394110180.42568.459210201.44577.3141 10222.1590.536510243.75600.1013
#Mann= 3 , 0 , 0
9510.576   0.085       09510.576   0.085       010243.75   0.085       0
#XS Ineff= 2 , 0
       0                               0
Bank Sta=9510.576,10243.75
Exp/Cntr=0.3,0.1

Type RM Length L Ch R = 1 ,67377.19,249.153400,249.153400,249.153400
XS GIS Cut Line= 6
612578.708446111751008.434246988612429.325956617750856.209432177
612343.190019161750740.762382542 612296.91556595750647.188568001
612254.906106917750538.867334003612203.243298328750438.782975768
#Sta/Elev= 30
9487.961629.67069507.059621.90399548.907609.55539578.973597.35529604.705581.9666
9621.165582.03389663.537564.03559754.285536.15349771.855 524.2879804.184521.5405
9828.309516.09069852.037514.66629862.678515.00379874.783522.80839886.156523.6582
9904.894522.45769908.684520.52189919.601505.04969929.816 502.125 9973.72  499.82
9984.427497.589210027.33499.368210048.82509.058110070.41 531.23910089.69548.9575
 10114.5576.232110148.56609.538210160.13615.764410171.71624.0132 10178.9 633.965
#Mann= 3 , 0 , 0
9487.961  0.0482       09487.961  0.0482       0 10178.9  0.0482       0
#XS Ineff= 2 , 0
       0                               0
Bank Sta=9487.961,10178.9
Exp/Cntr=0.3,0.1

Type RM Length L Ch R = 1 ,67128.04,397.816200,397.816200,397.816200
XS GIS Cut Line= 6
612725.636575948750888.918081673612668.913750209750828.823697281
612600.325734064750735.530298896612515.888815244750561.351005666
 612458.67399441750381.289927284 612412.74303289750319.680908724
#Sta/Elev= 30
9624.367619.39899671.835 596.3159724.822574.51619762.764553.24429779.536546.7155
9797.116544.10969814.695538.84749834.923537.67229857.733533.94469891.949525.6337
 9903.01520.19179935.884520.22269946.842518.13929957.801514.25089968.759507.8516
9979.717 497.5239990.675495.326110023.35496.656810033.94499.297910065.34497.8374
10075.68 496.06610086.03498.957510106.71502.191710137.87505.207710148.35507.5398
10190.95536.166610201.78540.401810251.04552.798610266.21555.853510283.24557.4692
#Mann= 3 , 0 , 0
9624.367    0.12       09624.367    0.12       010283.24    0.12       0
#XS Ineff= 2 , 0
       0                               0
Bank Sta=9624.367,10283.24
Exp/Cntr=0.3,0.1

Type RM Length L Ch R = 1 ,66730.22,349.643800,349.643800,349.643800
XS GIS Cut Line= 2
613088.607777983 750343.74312377612435.191623978750292.181384643
#Sta/Elev= 30
9712.389685.74559726.039673.85979766.164643.77619816.319597.18489836.381575.5441
9866.474533.08269886.537530.89169896.568524.7545 9916.63508.14399926.661497.5017
9936.692490.70579946.723 488.6999966.785489.23739986.848483.342810006.91482.8592
10016.94484.046210026.97488.2063   10037489.817710057.07489.8498 10067.1493.2023
10077.13494.148610087.16489.388510097.19489.528410117.25493.805810177.44498.9317
10207.53503.902610247.66506.678210307.84 527.00410347.97537.799910367.84 546.534
#Mann= 3 , 0 , 0
9712.389  0.0747       09712.389  0.0747       010367.84  0.0747       0
#XS Ineff= 2 , 0
       0                               0
Bank Sta=9712.389,10367.84
Exp/Cntr=0.3,0.1