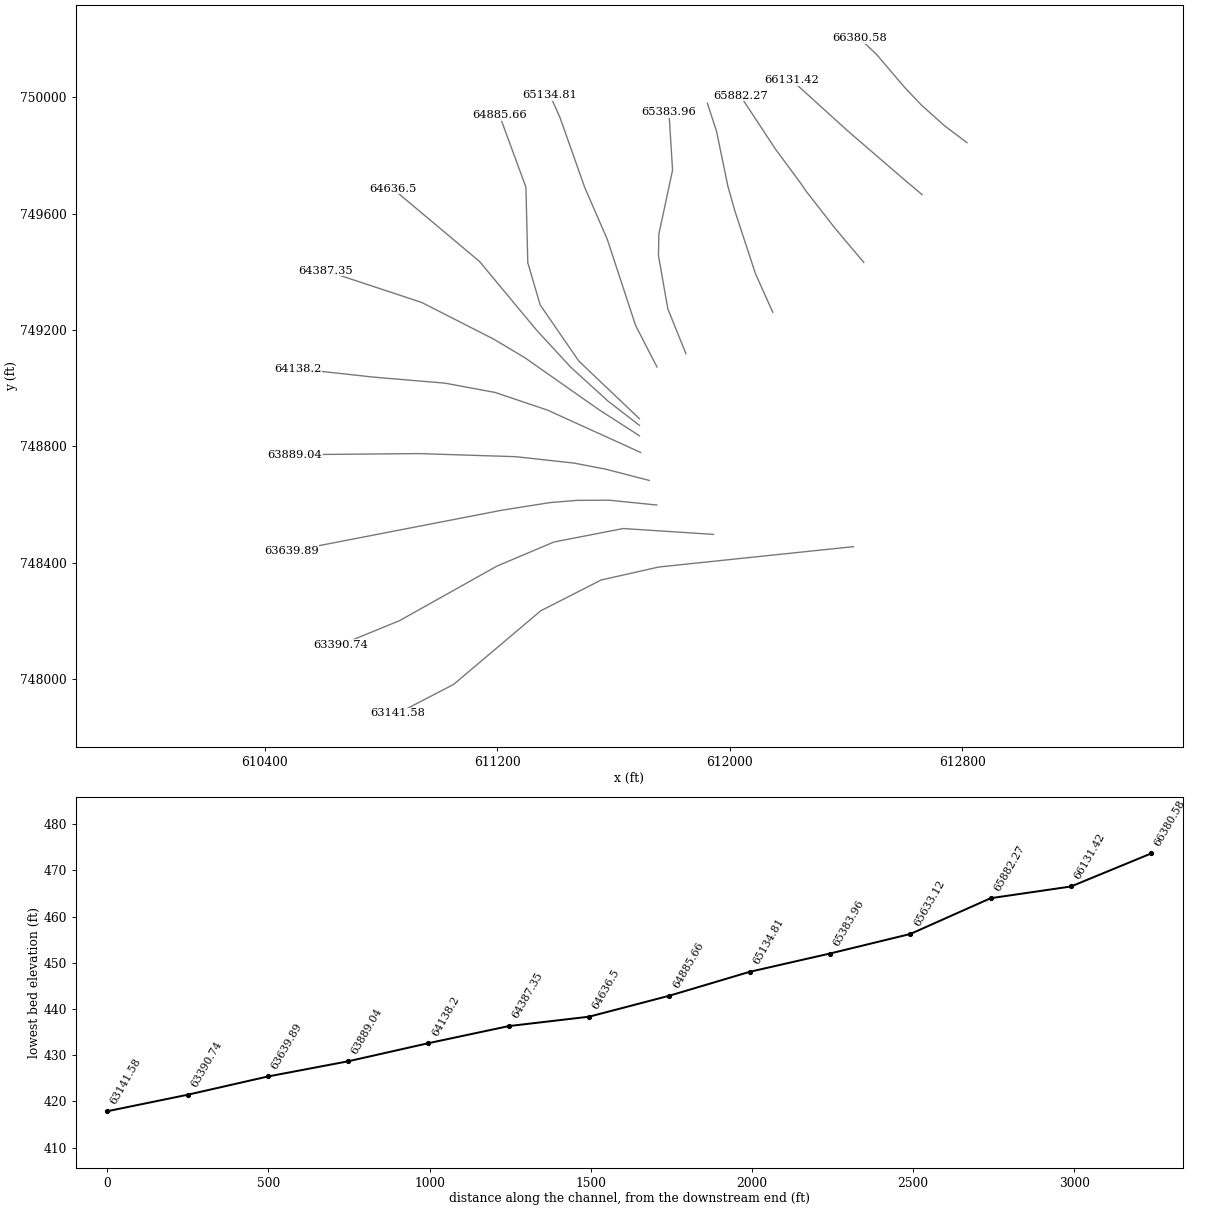
HEC-RAS study 3120_ras.prj: 3120

--- 3120_ras.g01 (geometry) --- (continued)

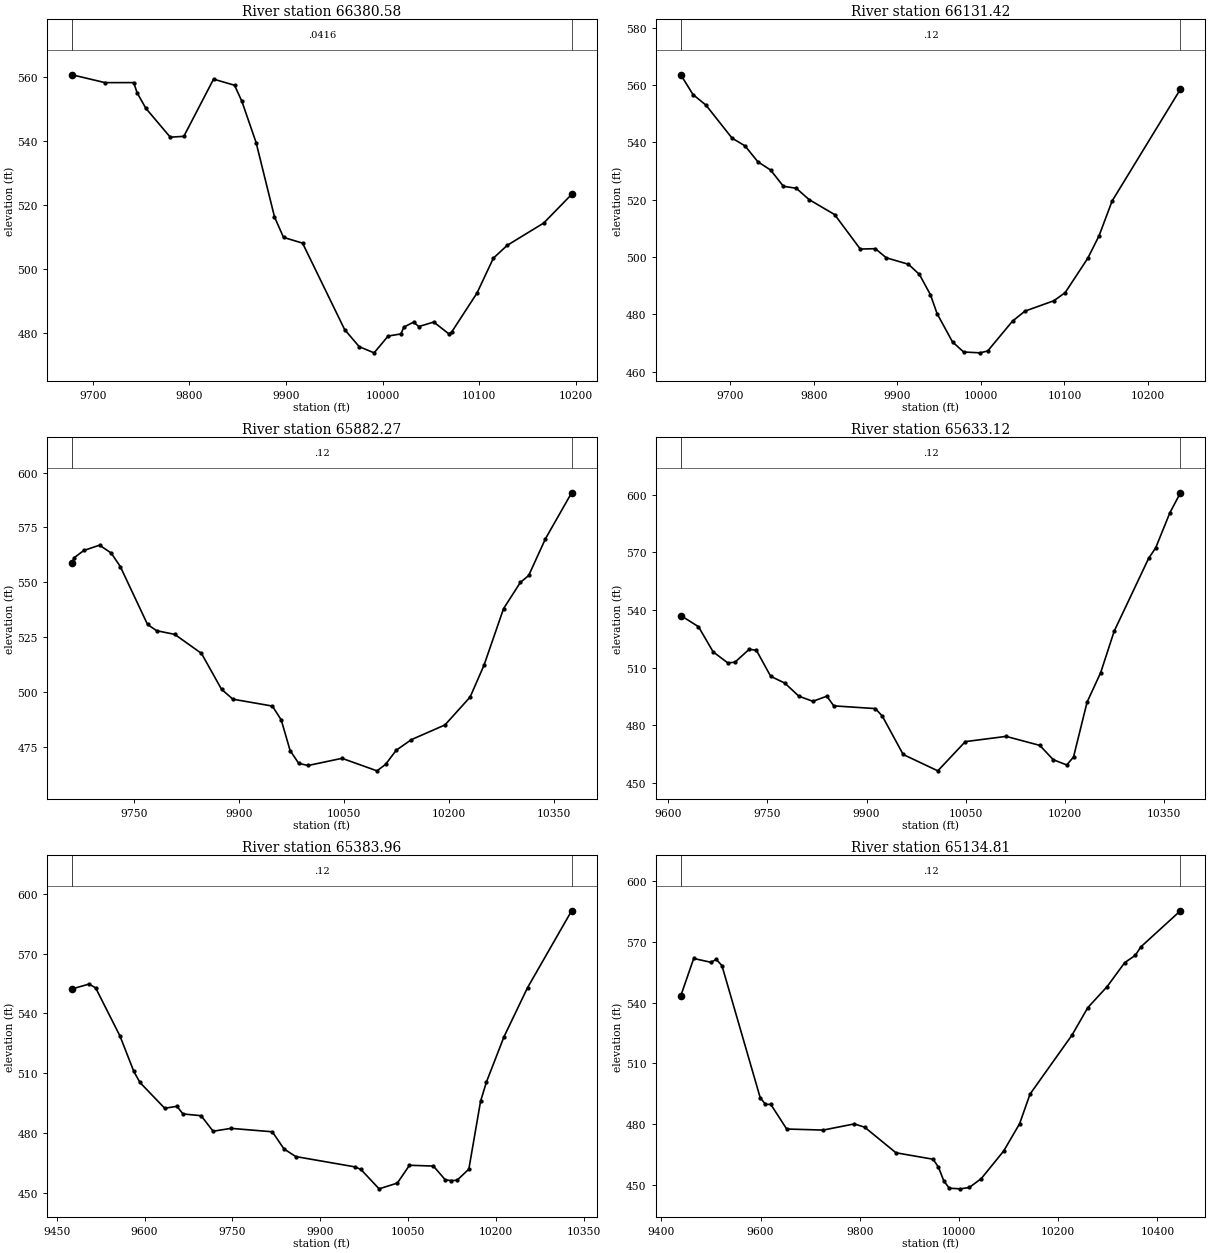
Type RM Length L Ch R = 1 ,66380.58,249.153400,249.153400,249.153400
XS GIS Cut Line= 6
612816.062592707749844.396264398612739.068052042749902.452596646
612659.046229384749973.978407662612601.691812359750034.386791448
612503.751380711750149.423337213612446.043179807750203.361382431
#Sta/Elev= 30
9678.449560.69729712.671558.24189742.401558.24459745.891555.05399754.925550.2059
9780.217541.16579794.258541.43629825.023559.33129846.779557.42159854.378552.3484
9869.056539.49679888.111516.21349897.433509.80739917.158508.01059960.729480.9447
9975.834475.59269991.226473.674210005.76478.9372 10018.9479.5891 10022.1 481.751
10032.03483.269210037.54481.906410052.97483.3109 10068.4479.662210071.42480.1398
10097.68492.353610114.69503.299810129.01507.318710166.84514.302610195.71523.2709
#Mann= 3 , 0 , 0
9678.449  0.0416       09678.449  0.0416       010195.71  0.0416       0
#XS Ineff= 2 , 0
       0                               0
Bank Sta=9678.449,10195.71
Exp/Cntr=0.3,0.1

Type RM Length L Ch R = 1 ,66131.42,249.153300,249.153300,249.153300
XS GIS Cut Line= 6
612661.874221517749665.537753811612602.011316803749715.913081472
612409.182134156749882.042595575612390.465290436749898.861405582
612388.954384923749900.171811827 612212.90980426 750059.89587537
#Sta/Elev= 30
9641.075563.56879655.771556.65559671.302552.95789702.364541.47749717.895538.7664
9733.235533.22549748.556 530.3119763.877 524.6419779.198523.96999794.565520.0064
 9825.16514.76359855.801  502.749873.762502.86879886.961499.6844 9913.36497.4313
9926.559493.86059939.759486.77339947.726480.15219966.157470.29949979.459466.8062
    9999466.513710008.19467.161210037.95477.616910052.83481.079110087.35484.6976
10100.86487.526510127.86499.513310141.36507.362910157.01519.5242 10238.7 558.545
#Mann= 3 , 0 , 0
9641.075    0.12       09641.075    0.12       0 10238.7    0.12       0
#XS Ineff= 2 , 0
       0                               0
Bank Sta=9641.075,10238.7
Exp/Cntr=0.3,0.1

Type RM Length L Ch R = 1 ,65882.27,249.153300,249.153300,249.153300
XS GIS Cut Line= 6
612461.016346093749432.542618311612362.913212191749549.034390103
612260.123859113749680.864151404 612244.75089692749703.950467324
612157.558049629749821.786138388612035.994023944750006.329718448
#Sta/Elev= 30
9661.046558.97879664.384561.25089677.967564.49669700.509566.92479717.147563.3488
9730.144 557.1959769.134530.77539782.131527.90939808.124526.23049846.293517.5468
9875.026501.17459891.289496.66239947.737493.52899960.418487.20969973.098473.2527
9985.552467.3457    9999466.427510047.33469.6895 10097.4463.982310109.69466.9226
10124.87 473.36810146.55478.200510194.66484.922710230.59497.630410250.43512.0989
10278.48537.981310302.43549.901810314.41553.092510338.36569.824410375.87590.8274
#Mann= 3 , 0 , 0
9661.046    0.12       09661.046    0.12       010375.87    0.12       0
#XS Ineff= 2 , 0
       0                               0
Bank Sta=9661.046,10375.87
Exp/Cntr=0.3,0.1

Type RM Length L Ch R = 1 ,65633.12,249.153400,249.153400,249.153400
XS GIS Cut Line= 6
612147.956020541749261.160682844612088.419005594749393.778581707
612018.005644916749608.073808328611993.589767814749694.463659415
  611954.4194753749884.089564092611923.033942766749980.059932121
#Sta/Elev= 30
9619.126 537.0969645.936531.27659668.081518.19489690.225512.4211  9701.1512.8011
9722.705519.53979733.508518.99449755.113505.44269776.482501.91199797.667 495.119
9818.851492.42789839.979495.09919850.477490.06599913.466488.64229923.964484.6928
9955.459464.752210007.81456.239810049.36471.446110111.07 474.17410162.01469.4825
10182.38462.024910202.76459.3019   10213463.431410233.51 492.01310254.03507.3403
10274.56529.007810326.64566.895210337.21572.300810358.57590.473910374.65600.9849
#Mann= 3 , 0 , 0
9619.126    0.12       09619.126    0.12       010374.65    0.12       0
#XS Ineff= 2 , 0
       0                               0
Bank Sta=9619.126,10374.65
Exp/Cntr=0.3,0.1

Type RM Length L Ch R = 1 ,65383.96,249.153300,249.153300,249.153300
XS GIS Cut Line= 6
611849.268519514749118.630041044 611787.02240076749272.543331282
611754.657812018749456.807403977611756.226735689749530.456563315
611803.217496655749749.881267834611790.876892659749949.325734415
#Sta/Elev= 30
9476.014552.25259505.417554.7063 9516.51552.74529557.925528.66729581.477510.9502
9592.044505.34619634.311492.42059655.145493.39499665.471489.5753 9696.45488.6765
9716.893480.89759747.425482.3409 9817.93480.61919837.963472.00329857.964468.1978
9958.794 463.0359969.144 461.746 10000.2452.011910031.35454.892610052.02463.8272
10092.92463.439110113.13456.525410123.24456.1366 10133.3456.320610153.35461.8839
10173.39495.940510183.39505.581310213.39 528.28510253.52552.871910328.82591.4472
#Mann= 3 , 0 , 0
9476.014    0.12       09476.014    0.12       010328.82    0.12       0
#XS Ineff= 2 , 0
       09794.086                       0
Bank Sta=9476.014,10328.82
Exp/Cntr=0.3,0.1

Type RM Length L Ch R = 1 ,65134.81,249.153400,249.153400,249.153400
XS GIS Cut Line= 6
611749.637947141749072.853832123611676.177920255 749215.57039972
 611578.65442784749512.113046858611501.318992118749689.860655658
611416.320095519749930.115164027611381.555538316750008.107886155
#Sta/Elev= 30
9439.135  543.299465.247561.77919499.553559.92089510.961561.28749522.208558.2208
9599.242493.07649609.933489.75219620.612489.75199652.647477.58069726.183477.0654
9788.919 480.0999809.831478.49099872.883 465.8559947.749462.66639958.579458.7629
 9969.53451.8367 9980.54448.359910002.57448.051710020.67448.7193 10044.7453.0661
10089.95466.708310122.04480.1678 10143.2494.843810227.87524.008810259.62537.5276
10298.42 547.86310334.04 559.74210355.41563.329910366.21567.449610446.28585.3296
#Mann= 3 , 0 , 0
9439.135    0.12       09439.135    0.12       010446.28    0.12       0
#XS Ineff= 2 , 0
       09823.842                       0
Bank Sta=9439.135,10446.28
Exp/Cntr=0.3,0.1

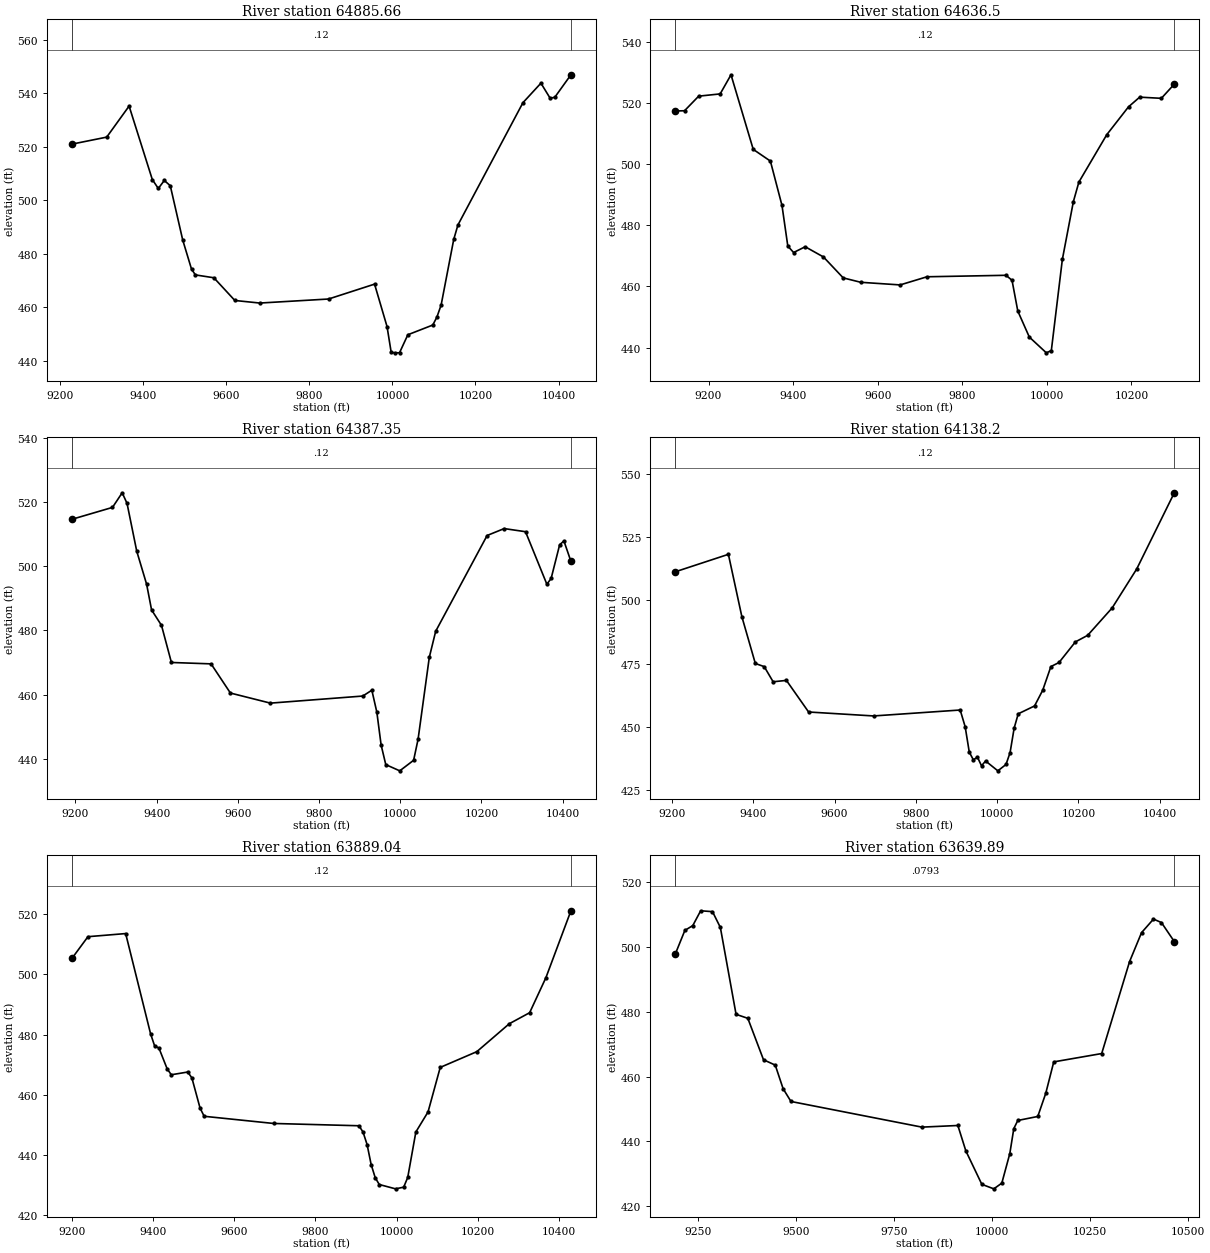
Type RM Length L Ch R = 1 ,64885.66,249.153300,249.153300,249.153300
XS GIS Cut Line= 6
611689.302222461748894.933133648 611480.85856874  749093.0946601
611347.879244041749286.323949682611305.239569499749431.565136691
611298.829605679749691.393863288611207.420445042749939.793349561
#Sta/Elev= 30
9228.079521.01079311.842523.63339365.768535.25659421.642507.76299436.084504.4086
9450.525507.40529464.967505.43529494.883485.13359516.115 474.2079525.456472.0552
9569.919470.98469620.446462.4829 9680.55461.51969846.093463.02989956.937468.6034
9986.999452.7065 9997.02 443.00910007.05442.880610017.07442.918310037.11 449.649
10097.19453.293310107.22  456.3210117.26460.786910147.64485.368210157.76490.7624
 10314.3536.5268 10357.6543.831810379.78538.197210390.95538.545410429.84546.9727
#Mann= 3 , 0 , 0
9228.079    0.12       09228.079    0.12       010429.84    0.12       0
#XS Ineff= 2 , 0
       09916.717                       0
Bank Sta=9228.079,10429.84
Exp/Cntr=0.3,0.1

Type RM Length L Ch R = 1 , 64636.5,249.153400,249.153400,249.153400
XS GIS Cut Line= 6
611689.302222461748871.990469829611581.062733824748955.547785507
 611453.13361537 749071.98564152611336.012318005 749198.90387455
611139.158138759749435.912659609610840.785048094749686.136938041
#Sta/Elev= 30
9121.414517.30729143.203517.38939176.699522.15449227.492522.88579253.129529.1337
9305.724504.77169346.292500.95139373.741486.45149387.465 473.207 9401.19 471.096
9428.638472.97989471.839469.64019518.522462.81099560.088461.37339653.186460.5157
9716.705463.17599903.576463.65859917.814462.02039931.453451.98699958.731443.4855
    9999438.337410010.78439.087510036.86468.839510062.93487.728610075.97494.1044
10141.85509.560210193.33518.667110219.76521.830110270.98521.443410301.65526.0712
#Mann= 3 , 0 , 0
9121.414    0.12       09121.414    0.12       010301.65    0.12       0
#XS Ineff= 2 , 0
       09878.244                       0
Bank Sta=9121.414,10301.65
Exp/Cntr=0.3,0.1

Type RM Length L Ch R = 1 ,64387.35,249.153300,249.153300,249.153300
XS GIS Cut Line= 6
611689.302222461748836.312679442611550.686250113748925.471082867
611294.444077618749105.157774276611187.079016179749169.187858009
 610939.90242958749294.972542516610608.621992236749404.512625152
#Sta/Elev= 30
9191.334514.62619291.242 518.3269315.152522.87989327.107519.57429351.017504.6902
9375.333494.40539387.546486.40589411.974481.59919436.401470.0426 9534.11469.6105
9581.778460.52469680.316 457.3859907.904459.59219930.184461.4097 9942.52454.5515
9953.029444.34999964.506438.24389998.934436.303910033.09439.591810044.08446.1344
10071.75471.657710087.48  479.7710214.14509.5782 10256.2511.732410308.77510.7586
10361.33494.411410371.85496.201810392.88506.705510403.39507.872610420.61501.5337
#Mann= 3 , 0 , 0
9191.334    0.12       09191.334    0.12       010420.61    0.12       0
#XS Ineff= 2 , 0
       09897.583                       0
Bank Sta=9191.334,10420.61
Exp/Cntr=0.3,0.1

Type RM Length L Ch R = 1 , 64138.2,249.153400,249.153400,249.153400
XS GIS Cut Line= 6
611693.235051812748778.924914439611373.249466732748924.452098063
611192.126525969748985.406684291611019.155221088749017.399750854
610775.406635999749037.902555485610513.142286059749066.685678399
#Sta/Elev= 30
9208.386511.2956 9338.93518.19339372.053493.55419405.176475.04869427.108473.7965
9448.928467.81889481.659468.3558 9536.21455.8662 9696.18454.30659909.044456.6522
9921.314450.01049931.381440.00839941.417436.96439951.454438.02019961.491434.6045
9971.527436.504710001.63432.6082 10021.7435.120810031.74439.808610041.77449.5171
10051.81455.151810091.95458.261810112.02464.479410132.09473.816710152.16475.4408
10192.35483.575810222.53486.166810282.89497.027710343.25  512.4210435.66 542.523
#Mann= 3 , 0 , 0
9208.386    0.12       09208.386    0.12       010435.66    0.12       0
#XS Ineff= 2 , 0
       09864.764                       0
Bank Sta=9208.386,10435.66
Exp/Cntr=0.3,0.1

Type RM Length L Ch R = 1 ,63889.04,249.153300,249.153300,249.153300
XS GIS Cut Line= 6
611722.970921496748682.637336358611572.437176522 748721.51365298
611462.860270304748742.466553762611262.725075656748764.349214674
610931.019122289748774.920335585 610503.43481569748771.147136048
#Sta/Elev= 30
9200.661505.31719240.097512.54819332.893513.58419394.272480.22059404.453476.1069
9414.634475.55749434.997468.60019445.178466.62749485.745467.53789495.837465.5846
9516.023455.53219526.116452.81429696.863450.43129906.991449.66649916.994447.5877
9926.998443.42969937.001436.77249947.004432.39969957.007430.12589997.019428.6872
10017.02429.240310027.02432.465310047.02447.591410077.02454.266710107.02469.0768
10197.03474.306210277.04483.604710327.05487.265310367.05498.905310428.63521.1638
#Mann= 3 , 0 , 0
9200.661    0.12       09200.661    0.12       010428.63    0.12       0
#XS Ineff= 2 , 0
       09889.208                       0
Bank Sta=9200.661,10428.63
Exp/Cntr=0.3,0.1

Type RM Length L Ch R = 1 ,63639.89,249.153400,249.153400,249.153400
XS GIS Cut Line= 6
 611749.09975425748598.029687392611585.011844271 748614.64093612
611473.466598964748613.962850091611381.580932978748606.386514186
611217.211535812748580.393913868610492.556842599748439.973288629
#Sta/Elev= 30
9191.116497.80639215.527505.08669235.688506.55979255.813511.12819285.999510.8612
9306.063505.9925 9346.14479.20339376.161477.96669416.166465.19359446.178 463.541
9466.187456.2743 9486.25452.33119820.392444.42159912.168444.92739932.563437.0907
9973.353426.780210003.94425.394610024.34427.153110044.73436.257310054.92443.9698
10065.12446.4735 10116.1447.7106 10136.5454.858210156.89464.539210279.23467.1091
10350.41495.473510380.92504.381410411.42 508.56710431.72507.495710464.54501.6365
#Mann= 3 , 0 , 0
9191.116  0.0793       09191.116  0.0793       010464.54  0.0793       0
#XS Ineff= 2 , 0
       0 9890.24                       0
Bank Sta=9191.116,10464.54
Exp/Cntr=0.3,0.1

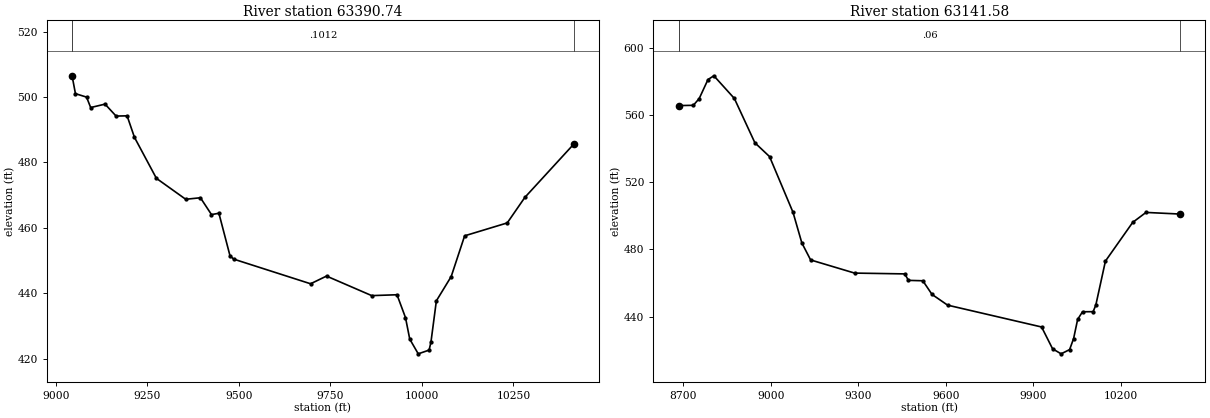
Type RM Length L Ch R = 1 ,63390.74,249.153300,249.153300,249.153300
XS GIS Cut Line= 6
611944.056053465748496.956704149 611633.57144509748517.183028764
611394.915680311748470.729771172611199.013751559748387.861610307
610864.038133715748200.182114287  610661.9376247748117.635499295
#Sta/Elev= 30
9044.219506.52489053.438501.0553 9083.82499.99569095.055496.80399134.313 497.853
9164.481494.19659194.585494.26899214.654487.69669274.688475.13979354.743468.7346
9394.939469.19959425.165464.05299445.411464.45759475.854451.40899486.072450.4139
9695.957442.87919739.486445.23469862.977439.25489932.065439.5211 9955.28432.5228
9966.887425.95239990.101421.440510019.84422.591410024.88425.068110039.61437.6529
10080.16445.098910116.87457.552810233.29461.5017 10281.3469.290210415.31485.6464
#Mann= 3 , 0 , 0
9044.219  0.1012       09044.219  0.1012       010415.31  0.1012       0
#XS Ineff= 2 , 0
       09884.816                       0
Bank Sta=9044.219,10415.31
Exp/Cntr=0.3,0.1

Type RM Length L Ch R = 1 ,63141.58,249.153300,249.153300,249.153300
XS GIS Cut Line= 6
612425.413333535748454.854234904611756.416593583748384.874005133
611558.001617917748340.261638976611349.888752121748234.217057034
 611050.02527682747980.851272527610858.014539044747881.310576188
#Sta/Elev= 30
8683.547565.66088734.235565.81418754.344569.82278784.508581.15338804.617 583.403
8874.999569.88988945.381543.50528995.654535.2861 9076.09502.10249106.254483.9228
9136.418 473.7749287.236465.94499459.083465.46459471.968461.61139521.107 461.377
9552.624453.25459606.084446.86069928.325433.85979966.004420.87449995.277417.8764
10024.37420.397710038.12426.9753 10051.9438.357610068.61442.916710105.04 442.976
 10114.3446.924310147.21473.085810240.72496.126710286.32502.059310404.01501.0796
#Mann= 3 , 0 , 0
8683.547    0.06       08683.547    0.06       010404.01    0.06       0
#XS Ineff= 2 , 0
       09893.431                       0
Bank Sta=8683.547,10404.01
Exp/Cntr=0.3,0.1