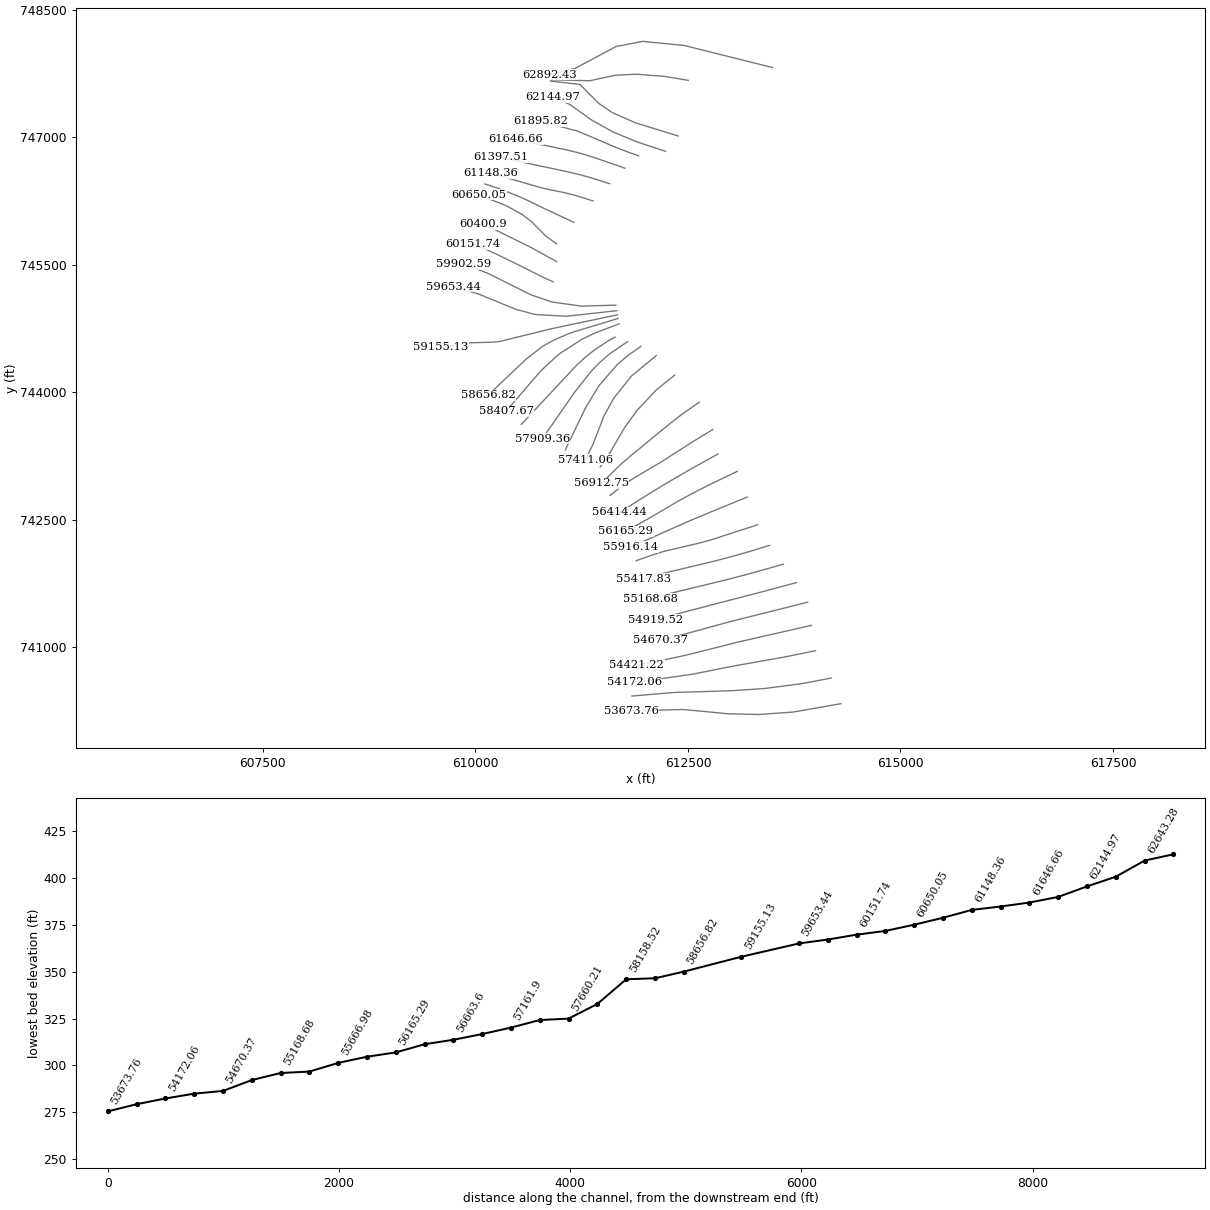
HEC-RAS study 3120_ras.prj: 3120

--- 3120_ras.g01 (geometry) --- (continued)

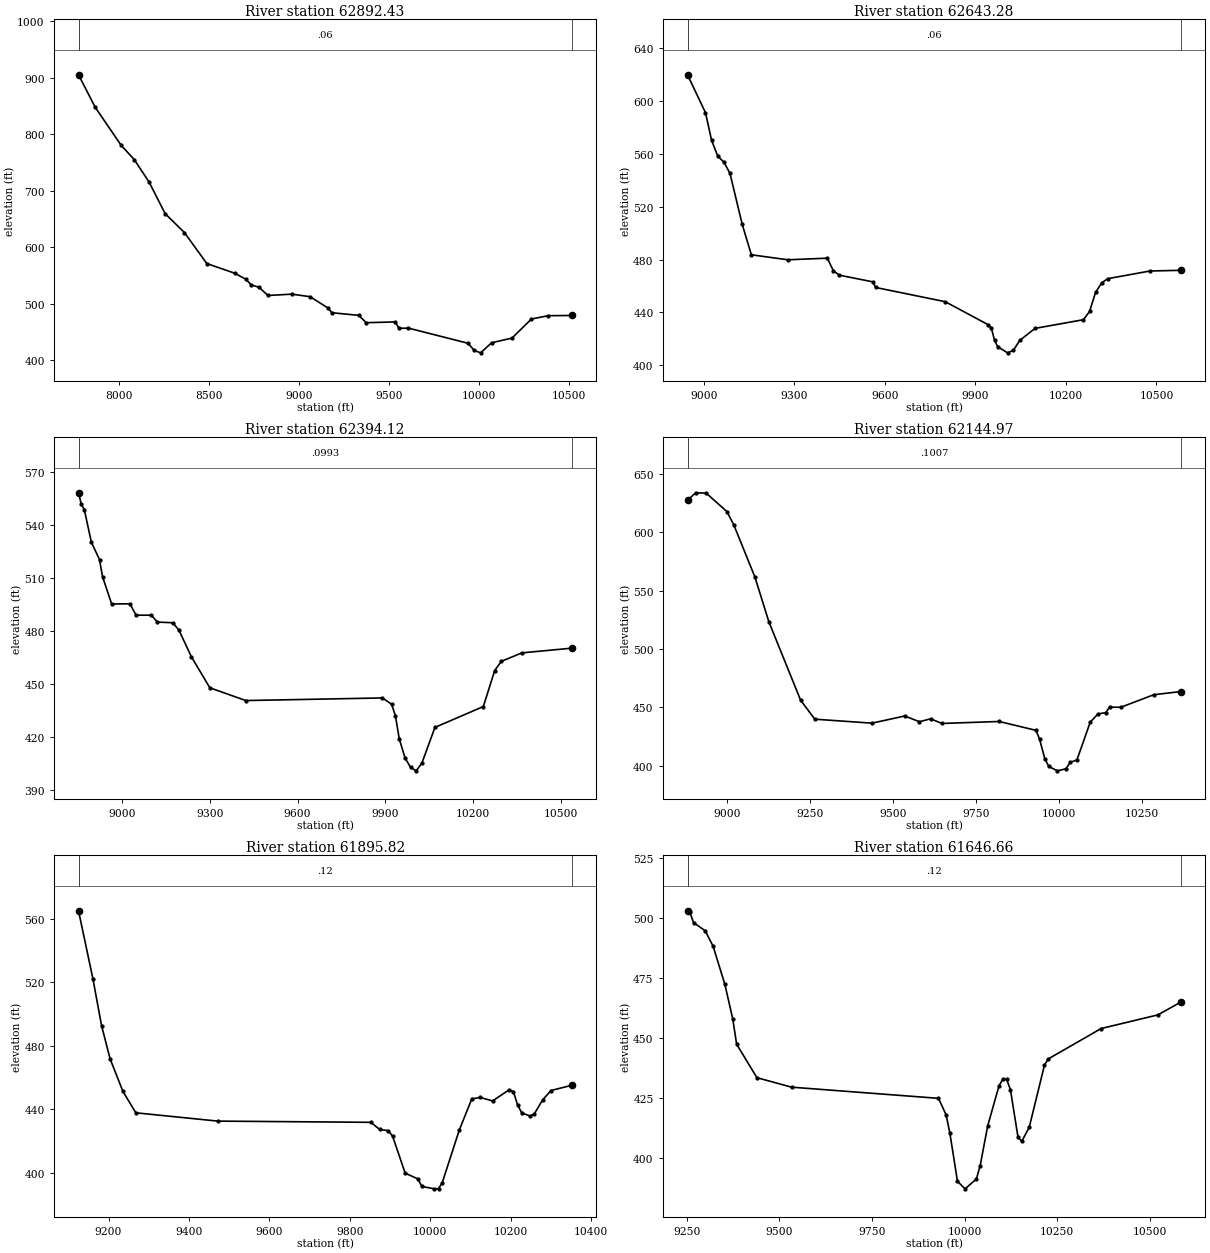
Type RM Length L Ch R = 1 ,62892.43,249.153400,249.153400,249.153400
XS GIS Cut Line= 6
613495.211885492747818.121468979612455.660900866748078.149471447
611968.804791687748126.281270178611653.827025295748065.657178308
611173.212642922747808.742120824610875.856433522747733.327804304
#Sta/Elev= 30
7775.765905.19557868.535847.60198012.671780.17688084.895 755.1728167.527715.1764
8256.581 659.3358363.899625.69338487.923570.89168642.908553.7886 8704.61543.1056
8735.461532.87578776.449529.12828827.634514.3643 8960.01516.73029061.102 512.218
9161.615491.99189181.667483.87769331.754479.1802 9371.85466.21539533.877467.5284
9554.424456.20979606.142456.65739937.374429.78229972.636416.9989 10007.9 412.811
10068.25430.609310181.71  438.9210289.33472.615410382.42 478.60810513.59478.9437
#Mann= 3 , 0 , 0
7775.765    0.06       07775.765    0.06       010513.59    0.06       0
#XS Ineff= 2 , 0
       09870.414                       0
Bank Sta=7775.765,10513.59
Exp/Cntr=0.3,0.1

Type RM Length L Ch R = 1 ,62643.28,249.153300,249.153300,249.153300
XS GIS Cut Line= 6
612503.438436161747667.682599141612217.740917886747715.269055272
611886.451988492747739.914828263611645.465331529747727.789492389
611346.295783886747663.039789916610882.931405258 747674.64715636
#Sta/Elev= 30
8946.184619.78069005.714591.13559026.032570.19769046.351558.23289066.669553.7731
9086.936545.1849 9127.39506.7154 9157.73483.62289278.864479.84989409.497481.0705
9429.545471.48899449.592468.19629559.693463.17799569.697458.90399800.111448.1477
 9942.62430.71639953.032428.11339963.443 419.0199973.854414.074410006.92409.4675
10025.98411.391610046.84418.823510097.83 427.96910258.15 434.534 10278.2440.7373
10298.25455.1809 10318.3462.335810338.34465.560910478.35471.357810580.47471.8949
#Mann= 3 , 0 , 0
8946.184    0.06       08946.184    0.06       010580.47    0.06       0
#XS Ineff= 2 , 0
       09889.997                       0
Bank Sta=8946.184,10580.47
Exp/Cntr=0.3,0.1

Type RM Length L Ch R = 1 ,62394.12,249.153400,249.153400,249.153400
XS GIS Cut Line= 6
612384.086367197747013.146657149611887.288600316747166.600463778
611605.045012306747290.739580951611448.831007396747398.500198757
611230.468240117747619.060094427610884.824134512 747658.94863725
#Sta/Elev= 30
8851.951558.37658861.387551.86168871.772548.82288895.893530.35038923.697520.4939
8934.082510.74778965.237495.35849027.554495.4808 9048.46489.01429100.727489.0111
9121.634485.10439173.901484.74059194.914480.5891 9237.16465.5769 9300.53447.8758
9423.374440.65629890.172442.13569921.574438.53099934.544431.92439947.513419.0058
9967.392408.1211 9986.18402.762810005.26400.830210024.81405.175810069.49425.4494
10234.72437.261310273.51457.619510295.97462.860210366.49467.669810536.82470.3335
#Mann= 3 , 0 , 0
8851.951  0.0993       08851.951  0.0993       010536.82  0.0993       0
#XS Ineff= 2 , 0
       09904.015                       0
Bank Sta=8851.951,10536.82
Exp/Cntr=0.3,0.1

Type RM Length L Ch R = 1 ,62144.97,249.153300,249.153300,249.153300
XS GIS Cut Line= 6
612238.695226032746832.509178779611910.027363648746940.220818527
611621.364728381 747059.33140207611365.753598107 747201.32559656
611109.236794895747384.777571882610907.667435897747469.483608074
#Sta/Elev= 30
8881.002627.45288905.762633.7469 8937.11633.47088999.809617.63989020.846606.0006
 9083.97561.64759126.336523.10239221.659456.18469264.415439.88059436.707436.4706
9535.301442.60519579.797 437.6769613.213440.20019647.369436.21579819.884437.9078
9930.702430.31489941.448422.86079957.322406.09059969.331399.43479995.083395.6457
10021.12397.398310033.42402.809610054.21405.0361 10094.2437.347610117.57444.3736
10140.93 445.52510152.45450.200110186.43450.077110285.51460.821510366.91463.5152
#Mann= 3 , 0 , 0
8881.002  0.1007       08881.002  0.1007       010366.91  0.1007       0
#XS Ineff= 2 , 0
       09908.724                       0
Bank Sta=8881.002,10366.91
Exp/Cntr=0.3,0.1

Type RM Length L Ch R = 1 ,61895.82,249.153400,249.153400,249.153400
XS GIS Cut Line= 6
611919.012212795746780.028108888611819.870818437746814.713812861
 611614.33614004746894.791751412611281.980162458747037.698040858
611189.289188521747073.390754338610764.729116781747186.784285677
#Sta/Elev= 30
9125.418564.98679161.452521.89479182.641492.79199203.829 471.895 9235.68451.4249
9267.876437.86619472.083 432.642 9852.44431.88149873.871 427.4179895.303426.6387
9906.019423.28599937.516399.89469968.861396.30779979.219391.528110010.19390.0328
10020.51390.160310029.55393.8384 10072.1427.049510103.12446.638410123.84447.5269
10154.92445.354810196.35452.425810206.71451.100410217.07442.722810227.43437.8036
10248.15435.821410258.51 437.20510279.23445.985910299.93451.899710351.64 455.196
#Mann= 3 , 0 , 0
9125.418    0.12       09125.418    0.12       010351.64    0.12       0
#XS Ineff= 2 , 0
       0 9883.15                       0
Bank Sta=9125.418,10351.64
Exp/Cntr=0.3,0.1

Type RM Length L Ch R = 1 ,61646.66,249.153300,249.153300,249.153300
XS GIS Cut Line= 6
611760.369166752746633.325937272 611429.74949892746748.508124436
611311.163954236746786.931001002611228.304509136746811.288372307
611065.900294522746851.410637847610474.152038837 746972.67485983
#Sta/Elev= 30
9251.659502.98279257.344502.64699267.934498.07419299.702494.61339320.881488.1593
 9352.65472.25649373.829457.92229384.418447.32499439.124433.38629532.671429.4224
9929.695424.76729950.225417.88779960.489410.19739981.015390.139110001.46387.0236
10032.09391.1292 10042.3396.744710062.73413.346210093.36430.075310103.57432.7346
10113.78432.711310123.99428.407610144.41408.651410154.62406.806610175.04 412.808
10215.88438.585710226.09441.190410369.04453.8749 10522.2459.560610584.15 464.883
#Mann= 3 , 0 , 0
9251.659    0.12       09251.659    0.12       010584.15    0.12       0
#XS Ineff= 2 , 0
       09884.653        10101.42       0
Bank Sta=9251.659,10584.15
Exp/Cntr=0.3,0.1

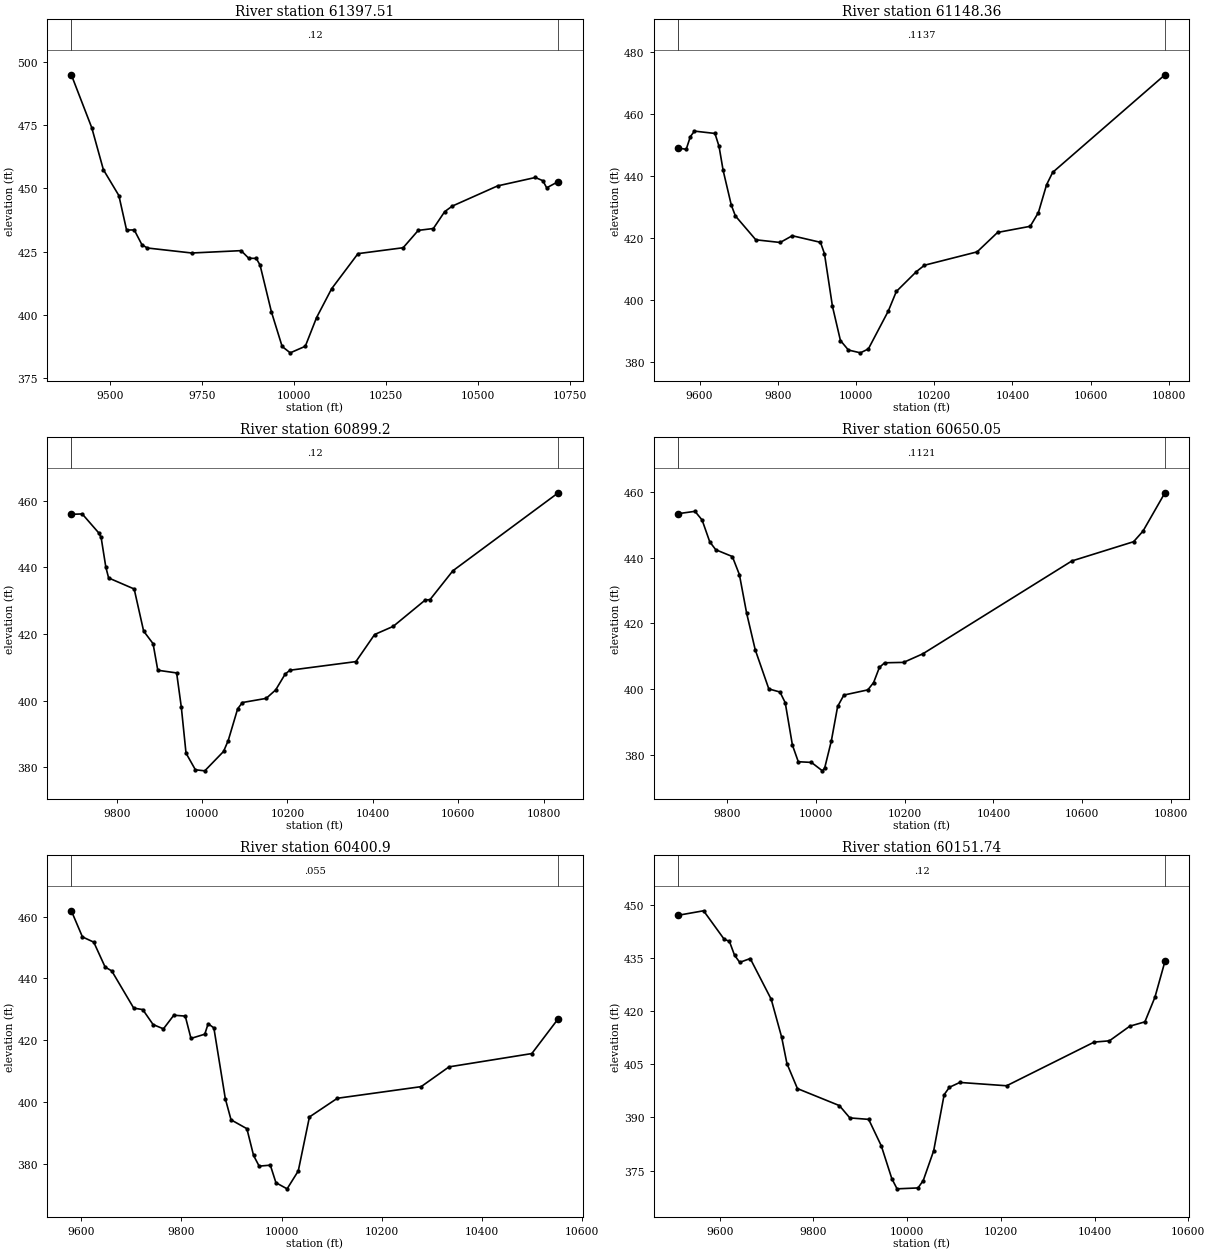
Type RM Length L Ch R = 1 ,61397.51,249.153400,249.153400,249.153400
XS GIS Cut Line= 6
 611577.75347518746452.883064044611347.184200347746525.185256585
611237.246470599746555.503006457611066.198178996746596.441218365
610700.447749987746673.102159531610294.203703864746764.886713432
#Sta/Elev= 30
9395.631494.99479451.098474.03189482.641457.41369524.663447.18149545.555433.5419
9566.446433.55369587.338427.6781 9602.04 426.4119722.536424.4311 9856.46425.3647
9877.025422.3628 9897.59422.29149907.872419.6559 9938.66401.15299967.851387.4177
9989.807 384.90110030.68 387.49910061.32398.875310102.18 410.28510173.68 424.177
10296.25426.515610337.25433.385310378.26434.128910409.02 440.80710429.53442.9965
10552.56450.995110655.09454.3266 10675.6453.046110685.85450.238610717.39452.7065
#Mann= 3 , 0 , 0
9395.631    0.12       09395.631    0.12       010717.39    0.12       0
#XS Ineff= 2 , 0
       09877.719                       0
Bank Sta=9395.631,10717.39
Exp/Cntr=0.3,0.1

Type RM Length L Ch R = 1 ,61148.36,249.153300,249.153300,249.153300
XS GIS Cut Line= 6
611384.967046697746249.035119161611164.157260776746317.251170028
611040.518087465746348.147871272610859.791413618746384.606892881
 610763.02508885746407.071203148610184.371397138746574.792336407
#Sta/Elev= 30
9544.934449.00499565.982448.59019576.523452.66959587.065454.44439639.446 453.696
9649.887449.53329660.328441.8077 9681.21430.64599691.652427.16119743.858 419.475
9806.115418.61419837.037420.78199909.135418.66349919.342415.01739939.758398.0853
9960.173387.06379980.588384.002310011.19 383.10210031.58384.359610082.56396.5568
10103.06402.845910154.39409.238110174.92 411.287 10309.6 415.59210361.81421.8409
10445.34423.817410466.22428.2422 10487.1437.181810502.69 441.16710789.72472.5726
#Mann= 3 , 0 , 0
9544.934  0.1137       09544.934  0.1137       010789.72  0.1137       0
#XS Ineff= 2 , 0
       09893.611                       0
Bank Sta=9544.934,10789.72
Exp/Cntr=0.3,0.1

Type RM Length L Ch R = 1 , 60899.2,249.153400,249.153400,249.153400
XS GIS Cut Line= 6
611158.092497925745997.590316013610814.467568676746157.936564719
610610.643615827746257.124978408610491.769193011 746310.06250628
610273.487016749 746394.90579516610111.424746958746448.538518789
#Sta/Elev= 30
9693.586455.93029719.137456.03819757.625 450.3739763.396448.98399774.461440.0328
9780.989436.81169840.849433.50029862.978420.85939885.108 417.0759896.173409.0921
9940.341408.28699951.327397.96959962.313384.19129984.284379.199210006.23378.8835
10050.21384.701710061.21387.989410083.32397.527910094.44399.401510150.05400.6416
10172.29403.175410194.53407.920910205.65 409.09810360.38411.690310404.17419.8271
10447.68422.265910522.87430.193910533.97430.301610587.56438.971110834.54 462.394
#Mann= 3 , 0 , 0
9693.586    0.12       09693.586    0.12       010834.54    0.12       0
#XS Ineff= 2 , 0
       09902.642                       0
Bank Sta=9693.586,10834.54
Exp/Cntr=0.3,0.1

Type RM Length L Ch R = 1 ,60650.05,249.153300,249.153300,249.153300
XS GIS Cut Line= 6
610955.150158708745744.661076695610828.633184936745835.856187018
610657.381032932746007.396851592610547.621677183746091.535214252
610360.625100979746194.312098266 610038.14127244 746321.70173597
#Sta/Elev= 30
9689.166 453.3139727.457454.03489743.532451.39459760.752444.77029774.299442.3633
9811.713440.29889827.595434.79719843.814423.14219863.202412.00249893.903400.0713
9919.017399.13449930.891395.88169947.073383.01769960.292377.95539989.895377.7468
10014.72375.185810019.76376.034210034.74384.2275   10049394.758310063.07398.2087
10117.03 399.78510130.07401.9996 10143.1406.603310154.86408.013910197.58408.1381
10241.16410.751410576.93438.955210716.05444.804610737.19448.015210786.72459.6705
#Mann= 3 , 0 , 0
9689.166  0.1121       09689.166  0.1121       010786.72  0.1121       0
#XS Ineff= 2 , 0
       0                               0
Bank Sta=9689.166,10786.72
Exp/Cntr=0.3,0.1

Type RM Length L Ch R = 1 , 60400.9,249.153300,249.153300,249.153300
XS GIS Cut Line= 6
610954.642773352745536.990938527610905.116691761 745562.99558447
610663.658090464745696.692835981610239.995708969745906.155388735
610128.911874733745956.151487666610086.201979604745973.759538623
#Sta/Elev= 30
9580.191461.88269602.377453.42289624.966451.72929647.693443.66399660.911442.4159
9704.846430.36139722.843429.89439743.486425.0493 9764.13423.65639784.861428.0693
9807.722427.78399819.153420.55859846.705421.92599853.445425.32289864.875423.9574
9887.736401.04199899.167394.19819930.789391.33249944.137382.67349955.305379.2061
9977.641379.52369988.809373.844610011.12371.857610033.42377.642110055.73 395.127
10111.49401.181210278.79404.941110334.55411.347110499.89415.654910552.76426.9637
#Mann= 3 , 0 , 0
9580.191   0.055       09580.191   0.055       010552.76   0.055       0
#XS Ineff= 2 , 0
       0                               0
Bank Sta=9580.191,10552.76
Exp/Cntr=0.3,0.1

Type RM Length L Ch R = 1 ,60151.74,249.153400,249.153400,249.153400
XS GIS Cut Line= 6
610915.233601191745297.507846424 610801.00993063745348.440421057
610474.976942104745512.260542827610237.722683364745627.666272795
610134.184795994745674.396209566609974.963062328745739.114947496
#Sta/Elev= 30
9511.045447.03929565.669448.3174 9609.71440.26699620.721439.71439631.731435.7794
 9642.85433.76219665.233434.83939709.999423.35199732.382412.60679743.573405.1984
9765.956398.14629855.488393.34979877.871389.87229918.001389.4623 9945.02381.9683
9967.403372.73749978.594369.860810023.29370.116410034.45372.196210056.77380.6192
10079.09396.432810090.25398.511110112.57399.883610212.43398.944210399.24411.2665
10431.78411.624210475.17415.7463 10507.5416.9794 10528.9 423.90810550.33434.0464
#Mann= 3 , 0 , 0
9511.045    0.12       09511.045    0.12       010550.33    0.12       0
#XS Ineff= 2 , 0
       0 9861.85                       0
Bank Sta=9511.045,10550.33
Exp/Cntr=0.3,0.1

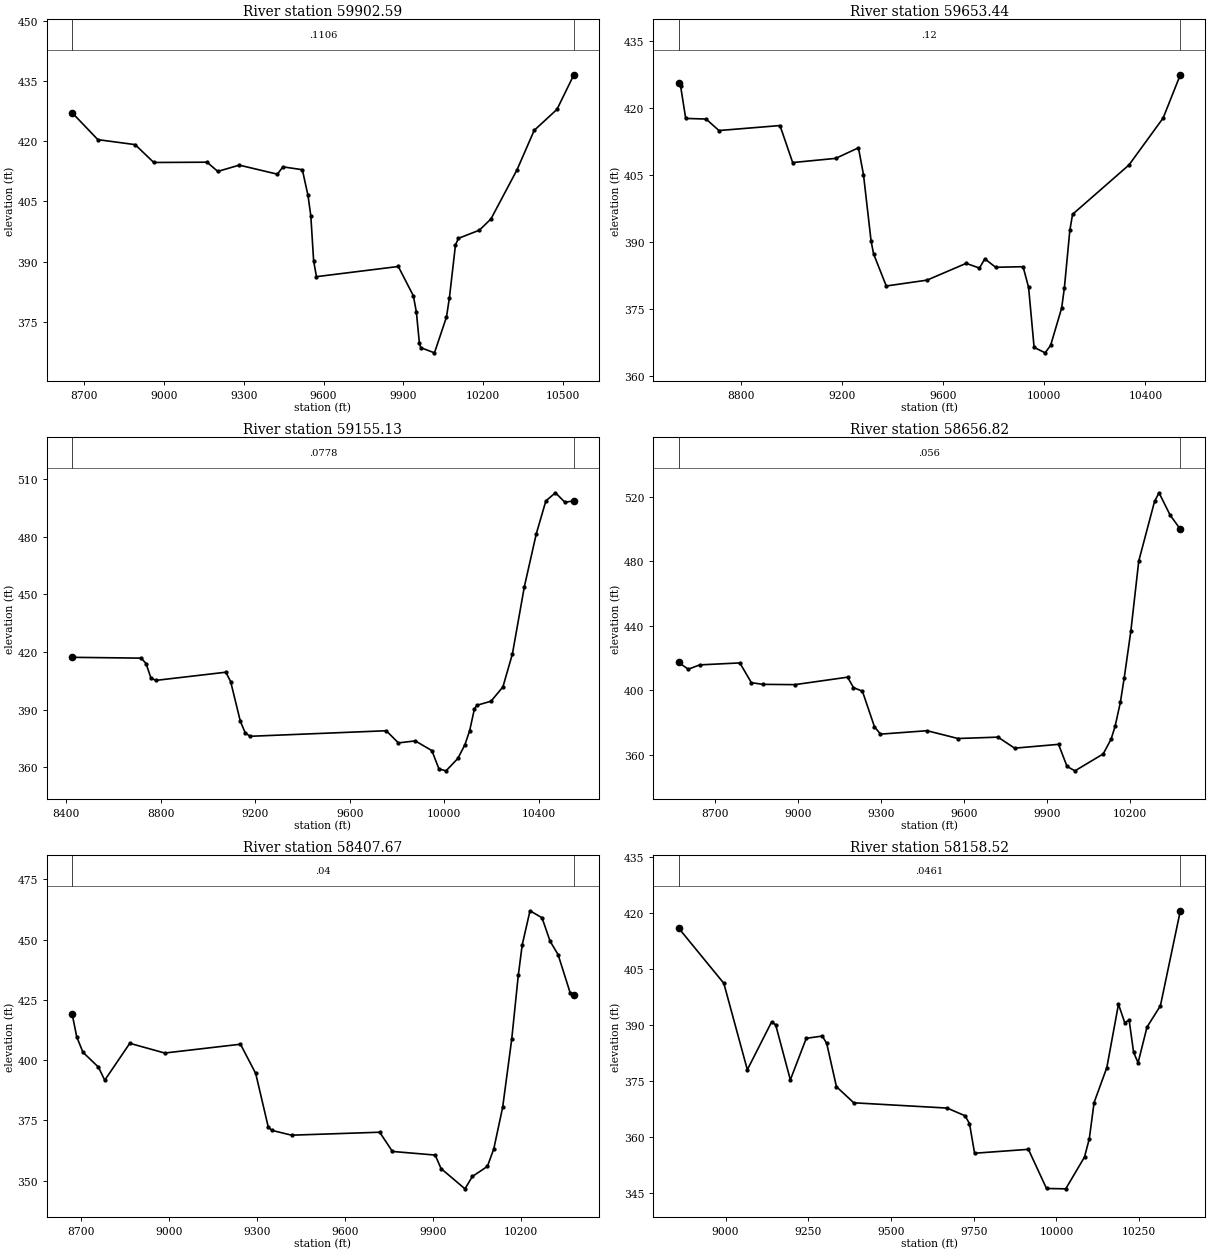
Type RM Length L Ch R = 1 ,59902.59,249.153300,249.153300,249.153300
XS GIS Cut Line= 6
611651.593122231745023.450444014611249.186148208745011.388343197
610896.485659028745061.122556157610655.894724851745143.448126899
610147.267515161745397.240676056609864.939160841745507.033280297
#Sta/Elev= 30
8654.939427.08978751.823420.37328891.956419.12968961.963414.68129162.272 414.755
9202.499412.45469283.292414.02429426.564411.76839447.389413.59699520.357412.8792
9541.579406.4679 9552.19401.40529562.801390.16569573.412386.23859880.968388.7735
9937.644381.4597 9948.98 377.3799960.315369.60229965.463368.5431 10016.9367.2641
10061.99376.170710073.09380.982910095.81394.129110107.08395.787310185.74397.8254
10229.15400.615110327.27412.873410391.72422.681610477.42427.922210540.76436.5299
#Mann= 3 , 0 , 0
8654.939  0.1106       08654.939  0.1106       010540.76  0.1106       0
#XS Ineff= 2 , 0
       09865.382                       0
Bank Sta=8654.939,10540.76
Exp/Cntr=0.3,0.1

Type RM Length L Ch R = 1 ,59653.44,498.306700,498.306700,498.306700
XS GIS Cut Line= 6
611663.038803235 744957.95571382611075.927047361744892.699981644
610704.452823474744912.502381758610477.536236974744973.025447916
610034.739979892745154.884498584609738.816267951 745240.99280311
#Sta/Elev= 30
8552.318425.66288560.462424.91968580.722417.66758661.644417.52668712.146414.9534
8953.852416.07059004.031407.78069174.327  408.729264.341411.08379284.342405.0711
9314.364390.22559324.373 387.3129374.461380.13699535.902381.44969690.674385.2093
9743.303 384.1499764.582 386.2149807.411384.32769915.998384.45879937.795379.8225
9959.592366.397110003.21365.166610025.06366.853210068.61375.192410079.42379.7064
10101.03392.612210111.84396.191510335.04407.236410470.25417.749910538.32 427.441
#Mann= 3 , 0 , 0
8552.318    0.12       08552.318    0.12       010538.32    0.12       0
#XS Ineff= 2 , 0
       09875.293                       0
Bank Sta=8552.318,10538.32
Exp/Cntr=0.3,0.1

Type RM Length L Ch R = 1 ,59155.13,498.306700,498.306700,498.306700
XS GIS Cut Line= 6
611671.471474357744909.702095733610892.401726099744745.069563591
610286.622255197744595.946865145610205.128023421744586.618395659
609942.221082259744581.146035817609588.093871692744530.104990936
#Sta/Elev= 30
8424.906417.19278717.704416.76858737.849413.95288758.587406.44118779.029405.1716
9075.433409.42989095.875404.57499136.758383.9747  9157.2377.95939177.641376.0584
9754.292378.95179805.773372.61899877.143373.66389947.354368.60459977.356359.0753
10007.36358.068510057.36364.513410087.37371.709410107.39379.040210127.41390.3116
10137.44392.192210197.66394.327610248.03401.779710288.33419.0375 10338.7453.9479
10389.31481.554310429.82498.672310470.34502.886610510.85497.906110548.23498.7098
#Mann= 3 , 0 , 0
8424.906  0.0778       08424.906  0.0778       010548.23  0.0778       0
#XS Ineff= 2 , 0
       09698.401                       0
Bank Sta=8424.906,10548.23
Exp/Cntr=0.3,0.1

Type RM Length L Ch R = 1 ,58656.82,249.153400,249.153400,249.153400
XS GIS Cut Line= 6
611679.000222232744866.620927336611127.670212198744699.445149896
610931.697361212744616.710678079610791.723472346744539.613603439
610588.888307007  744381.3543724610147.848043929743962.181416947
#Sta/Elev= 30
8567.041 417.2928602.234413.02978643.638415.72948788.812  416.94 8830.47404.7041
8872.226403.66768987.725403.48169178.438408.10869199.893401.66749232.208399.4065
9275.646377.48429297.445372.83349466.078  374.969577.819370.13229722.693370.9787
9782.843364.14419941.662366.51779972.447 352.83310001.01350.108410103.25360.5877
10131.83369.797810146.12377.568210165.38392.612610179.38407.818910203.29436.7086
10231.87 480.06810289.03516.969810305.09522.306710345.57508.414110382.21499.7431
#Mann= 3 , 0 , 0
8567.041   0.056       08567.041   0.056       010382.21   0.056       0
#XS Ineff= 2 , 0
       09879.106                       0
Bank Sta=8567.041,10382.21
Exp/Cntr=0.3,0.1

Type RM Length L Ch R = 1 ,58407.67,249.153300,249.153300,249.153300
XS GIS Cut Line= 6
 611690.09925281744803.109807915611413.672221819744698.050433741
611251.534802554744620.664146535610979.385233156744445.003232021
610771.706827275744252.477656842610361.051838653743776.112650632
#Sta/Elev= 30
8667.892419.29298683.854409.64358704.996403.26528757.974397.08258779.341391.6436
8864.869406.97628984.216402.94299242.699406.60049294.661394.46219337.261372.3279
9349.225370.85039417.167 368.8389717.763370.06749761.226362.08549907.205360.5794
9927.207354.983110008.91346.562810034.14 351.69410085.45355.894210107.15 363.121
10137.49380.414910168.44408.714410190.81435.166310204.14447.769210230.81461.9989
 10271.8459.101910299.24449.406210326.68443.800610367.94427.9163 10380.5427.1719
#Mann= 3 , 0 , 0
8667.892    0.04       08667.892    0.04       0 10380.5    0.04       0
#XS Ineff= 2 , 0
       09888.762                       0
Bank Sta=8667.892,10380.5
Exp/Cntr=0.3,0.1

Type RM Length L Ch R = 1 ,58158.52,249.153300,249.153300,249.153300
XS GIS Cut Line= 6
  611643.6267963744647.466965932611551.385157473 744595.85459511
611401.443811292744496.922554481611285.352228812744404.364107975
611195.115540106744321.197023451610539.493991708743620.381317048
#Sta/Elev= 30
8857.982415.87288994.832 401.0579065.918377.9165 9139.04390.6791 9151.49389.9642
9195.873 375.208 9244.01386.32869292.357386.92829305.695384.99799335.206373.3778
9387.553 369.0659669.953367.65069723.808365.58879737.272363.50549752.718 355.563
9915.319356.60629970.047346.125210028.22346.029410084.99354.559910099.44359.4663
10113.89369.137910152.33 378.47710187.59395.450810206.31390.558710219.81391.1854
 10233.3382.5506 10246.8379.791710273.79389.326910314.28395.035610374.49420.4715
#Mann= 3 , 0 , 0
8857.982  0.0461       08857.982  0.0461       010374.49  0.0461       0
#XS Ineff= 2 , 0
       09886.315                       0
Bank Sta=8857.982,10374.49
Exp/Cntr=0.3,0.1

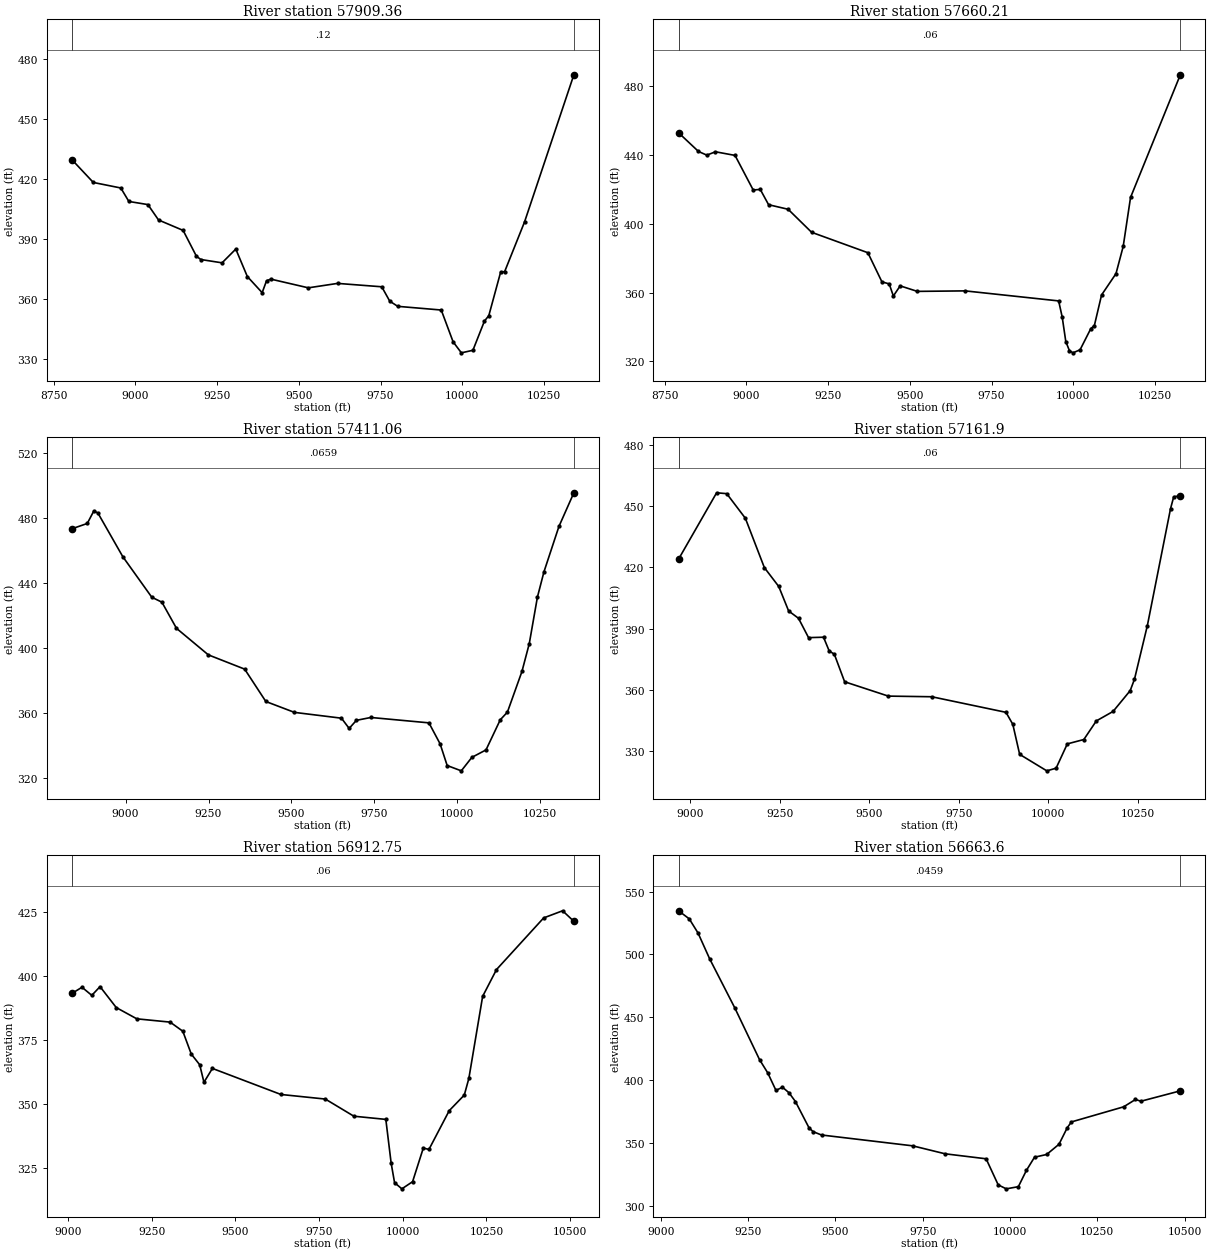
Type RM Length L Ch R = 1 ,57909.36,249.153400,249.153400,249.153400
XS GIS Cut Line= 6
611790.665247248744594.369747535611582.735839578744453.289771035
611459.595797097744346.021574903611365.583257248744249.161968519
611171.053400555744004.190900032 610787.23623927743452.571752172
#Sta/Elev= 30
8806.295429.5952 8871.26418.25868955.367415.48678980.019408.73159038.239407.1636
9070.743399.44949146.021394.21939186.696381.26589200.254379.6232 9265.11377.9655
9307.091384.85949342.352371.10719387.755363.00959401.154368.97959414.329369.7956
9529.029365.43549618.388 367.6559753.578365.95739777.995358.75059802.412356.1542
9935.531354.3058 9971.81338.36139997.089332.842910032.39334.123610067.73348.8011
10080.92351.444410117.31373.381610129.45373.550410190.23398.433110341.16  472.24
#Mann= 3 , 0 , 0
8806.295    0.12       08806.295    0.12       010341.16    0.12       0
#XS Ineff= 2 , 0
       09879.456                       0
Bank Sta=8806.295,10341.16
Exp/Cntr=0.3,0.1

Type RM Length L Ch R = 1 ,57660.21,249.153300,249.153300,249.153300
XS GIS Cut Line= 6
611947.379468773744537.778500874611806.276351762744440.952645183
611669.484759436744324.530200385611456.554620758744080.444173965
611297.538594854743819.371395848611057.128022744743320.944202041
#Sta/Elev= 30
8792.485453.01348853.545442.11348878.993 439.9838905.419441.93818965.324439.8261
 9020.86419.71229042.486420.04559067.925411.15439127.721408.49539199.498395.1114
9371.618383.22829414.607366.28179436.844365.10039449.593358.06019470.488 363.949
 9522.83360.74139669.124361.03329955.176355.19549966.111345.75299977.046331.5864
9987.981326.33519998.916324.996510020.75326.777510053.51339.068710064.43340.8811
10086.47358.6518 10130.6371.066210152.66386.923610175.08415.369610327.37486.7218
#Mann= 3 , 0 , 0
8792.485    0.06       08792.485    0.06       010327.37    0.06       0
#XS Ineff= 2 , 0
       0 9887.16                       0
Bank Sta=8792.485,10327.37
Exp/Cntr=0.3,0.1

Type RM Length L Ch R = 1 ,57411.06,249.153400,249.153400,249.153400
XS GIS Cut Line= 6
612128.330124214744431.014105805611834.188948319744187.442385997
611623.531104086743922.807451221611511.069088149743717.537843317
611380.888610492743381.230361943611293.250556552743205.786081051
#Sta/Elev= 30
8838.574473.5753 8884.41476.82638903.716 484.3798916.083483.40098991.371 456.379
9078.927431.31459109.351428.27299153.345412.14119249.297395.77949358.816386.9813
9422.683367.01049508.844360.29839650.626356.71269673.798350.40559695.693 355.396
9739.225357.15429914.244353.83979947.968 340.885 9969.26327.510710011.82324.2394
10043.71 332.553 10086.3337.147710129.32355.726310150.84360.450210194.72385.5663
 10216.7402.664310241.33431.4249   10261446.994110306.19474.996210351.15 495.755
#Mann= 3 , 0 , 0
8838.574  0.0659       08838.574  0.0659       010351.15  0.0659       0
#XS Ineff= 2 , 0
       09894.504                       0
Bank Sta=8838.574,10351.15
Exp/Cntr=0.3,0.1

Type RM Length L Ch R = 1 , 57161.9,249.153300,249.153300,249.153300
XS GIS Cut Line= 6
612341.985746354 744198.82712869612126.902807452 744024.45131168
611902.087905501 743785.49107625611758.317046424 743587.44314014
611580.400060288743283.756794978611469.059439095743120.043224405
#Sta/Elev= 30
8968.022424.05989074.326 456.6569102.512456.22659154.454444.16899207.501419.9404
9247.707410.66499275.252398.65799302.797395.06249330.807385.57029372.634385.7689
9388.447379.03039402.797377.42449431.499363.90889553.445356.87239674.724356.5562
  9881.8 348.9099900.871343.01299919.941328.28069995.665320.196510021.61321.4906
10052.92333.424410099.03335.562910133.93344.693510180.74349.362410228.48359.5771
10240.42 365.191 10276.3391.468910340.99448.868210349.86454.666910368.31455.2215
#Mann= 3 , 0 , 0
8968.022    0.06       08968.022    0.06       010368.31    0.06       0
#XS Ineff= 2 , 0
       09912.149                       0
Bank Sta=8968.022,10368.31
Exp/Cntr=0.3,0.1

Type RM Length L Ch R = 1 ,56912.75,249.153400,249.153400,249.153400
XS GIS Cut Line= 6
612633.979771771743881.507090872612433.361678528743741.588414401
612287.138023007743628.805691669 611808.70771778743235.680520851
611698.806659573 743140.35993795611481.237864783742926.013131743
#Sta/Elev= 30
9011.796393.17939041.464395.55379070.742392.38869095.382395.80339143.834387.6166
9205.259383.21419304.859381.92739342.746378.35899368.004369.43889393.262365.2427
9405.891358.40279431.148 363.8259635.927353.64079768.613351.84519853.844345.1433
9949.383343.89759965.347326.73849975.475319.17369997.274316.747410029.33319.5387
10061.39332.701710078.21332.148710138.88 347.31910183.88353.412210197.52359.9296
10238.69391.994910280.09402.470810421.06422.666710477.65425.455210511.27 421.329
#Mann= 3 , 0 , 0
9011.796    0.06       09011.796    0.06       010511.27    0.06       0
#XS Ineff= 2 , 0
       09914.319                       0
Bank Sta=9011.796,10511.27
Exp/Cntr=0.3,0.1

Type RM Length L Ch R = 1 , 56663.6,249.153300,249.153300,249.153300
XS GIS Cut Line= 6
612793.165264702  743560.4378155612548.876517197743411.215904726
 612193.71335106743183.918830572611839.561127562742973.408830989
611707.609709858742881.895925231611583.788824219742785.371815928
#Sta/Elev= 30
 9050.31534.70569080.914528.32269106.092517.07679139.486496.51569211.756457.3646
9282.332416.41519305.858  405.87  9329.4391.95449348.117394.45729366.669390.0923
 9385.22383.06689424.296362.11869436.169359.09769459.914356.4856 9721.11347.8728
 9814.05341.53819931.512 337.5749966.128316.83849989.205313.690310023.89315.4089
10047.05328.4186 10070.2338.839110104.94340.995510140.29349.113110163.87362.2245
10175.77366.869110325.56378.885110359.35384.710410375.15383.3362 10487.9391.5805
#Mann= 3 , 0 , 0
 9050.31  0.0459       0 9050.31  0.0459       0 10487.9  0.0459       0
#XS Ineff= 2 , 0
       09882.113                       0
Bank Sta=9050.31,10487.9
Exp/Cntr=0.3,0.1

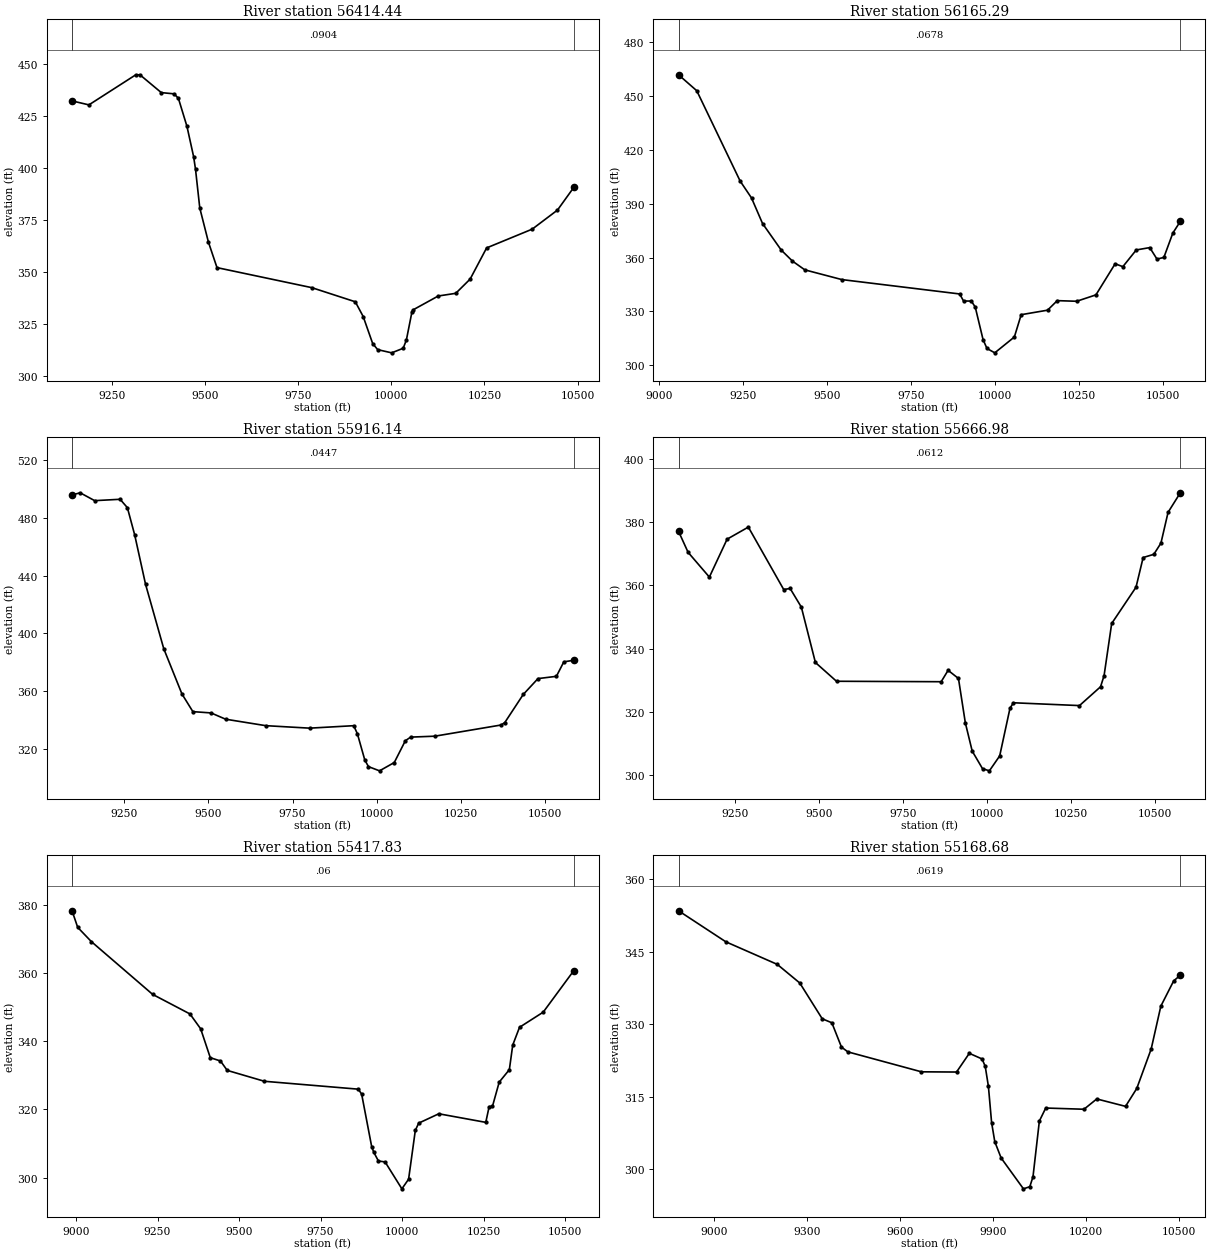
Type RM Length L Ch R = 1 ,56414.44,249.153400,249.153400,249.153400
XS GIS Cut Line= 6
612854.786049095743272.874154949612548.217628081743103.058812457
612321.780452864742971.758431013 612111.22823922742845.687686214
611937.042288079742738.090291365611698.101383403742584.520666441
#Sta/Elev= 30
9143.467432.38359188.671430.4828 9314.07444.89639325.543444.94879382.905436.3753
9417.323435.78429428.795433.6136 9451.74420.14779469.576 405.6189474.685399.5583
9486.158380.90019509.218364.58989532.337 352.2559786.903 342.6229903.455335.8324
 9924.59328.75649950.075 315.7539963.525312.8329   10001311.296310031.93313.4899
10040.46317.450510055.44330.984410059.49332.055910125.96338.612810172.98339.9051
10211.56346.7411 10255.8361.728410378.13370.751410445.95379.917710489.88390.8651
#Mann= 3 , 0 , 0
9143.467  0.0904       09143.467  0.0904       010489.88  0.0904       0
#XS Ineff= 2 , 0
       09866.218        10112.17       0
Bank Sta=9143.467,10489.88
Exp/Cntr=0.3,0.1

Type RM Length L Ch R = 1 ,56165.29,249.153300,249.153300,249.153300
XS GIS Cut Line= 6
613080.722973105743068.261791448612732.138332558742900.137120902
 612549.67966176742806.871759208612403.020684253742727.559275706
612029.216550744742508.144251853611765.497308786742361.151313768
#Sta/Elev= 30
9056.733461.93469110.994453.04179240.167402.68489274.037393.25789306.853379.0146
9362.566364.19269395.994358.05129432.728353.17689542.924 347.7549893.776339.7397
9905.299 335.8179928.503335.76959940.139332.44049963.412314.30699975.048309.3537
 9998.32306.913210056.61315.740210076.97328.184910155.44330.696910184.37 336.017
10242.17335.663710299.48339.229910356.72356.577410379.62354.949610419.63364.2794
10459.75365.581610481.25359.181810501.79360.109810528.45373.675310550.77380.2053
#Mann= 3 , 0 , 0
9056.733  0.0678       09056.733  0.0678       010550.77  0.0678       0
#XS Ineff= 2 , 0
       09859.402        10134.96       0
Bank Sta=9056.733,10550.77
Exp/Cntr=0.3,0.1

Type RM Length L Ch R = 1 ,55916.14,249.153400,249.153400,249.153400
XS GIS Cut Line= 6
613197.264415217742764.741771896 613111.14679375742730.244969503
612748.669131068742581.989091849612501.187892476742477.586892277
611875.949247063742199.760258825 611827.97999682 742177.51453769
#Sta/Elev= 30
9095.113495.85159119.097497.38849162.187491.92729237.741492.88299259.349487.0707
9280.984468.26789313.369433.9129 9367.39389.2891 9421.41357.91559453.823345.6752
9507.843 344.782 9551.06340.43099670.317335.95249800.558334.22689931.515335.9352
9942.462  330.279964.357312.15229975.304307.552410008.14304.638110051.91310.4015
10084.73325.487710100.48328.016710172.27328.656810369.21336.416910380.15338.1316
10434.86357.575610478.63368.578610533.34370.153610555.39380.210710585.17 381.284
#Mann= 3 , 0 , 0
9095.113  0.0447       09095.113  0.0447       010585.17  0.0447       0
#XS Ineff= 2 , 0
       0 9882.97        10143.21       0
Bank Sta=9095.113,10585.17
Exp/Cntr=0.3,0.1

Type RM Length L Ch R = 1 ,55666.98,249.153300,249.153300,249.153300
XS GIS Cut Line= 6
 613321.92006986742440.089132896 612786.17623439742266.504606018
612639.211019711742225.488935179 612221.05692301742127.507655489
612089.558421576742087.146070041611890.898467235742016.517275159
#Sta/Elev= 30
9080.972377.12139109.398370.47569172.753362.6344 9225.55374.63279288.767378.4567
9394.004358.70629413.166359.02699446.544353.13619488.409335.60539551.207329.6662
9862.841329.52299883.426333.13379914.289330.54829934.735316.5056 9955.18307.5704
9985.848302.009210006.29301.320110036.98306.039710067.66321.135210077.89322.8619
10274.49321.970110337.25327.927110347.71331.430410370.37347.947510442.84359.4349
10464.03368.822510495.81369.8367   10517373.381810538.24383.126610574.72 389.315
#Mann= 3 , 0 , 0
9080.972  0.0612       09080.972  0.0612       010574.72  0.0612       0
#XS Ineff= 2 , 0
       09895.825        10157.01       0
Bank Sta=9080.972,10574.72
Exp/Cntr=0.3,0.1

Type RM Length L Ch R = 1 ,55417.83,249.153300,249.153300,249.153300
XS GIS Cut Line= 6
613461.483083803 742196.99297138613200.316934615742118.037188022
612982.540627169742056.498520127612830.507882377742016.691953839
612191.938572086741863.781487712611974.941286755741801.466531096
#Sta/Elev= 30
 8987.97378.2654 9005.19373.40759046.978369.23239235.024353.73999349.468347.9988
9382.302343.64079411.818335.16599442.993334.20249463.776331.43889577.606328.2459
9865.677325.93159875.951324.47969906.771309.03639913.369307.38479927.319304.8618
9947.866304.58479999.322296.691510019.91299.521210040.49313.818210050.78 315.963
10112.52318.711210256.59316.194110266.88320.805510277.17320.922210297.75327.9979
10328.88331.655210339.26338.872810360.04344.081710432.74348.527310526.68360.7364
#Mann= 3 , 0 , 0
 8987.97    0.06       0 8987.97    0.06       010526.68    0.06       0
#XS Ineff= 2 , 0
       0 9853.48        10135.95       0
Bank Sta=8987.97,10526.68
Exp/Cntr=0.3,0.1

Type RM Length L Ch R = 1 ,55168.68,249.153400,249.153400,249.153400
XS GIS Cut Line= 6
613621.715881727741975.372283343613211.181313136741860.055458055
612965.269717339741795.502219036612377.501586149741653.117444333
612189.853781721741605.499689803612054.266093679 741568.38683594
#Sta/Elev= 30
8884.839353.50079037.512347.07619203.539342.40189276.176338.54659348.676331.1331
9379.693330.31179410.709325.28119431.387324.28399668.833320.1563 9782.18320.1113
 9823.37323.98469864.479322.82089874.756321.29189885.033317.13399895.311309.6511
9905.588305.69329926.143302.30919998.084295.926110018.64296.371110028.92298.4312
10049.49309.967510070.05312.6584 10193.5312.406510234.77314.538710327.62313.0045
10363.88  316.7110410.39324.882610441.53333.747410482.96338.980610504.46340.1572
#Mann= 3 , 0 , 0
8884.839  0.0619       08884.839  0.0619       010504.46  0.0619       0
#XS Ineff= 2 , 0
       09823.996        10129.54       0
Bank Sta=8884.839,10504.46
Exp/Cntr=0.3,0.1

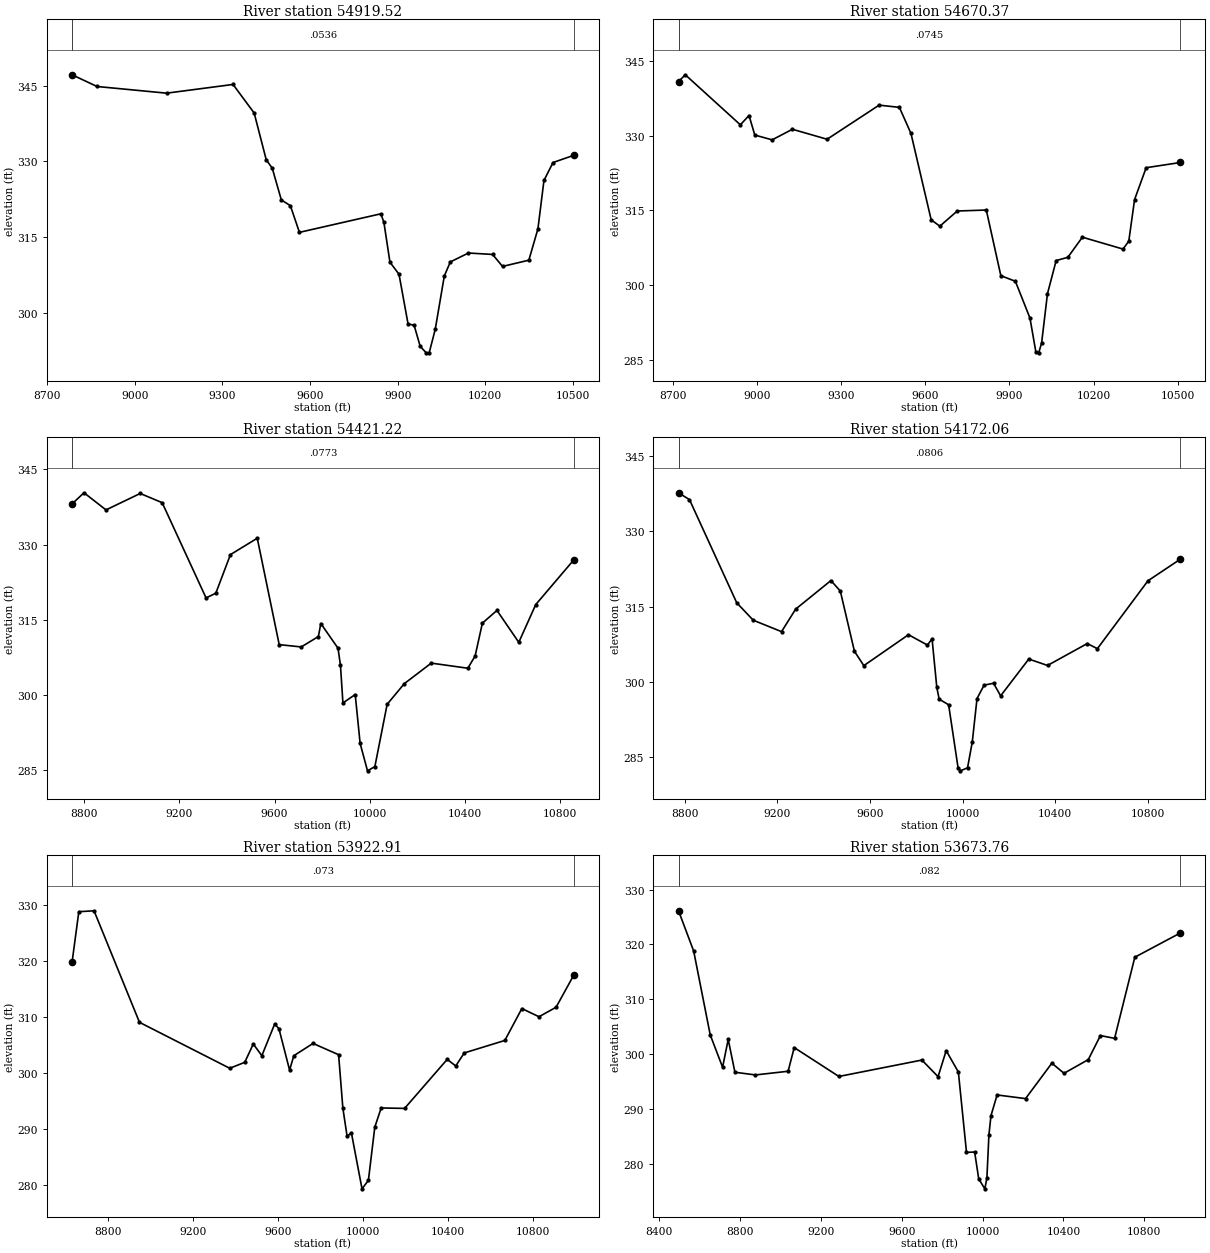
Type RM Length L Ch R = 1 ,54919.52,249.153300,249.153300,249.153300
XS GIS Cut Line= 6
613777.530274897741759.862765516613404.732561012741659.190781231
612783.625036479741498.300213075612603.647707159741451.006930316
612601.713306088741450.498902268612115.956417323741322.996437433
#Sta/Elev= 30
8785.154347.1238 8870.64344.80749108.879343.4881 9336.31345.2117 9408.62339.5611
 9449.94330.3242  9470.6328.64389501.591322.38279532.581321.24839563.571315.9668
9842.509319.63769852.849317.92499873.528310.06769904.546307.68319935.565  297.84
9956.244297.60699976.923 293.4569997.602292.145110007.94292.165410028.62296.7962
10059.63 307.33910080.31310.123410142.34311.882410225.05311.598710258.99309.2314
10349.12310.464610380.14316.655410400.81326.223310431.83 329.77310503.21331.2095
#Mann= 3 , 0 , 0
8785.154  0.0536       08785.154  0.0536       010503.21  0.0536       0
#XS Ineff= 2 , 0
       09805.765        10127.43       0
Bank Sta=8785.154,10503.21
Exp/Cntr=0.3,0.1

Type RM Length L Ch R = 1 ,54670.37,249.153400,249.153400,249.153400
XS GIS Cut Line= 6
613908.295620035741529.782738234613734.621715954741484.406211105
612986.265880847741297.276233779612505.280303926741165.076259172
612317.981056724741116.108274919612176.603683947741081.755087962
#Sta/Elev= 30
8720.559340.84968744.636342.21018940.904332.15928971.828334.02878992.444330.0996
9054.291329.13749126.446331.26559250.141329.25899435.683336.11289507.838335.6631
 9549.07330.43459621.225313.06359652.149311.79849714.179314.8438  9817.7 315.038
9869.533301.85269921.448300.71949973.363293.32469994.128286.606610004.51286.3493
10014.89288.319910035.65298.205110066.79304.8951 10108.3 305.536 10160.2309.5823
10304.95307.197110325.62 308.77710346.29317.140310387.53323.539410509.37324.5883
#Mann= 3 , 0 , 0
8720.559  0.0745       08720.559  0.0745       010509.37  0.0745       0
#XS Ineff= 2 , 0
       09787.567        10166.89       0
Bank Sta=8720.559,10509.37
Exp/Cntr=0.3,0.1

Type RM Length L Ch R = 1 ,54421.22,249.153300,249.153300,249.153300
XS GIS Cut Line= 6
613953.829106373 741256.58182027613083.530535606  741058.1962163
612571.123339389740928.258504281612414.799134873740891.431462932
612165.501948964740840.098478758611897.589724164740789.307170089
#Sta/Elev= 30
8749.018338.13268799.195 340.3488891.681336.93229035.441340.20959127.684338.3777
9312.171319.37719353.168320.31739414.663328.01439527.405331.28259619.648310.0606
9712.198309.59999784.255311.67159794.549314.27239866.794309.34719877.124305.9251
9887.454298.42399939.106300.10769959.766290.36519990.757284.888410021.74285.7379
10073.36298.167510145.64302.285610258.77306.372410412.37305.354410442.99307.7779
10473.62314.348510534.88316.885510626.64 310.51810697.89318.0513 10858.1326.9813
#Mann= 3 , 0 , 0
8749.018  0.0773       08749.018  0.0773       0 10858.1  0.0773       0
#XS Ineff= 2 , 0
       09794.122        10234.99       0
Bank Sta=8749.018,10858.1
Exp/Cntr=0.3,0.1

Type RM Length L Ch R = 1 ,54172.06,249.153400,249.153400,249.153400
XS GIS Cut Line= 6
614001.250601083740957.660165154613615.827339419740879.651603313
613014.282257093740773.324113093612573.847055049740685.320742908
612401.992585726740659.080697067611866.641796206740586.856141305
#Sta/Elev= 30
8773.019337.71088820.359336.34469024.467315.78519095.793312.32059217.892310.0457
9278.822314.52939431.147320.22119471.767 318.1329532.698306.14039573.318 303.272
9766.263309.43279847.744307.37899868.124308.59289888.503298.94249898.708296.5991
9939.605295.47589980.501282.88549990.725282.314410021.38282.922710041.82288.0866
10062.26296.724410092.92299.391710133.65299.762610164.15297.253410285.85304.5866
10366.77303.306810538.37307.671910582.12306.654110800.68320.181610940.37324.4817
#Mann= 3 , 0 , 0
8773.019  0.0806       08773.019  0.0806       010940.37  0.0806       0
#XS Ineff= 2 , 0
       09819.498        10297.78       0
Bank Sta=8773.019,10940.37
Exp/Cntr=0.3,0.1

Type RM Length L Ch R = 1 ,53922.91,249.153300,249.153300,249.153300
XS GIS Cut Line= 6
614186.019020181740636.381569211 613847.96545826740571.713527159
613406.938651368740513.713456137613015.148766261740487.141045386
612346.627544752740466.975072223611841.920208949740425.135757947
#Sta/Elev= 30
8633.277319.81318664.975 328.8568736.455329.0231 8950.01309.05439374.046300.8319
9444.404301.89689484.556305.17749524.707303.08949584.903308.74219604.946307.9372
9655.053300.51149675.096 303.0829765.222305.27849885.296303.26239905.303293.7238
9925.309288.63429945.315289.29859995.331279.252610025.34280.770110055.34290.2973
10085.35293.728910195.37293.650910395.53302.427110435.57301.244210475.61303.5775
10666.08305.809310746.28311.521410826.58310.058110906.93311.753910990.48317.5377
#Mann= 3 , 0 , 0
8633.277   0.073       08633.277   0.073       010990.48   0.073       0
#XS Ineff= 2 , 0
       09845.962        10335.23       0
Bank Sta=8633.277,10990.48
Exp/Cntr=0.3,0.1

Type RM Length L Ch R = 1 ,53673.76,498.306700,498.306700,498.306700
XS GIS Cut Line= 6
614298.198983926740334.782978196613739.555284039740236.612775246
613333.577864892740207.319599854612975.264298634740215.774726173
612443.882072596740266.216669388611830.389948239740250.159826029
#Sta/Elev= 30
8496.673326.13758571.592318.7823 8653.36303.49968714.477297.59938742.323302.6666
8775.509296.68228876.912296.19229038.447296.86369068.713301.18199289.637295.9137
9699.912298.90669780.021295.87859820.097300.62339880.354 296.7299920.545282.0712
 9960.88282.12799981.047277.221410011.31275.4145 10021.4277.407610031.48285.2768
10041.57  288.7610071.84292.541510212.52291.874110342.73 298.33710402.76296.4894
10522.78298.989510582.78303.371410652.79302.866310752.84 317.66810977.86322.0883
#Mann= 3 , 0 , 0
8496.673   0.082       08496.673   0.082       010977.86   0.082       0
#XS Ineff= 2 , 0
       09866.742        10371.68       0
Bank Sta=8496.673,10977.86
Exp/Cntr=0.3,0.1