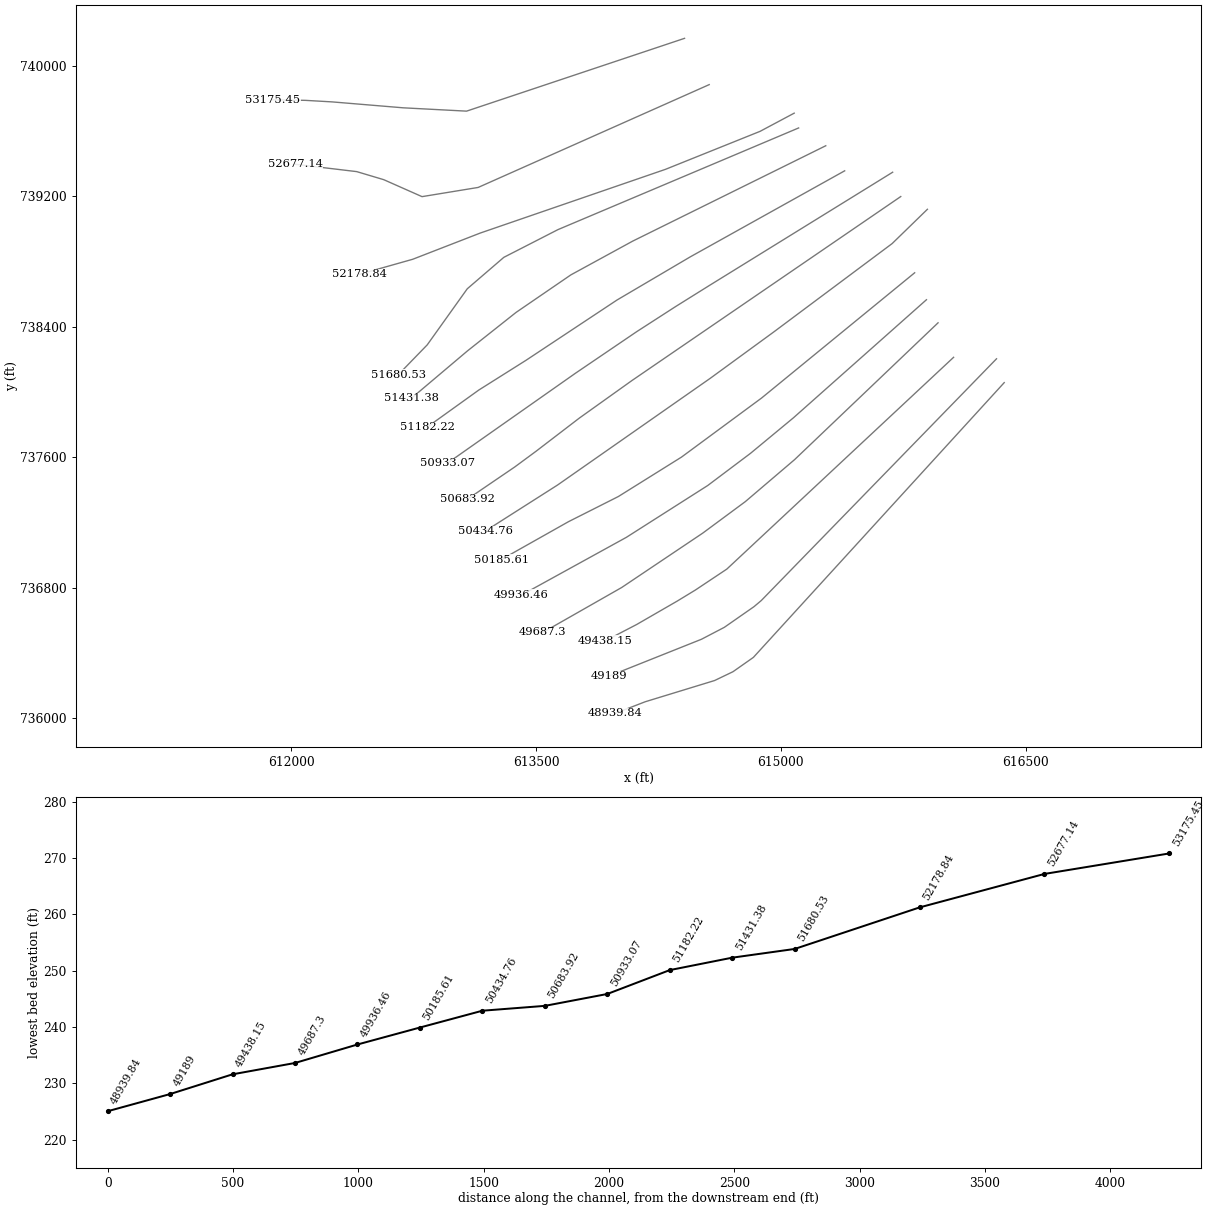
HEC-RAS study 3120_ras.prj: 3120

--- 3120_ras.g01 (geometry) --- (continued)

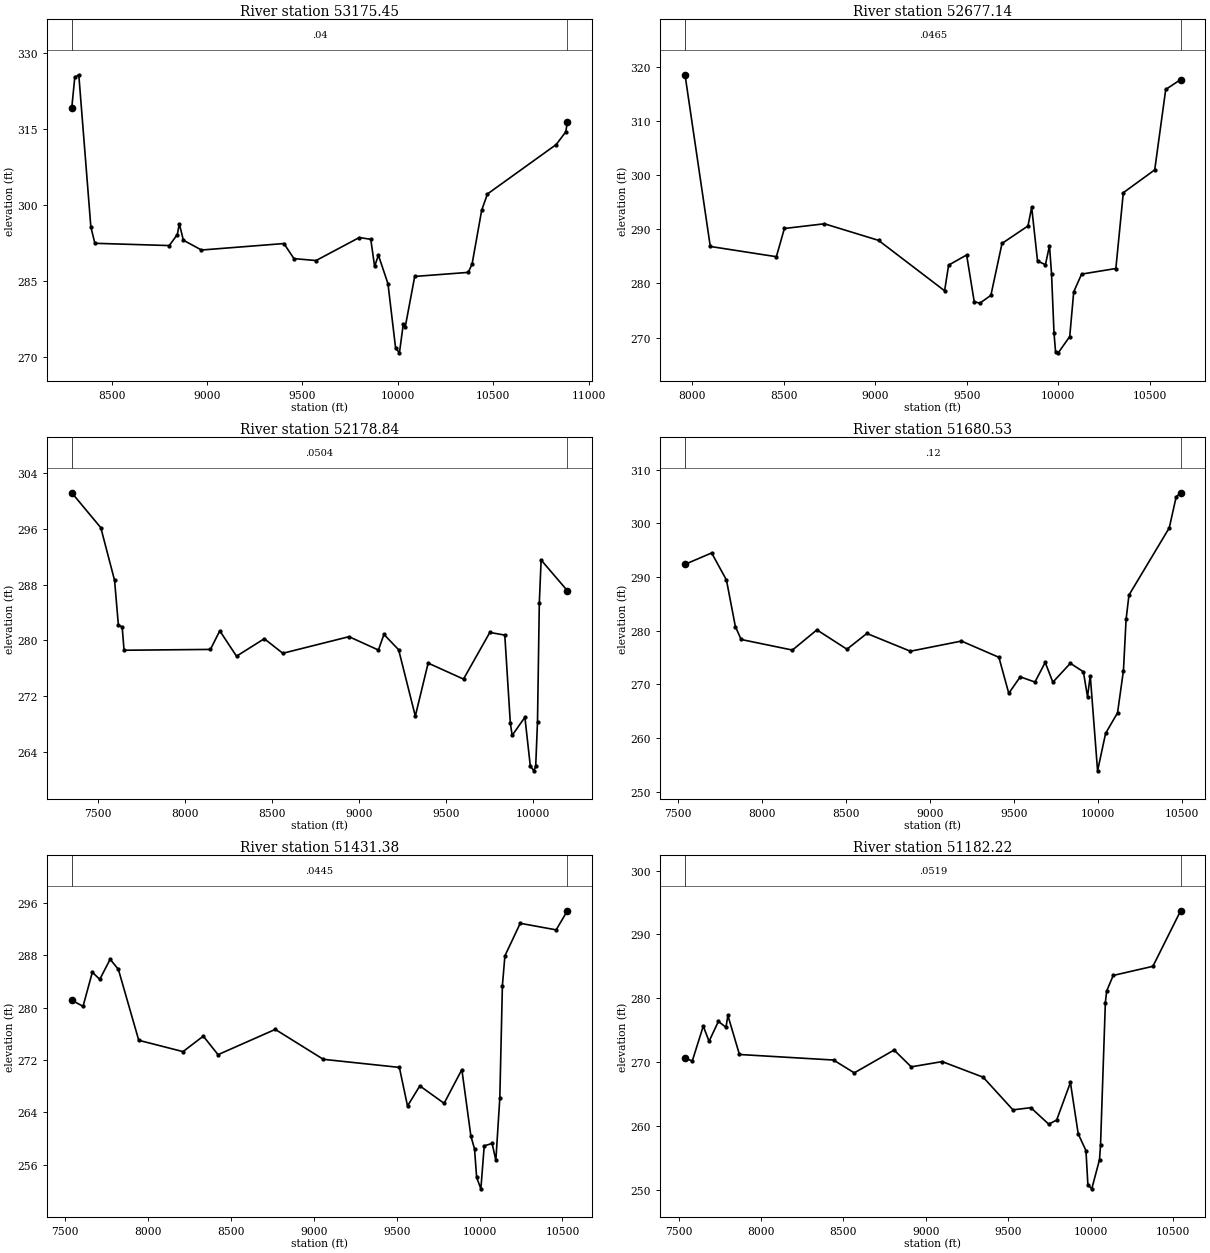
Type RM Length L Ch R = 1 ,53175.45,498.306700,498.306700,498.306700
XS GIS Cut Line= 6
614409.957442611740168.593184501613073.983039845739722.364546731
612685.740578187739742.742405329612250.247704704739779.010831284
612085.986693132739788.472118256 611886.39396007739791.945183585
#Sta/Elev= 30
8290.568 319.1378306.337325.16828327.423325.67938390.682295.65798411.768292.4345
8801.861291.98588844.034294.16678854.577 296.2778875.663293.04788970.551291.1062
9402.816292.38379455.532289.40869571.505 289.0349798.209293.57379858.289293.2172
9878.316287.87929898.342290.08579948.409 284.4539988.462271.746710008.49270.8227
10028.52276.428410038.54275.843310088.61 285.89510369.55286.695410389.62288.3757
10439.81298.968110469.92302.163210830.44311.913110880.44314.411410889.05316.3281
#Mann= 3 , 0 , 0
8290.568    0.04       08290.568    0.04       010889.05    0.04       0
#XS Ineff= 2 , 0
       09896.885        10474.23       0
Bank Sta=8290.568,10889.05
Exp/Cntr=0.3,0.1

Type RM Length L Ch R = 1 ,52677.14,498.306700,498.306700,498.306700
XS GIS Cut Line= 6
614561.159409984739884.898366845 613145.00000003739254.715777069
612800.949458304739198.335432597612566.041738921739302.416219395
612400.808569527739351.658066898612023.649274948739396.731405667
#Sta/Elev= 30
7960.431318.47978098.517286.80788459.716284.91518503.498290.12258722.406290.9919
9017.932287.9349 9379.13278.63049401.021283.3633 9499.53285.23889540.875276.6457
9571.275276.33049632.076277.79269692.876287.36969834.743290.5893 9855.01294.0311
9887.051284.11829930.198283.44429952.356286.95629963.436281.81619977.021270.8536
9985.594267.350510000.21267.183210063.01270.195510084.73278.431210127.82 281.707
10315.04282.740210355.81296.725710527.38300.934110587.56315.773710669.05317.5906
#Mann= 3 , 0 , 0
7960.431  0.0465       07960.431  0.0465       010669.05  0.0465       0
#XS Ineff= 2 , 0
       09833.376                       0
Bank Sta=7960.431,10669.05
Exp/Cntr=0.3,0.1

Type RM Length L Ch R = 1 ,52178.84,498.306700,498.306700,498.306700
XS GIS Cut Line= 6
615082.097588599739710.042449355614872.802153796739598.486772552
614293.469523609739365.811320469 613158.02448675738975.231362253
612743.688982487738814.382977769612420.049904525738723.005439222
#Sta/Elev= 30
7352.249301.20317518.937296.1821  7597.9 288.605 7619.64282.19797641.381281.9223
7652.251278.57178147.794278.69038201.419281.36438297.408277.71468456.787280.2284
8562.862278.13528942.731280.52149111.451278.60199143.086280.84649227.445278.6424
9323.094269.10349396.642 276.7239599.554274.42679750.572281.1343 9836.38280.7468
9868.202268.09489878.672266.33149951.722268.9415 9982.72261.931210003.39261.2394
10013.74261.9199 10024.1268.319310034.45285.3646 10044.8291.539210195.46287.1324
#Mann= 3 , 0 , 0
7352.249  0.0504       07352.249  0.0504       010195.46  0.0504       0
#XS Ineff= 2 , 0
       09734.597                       0
Bank Sta=7352.249,10195.46
Exp/Cntr=0.3,0.1

Type RM Length L Ch R = 1 ,51680.53,249.153300,249.153300,249.153300
XS GIS Cut Line= 6
615109.134889219739619.330543713613633.887640736738996.106246872
613302.515734442738826.401464526613078.342309438738633.650408974
612832.989719308738290.024077066612655.588673944738107.180003206
#Sta/Elev= 30
7541.723292.36157700.213294.48027788.181289.44027841.327 280.7627875.694278.3509
8180.701276.37918326.294280.14378505.038276.53758623.605279.47428882.294276.1648
9186.203278.05659409.135275.02849467.775268.32549536.158271.39269623.605270.4201
9684.539274.07529730.182270.39159834.189273.91839911.788272.32759936.368267.6835
9952.626271.62429996.177253.869310043.91260.850210114.97264.686510150.04272.5585
10165.84282.118710182.89286.625110422.59299.157310463.69304.932210490.29305.6968
#Mann= 3 , 0 , 0
7541.723    0.12       07541.723    0.12       010490.29    0.12       0
#XS Ineff= 2 , 0
       09827.977                       0
Bank Sta=7541.723,10490.29
Exp/Cntr=0.3,0.1

Type RM Length L Ch R = 1 ,51431.38,249.153400,249.153400,249.153400
XS GIS Cut Line= 6
615275.565497682739510.251568114614092.227888853738925.718397241
613713.380982172738718.882933136613377.536855416738488.903362845
613078.971429643738252.426037985612735.375690653737962.195595706
#Sta/Elev= 30
7540.259281.12647608.259280.19097664.397285.39817709.307284.31177771.758287.3774
7821.401285.83727944.313275.00558211.341 273.2768333.644275.64038422.592272.8096
8767.778  276.679057.786272.09859516.331270.86749565.451264.97369639.809268.0422
9786.206265.38219893.278  270.539947.807260.36579969.659258.42319982.389254.0776
10007.95252.321410028.13258.884910075.88259.254210098.35256.682210122.21   266.2
10137.79283.367710153.01287.907510245.41292.870710462.03291.868510529.76294.7835
#Mann= 3 , 0 , 0
7540.259  0.0445       07540.259  0.0445       010529.76  0.0445       0
#XS Ineff= 2 , 0
       09845.157                       0
Bank Sta=7540.259,10529.76
Exp/Cntr=0.3,0.1

Type RM Length L Ch R = 1 ,51182.22,249.153300,249.153300,249.153300
XS GIS Cut Line= 6
615391.435087823739356.629927381614446.521732855738830.066097756
613996.438516715738564.973727832613438.366527953738195.295899363
613148.931405656738012.932742296  612832.4638766737785.772492105
#Sta/Elev= 30
7539.233270.62887583.259270.15487649.952275.6319 7685.03273.24497741.801276.3666
7787.696275.43797799.134277.30137869.278271.17918439.688270.31018565.511 268.297
 8807.09271.87868910.909269.24119098.316270.06489347.091 267.6189527.687262.4983
9636.119262.84079744.552260.25839792.744260.89819876.101266.79279923.435258.7312
 9970.38 256.1179982.117250.734710005.59 250.11710052.61254.6959 10058.7256.9469
10088.08279.328410095.94281.133110135.75283.572910376.39 285.00510544.48293.7096
#Mann= 3 , 0 , 0
7539.233  0.0519       07539.233  0.0519       010544.48  0.0519       0
#XS Ineff= 2 , 0
       0 9822.07                       0
Bank Sta=7539.233,10544.48
Exp/Cntr=0.3,0.1

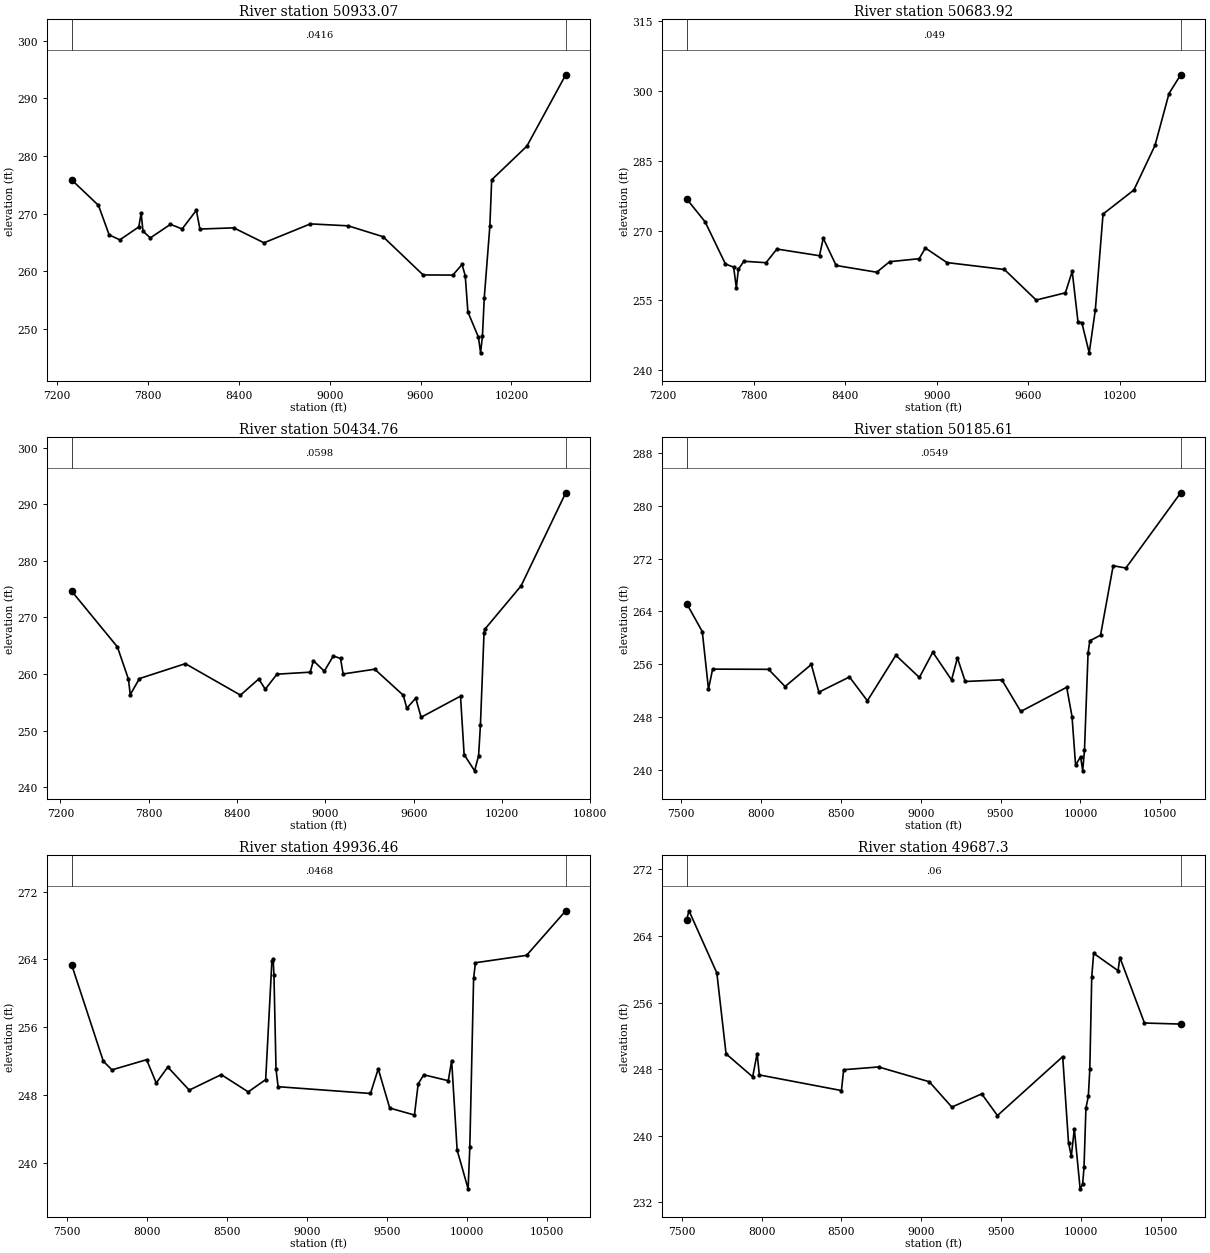
Type RM Length L Ch R = 1 ,50933.07,249.153400,249.153400,249.153400
XS GIS Cut Line= 6
 615685.51092419739347.994448021614558.097995013 738651.32225211
614355.249842674738524.620361418614117.238483429738371.109447762
613739.561836094738114.723396584612954.835998297737563.404865265
#Sta/Elev= 30
 7295.65275.85497472.579271.4488 7543.11266.33457613.641265.46937738.881267.7075
7754.704270.09797766.459266.98497814.974265.80257948.137268.15748025.073 267.356
8119.115 270.5948142.625267.33968365.974267.54958565.813264.95598872.311268.2362
9122.201267.8977 9352.25266.01339616.748259.38489813.113259.35939874.205261.1989
9895.204259.21479912.607252.96749982.221248.59539996.389245.878710008.64248.7484
10020.88255.4599 10057.6267.818110069.84275.880310302.41281.719110558.86294.0862
#Mann= 3 , 0 , 0
 7295.65  0.0416       0 7295.65  0.0416       010558.86  0.0416       0
#XS Ineff= 2 , 0
       09799.327                       0
Bank Sta=7295.65,10558.86
Exp/Cntr=0.3,0.1

Type RM Length L Ch R = 1 ,50683.92,249.153300,249.153300,249.153300
XS GIS Cut Line= 6
615735.203787148739198.915859208  614086.8987405738070.742488563
613765.400141716737841.245268688613498.102566332737636.481809363
613369.416903406737541.568106368613076.974817157737342.497501031
#Sta/Elev= 30
7358.708276.7942 7480.05271.86197613.254262.8233 7667.09262.15187684.821257.7078
 7698.02261.67447734.349263.41347879.869263.10687950.796266.03948230.837264.6021
8255.056 268.3598339.823262.50858606.231261.05998690.997 263.3188884.819263.9658
8925.638266.2515 9066.98263.13399444.054261.64999652.849255.09369844.608 256.644
9889.382 261.2419927.232250.4438 9952.58250.2258   10001243.769410041.22253.0074
10091.72 273.53910294.27278.698410432.78288.260610524.72299.398910601.56 303.415
#Mann= 3 , 0 , 0
7358.708   0.049       07358.708   0.049       010601.56   0.049       0
#XS Ineff= 2 , 0
       09804.652                       0
Bank Sta=7358.708,10601.56
Exp/Cntr=0.3,0.1

Type RM Length L Ch R = 1 ,50434.76,249.153400,249.153400,249.153400
XS GIS Cut Line= 6
615898.480336726739120.827074617 615682.46465224 738910.73309125
614956.805803001738368.994628876614568.685859293738085.712886751
 613632.32640788737431.249766544613187.788353682 737148.06393382
#Sta/Elev= 30
7276.245 274.6517586.894   264.8 7661.77259.11517674.249256.37097736.646259.2083
8048.629261.83958423.008256.28588547.289259.1305  8591.7 257.3268671.092259.9861
8897.018260.33868918.699262.37378992.672260.51089053.922263.20369102.922262.7567
 9120.71 260.0219335.228260.86239529.236256.26479553.488253.96749614.115255.7531
9650.492252.37339918.303 256.1059942.845245.779310014.22242.909310041.16245.6048
10053.49250.940610078.15267.3446 10082.6267.899210330.05275.588510633.24292.0279
#Mann= 3 , 0 , 0
7276.245  0.0598       07276.245  0.0598       010633.24  0.0598       0
#XS Ineff= 2 , 0
       09804.436                       0
Bank Sta=7276.245,10633.24
Exp/Cntr=0.3,0.1

Type RM Length L Ch R = 1 ,50185.61,249.153300,249.153300,249.153300
XS GIS Cut Line= 6
615820.408881276738731.689803473614882.265507427737964.142337847
614391.551064859737602.130801118614004.352793538 737360.34224333
613698.931486933737206.275520672613286.943892198736974.085504239
#Sta/Elev= 30
7534.109265.19927631.876260.9679 7670.77252.2805  7696.7255.29478046.752 255.262
8150.471252.6643 8314.51255.9946  8362.1251.81338553.492 254.1098665.723250.5099
8843.778257.38448991.379254.03369075.462257.84889192.946253.65769229.635256.9892
9278.553253.42489508.152253.67349626.286248.89429913.823 252.5519947.269248.1194
9969.566240.7707   10001242.069510014.18239.925710025.34243.088110047.66257.7338
10058.82259.5778 10125.8260.418510204.94270.906310284.69270.573610627.84281.9355
#Mann= 3 , 0 , 0
7534.109  0.0549       07534.109  0.0549       010627.84  0.0549       0
#XS Ineff= 2 , 0
       09800.642                       0
Bank Sta=7534.109,10627.84
Exp/Cntr=0.3,0.1

Type RM Length L Ch R = 1 ,49936.46,249.153300,249.153300,249.153300
XS GIS Cut Line= 6
615892.605483403738566.529652508615078.219436244737843.548496187
614814.226070228737625.053637024614551.978101041737427.786871251
614053.275872291737110.107286106 613410.93228428736756.535319342
#Sta/Elev= 30
7531.967263.35787729.499251.98067783.424250.96267999.824252.16418059.896249.4099
8131.916251.29828265.951 248.5698465.821250.39978634.196248.36228743.209249.8101
8781.979263.78478789.782264.08198794.886262.14678807.793251.0473  8820.7 248.974
9397.436248.17389445.986251.07779517.724246.4527 9672.09 245.6299695.343249.3057
9730.224250.38199883.375249.68339904.278252.05669938.589241.492610007.18236.9152
10017.73241.8501 10041.4261.7525 10052.8263.610610372.11264.4835 10616.6269.7456
#Mann= 3 , 0 , 0
7531.967  0.0468       07531.967  0.0468       0 10616.6  0.0468       0
#XS Ineff= 2 , 0
       09789.709                       0
Bank Sta=7531.967,10616.6
Exp/Cntr=0.3,0.1

Type RM Length L Ch R = 1 , 49687.3,249.153400,249.153400,249.153400
XS GIS Cut Line= 6
615963.753870388 738425.01867539615084.588907876 737586.62626646
 614782.41850689737329.062308047614521.699945938 737136.18190107
614024.665940798 736802.69472111613541.529775975736527.388800156
#Sta/Elev= 30
7531.377265.95787545.928267.03367720.226259.56277777.846249.85227944.412247.0918
  7972.2249.88587986.094247.31668499.885245.44078513.541247.94238732.031248.2755
 9049.43246.49779190.524243.45669377.517245.04099475.797242.43759884.166249.5121
9920.524239.17949938.077237.56619956.881240.83229993.239233.635510008.87 234.175
10017.47236.204410029.57243.3512 10044.4244.726610053.76 247.97410065.86259.0913
10077.74261.920110230.54259.841210242.02261.420110395.72253.551910622.53253.4258
#Mann= 3 , 0 , 0
7531.377    0.06       07531.377    0.06       010622.53    0.06       0
#XS Ineff= 2 , 0
       0 9794.64                       0
Bank Sta=7531.377,10622.53
Exp/Cntr=0.3,0.1

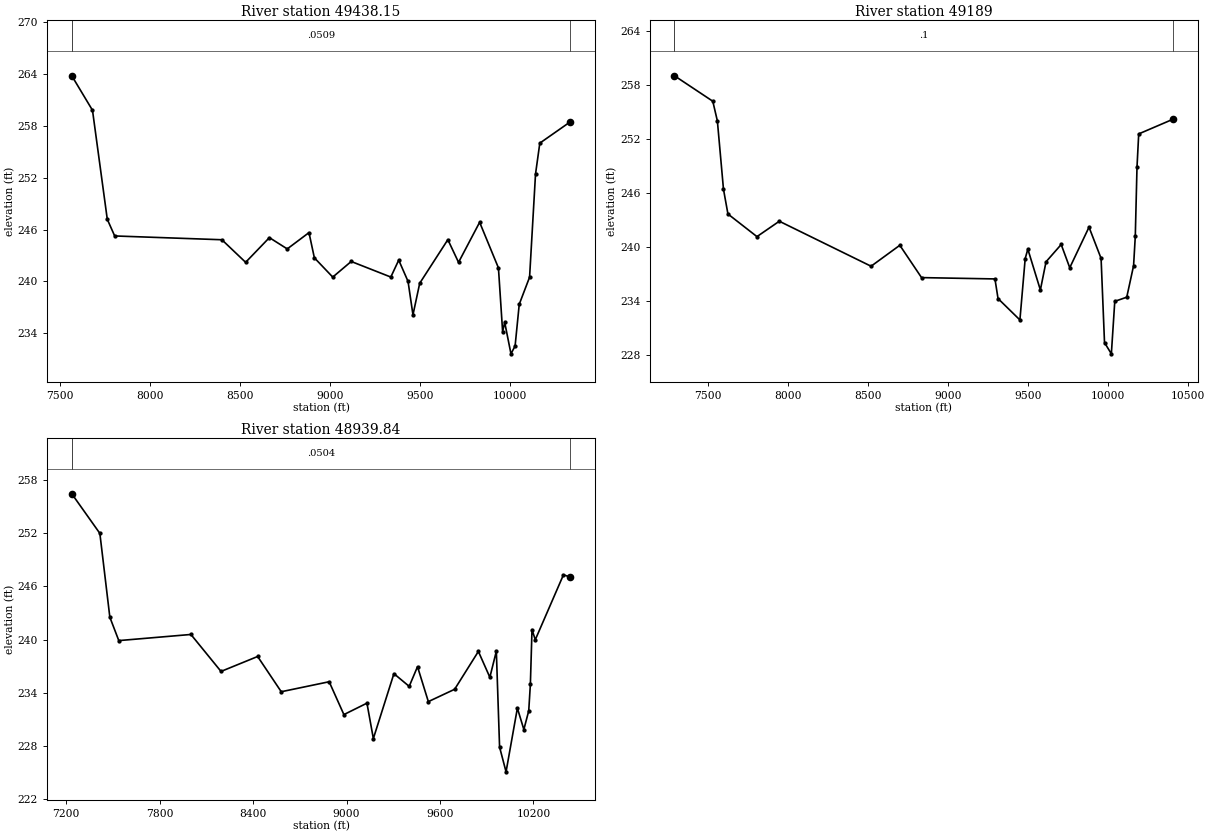
Type RM Length L Ch R = 1 ,49438.15,249.153300,249.153300,249.153300
XS GIS Cut Line= 6
616059.028893888738213.645576939614669.165777445 736915.61349234
614476.604491085736787.370746255614365.038331747736719.449784935
 614116.58323729736575.983933762613924.837103397736476.383138612
#Sta/Elev= 30
7565.973263.78717680.949259.79667763.046247.18537804.095245.25968399.091244.8202
 8530.95242.20878662.808245.06598761.899243.75998882.572245.64488912.411242.7305
9014.431240.50089116.987242.30679336.751240.50529380.704242.46379432.362240.0039
9459.728236.13589497.138239.78559653.361244.83049712.683242.20529829.757246.8408
9934.129241.56579957.322234.19319968.919235.260310003.68231.623110026.64232.5359
10049.59237.354710106.97240.489410139.95252.420710163.76255.994610332.71 258.458
#Mann= 3 , 0 , 0
7565.973  0.0509       07565.973  0.0509       010332.71  0.0509       0
#XS Ineff= 2 , 0
       09823.688                       0
Bank Sta=7565.973,10332.71
Exp/Cntr=0.3,0.1

Type RM Length L Ch R = 1 ,   49189,249.153400,249.153400,249.153400
XS GIS Cut Line= 6
616322.059916258738204.536136508614880.235358089736722.810927078
614835.511646926736685.189085275 614653.90952298736558.643908739
614513.840708137736485.570914418 613947.00332886736259.470789269
#Sta/Elev= 30
7288.723259.03887528.273256.20787556.951254.01567595.042 246.4247622.948243.6695
7804.338241.15457944.108242.86478517.675237.86218697.331240.19128833.136236.5965
9291.989236.44939311.264234.2672    9448231.88859481.066238.71959497.599239.7606
9575.896235.22239611.274 238.3559706.068240.27829759.527237.69519879.956242.2055
9955.416238.7336 9976.83229.367810019.61  228.1210040.98233.958110115.78234.4172
10158.53 237.91810169.22241.1986 10179.9248.879210190.59252.574410404.55254.2047
#Mann= 3 , 0 , 0
7288.723     0.1       07288.723     0.1       010404.55     0.1       0
#XS Ineff= 2 , 0
       0 9814.94                       0
Bank Sta=7288.723,10404.55
Exp/Cntr=0.3,0.1

Type RM Length L Ch R = 1 ,48939.84,747.460000,747.460000,747.460000
XS GIS Cut Line= 6
616369.338037938738058.491004914614831.889702708736374.388385013
614706.742857784736286.526623905614594.068256497736232.499875486
614169.251689613 736102.56436941613985.016046196 736031.41947788
#Sta/Elev= 30
7235.239256.4559 7415.57251.9866 7479.67242.52437537.151239.88458000.249240.5764
8193.607236.40448428.738238.09018580.323234.1118 8888.04  235.248982.602231.5323
9130.649232.82299171.727 228.8279303.814236.15239401.938234.71789455.351236.9421
9524.897232.99679693.739234.38929846.203238.66059919.917235.7434 9961.54238.6901
9982.352 227.86510023.93225.070810096.65 232.264 10138.2229.848310169.55231.9586
10180.05234.939710190.55241.128810211.55239.978310392.66247.315310436.14247.0471
#Mann= 3 , 0 , 0
7235.239  0.0504       07235.239  0.0504       010436.14  0.0504       0
#XS Ineff= 2 , 0
       09828.528                       0
Bank Sta=7235.239,10436.14
Exp/Cntr=0.3,0.1