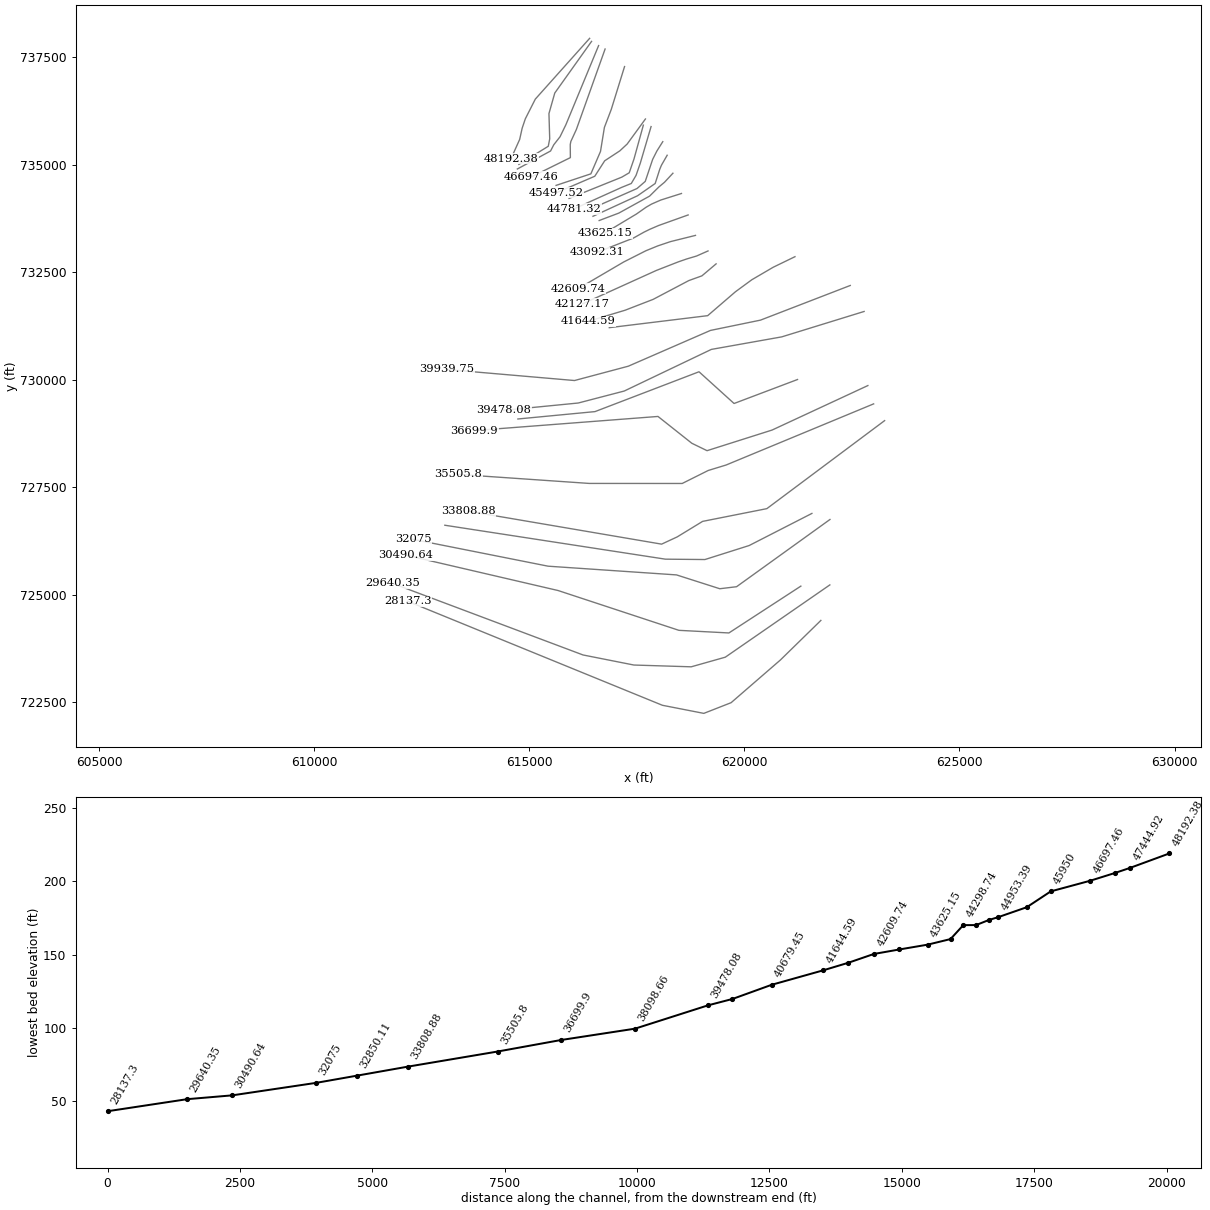
HEC-RAS study 3120_ras.prj: 3120

--- 3120_ras.g01 (geometry) --- (continued)

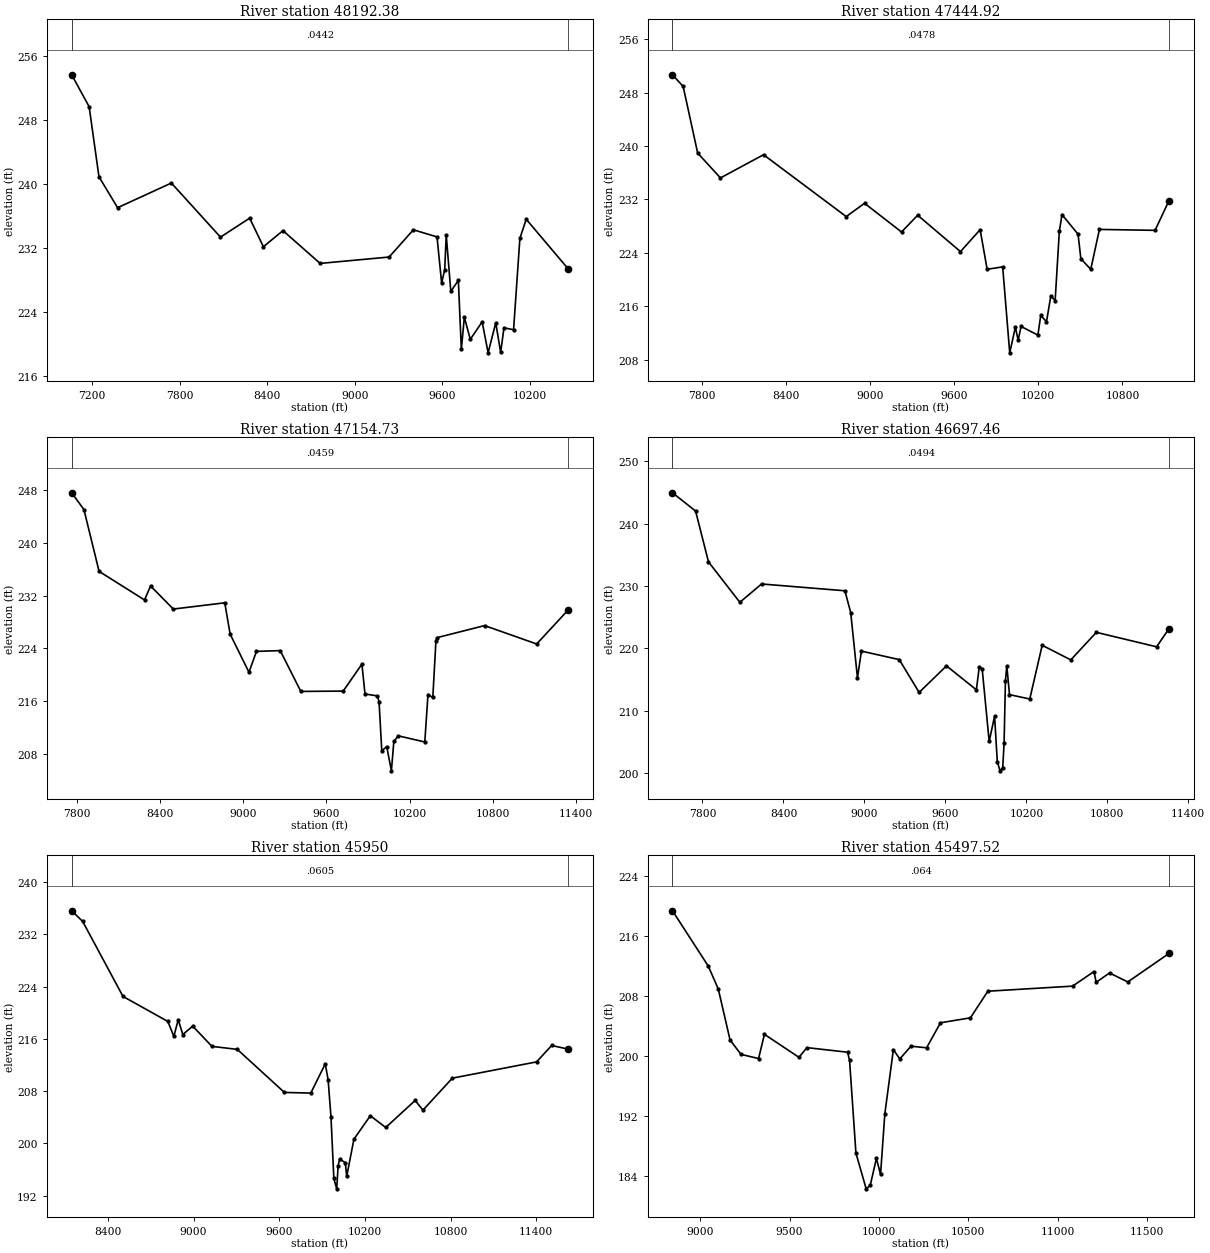
Type RM Length L Ch R = 1 ,48192.38,747.460000,747.460000,747.460000
XS GIS Cut Line= 6
616404.801940113737934.367347285615141.783602238736521.831122324
614909.862582445736063.992380187614835.919233054735844.942857623
614778.414938033 735585.13939704614574.311745971735132.260858566
#Sta/Elev= 30
7059.383253.62377179.106249.63837246.338240.8916 7374.14237.03147742.676 240.111
8079.262233.35728279.259235.72758373.161232.15678507.306234.16878762.183230.0759
9235.024230.8728 9401.11234.27139563.133233.38599594.724227.63219615.784229.2791
9626.314233.61099657.588226.58789709.346227.95229729.851219.34999750.356223.3667
9791.231220.59799872.626 222.783 9913.34218.9134 9965.69 222.6689999.376 218.957
10021.88222.037610087.73221.797810131.04233.200210174.35235.589710462.54229.3864
#Mann= 3 , 0 , 0
7059.383  0.0442       07059.383  0.0442       010462.54  0.0442       0
#XS Ineff= 2 , 0
       09635.346        10148.83       0
Bank Sta=7059.383,10462.54
Exp/Cntr=0.3,0.1

Type RM Length L Ch R = 1 ,47444.92,290.194600,290.194600,290.194600
XS GIS Cut Line= 6
616449.131817877737863.439542934 615594.13717404736663.168410644
615458.872306764736186.161548018615476.519797951735597.268766806
615442.881212056735425.825626746614760.163476676735004.162429824
#Sta/Elev= 30
7593.088 250.6637669.153248.91057772.568238.93497934.948235.2063 8241.89238.6855
 8831.22229.41958961.843 231.406 9225.47227.10789340.614229.61849645.579 224.172
9785.705227.45259835.768221.51859946.334221.87979996.652209.001110036.93212.8494
10057.01210.884210077.07212.954210197.42211.660210217.68 214.60810258.69213.6617
10289.54217.531810320.39216.833110350.43227.289410369.46 229.70610483.64226.7745
10503.64223.099910574.16221.512510635.88227.492911032.55 227.35411132.26231.8251
#Mann= 3 , 0 , 0
7593.088  0.0478       07593.088  0.0478       011132.26  0.0478       0
#XS Ineff= 2 , 0
       0 9901.15        10388.13       0
Bank Sta=7593.088,11132.26
Exp/Cntr=0.3,0.1

Type RM Length L Ch R = 1 ,47154.73,457.265500,457.265500,457.265500
XS GIS Cut Line= 6
616613.152365416737765.913811952615852.227887839 735926.33162412
615716.232082725735646.539682776615571.180279732735460.817967415
615496.494379431735316.016231775  614724.6995745734897.770723298
#Sta/Elev= 30
 7763.95247.55817852.281245.01947961.449235.66888288.951231.34228332.618233.4601
8496.369229.96318867.538230.91038906.127 226.176 9041.91220.40139095.929223.5598
9267.229 223.6789415.864217.50129721.235217.55279856.045221.63219878.307217.1158
9968.445216.82179979.728215.89999999.323208.508510035.02209.1528 10068.6205.4863
10086.22209.939310118.41210.783410309.31 209.85210332.42217.033110367.09216.5855
10389.64225.102110397.95 225.64210740.36227.4634 11115.7224.680611343.52229.8384
#Mann= 3 , 0 , 0
 7763.95  0.0459       0 7763.95  0.0459       011343.52  0.0459       0
#XS Ineff= 2 , 0
       09896.343        10407.04       0
Bank Sta=7763.95,11343.52
Exp/Cntr=0.3,0.1

Type RM Length L Ch R = 1 ,46697.46,747.460000,747.460000,747.460000
XS GIS Cut Line= 6
616763.873949677737686.120032057616095.822387069735815.570958376
615967.301351815 735536.20126605615953.721428841735464.589893758
 615956.80427897735162.009280458615052.035452873734715.051445842
#Sta/Elev= 30
7577.772244.95257748.984242.01787844.621233.85318077.033227.37258237.796 230.314
8855.532229.2213 8898.56225.70518948.525215.24528977.947219.53569258.275218.1738
9405.733 212.9049608.274217.16979829.683213.32289851.451 217.0289873.153216.5999
9924.578205.03459964.676209.08699984.767201.814210004.91200.318110025.05200.8386
10035.12204.755410045.15214.791510055.17217.171510075.21212.549410225.45211.8511
10317.47220.474410529.39218.1296   10719222.549511165.15220.226811257.69223.1571
#Mann= 3 , 0 , 0
7577.772  0.0494       07577.772  0.0494       011257.69  0.0494       0
#XS Ineff= 2 , 0
       09747.429        10075.72       0
Bank Sta=7577.772,11257.69
Exp/Cntr=0.3,0.1

Type RM Length L Ch R = 1 ,   45950,452.482600,452.482600,452.482600
XS GIS Cut Line= 6
617216.038702458737278.285156995616907.328803629736282.899608746
616747.613261223735863.933046609616656.900045067735305.493250787
616433.032927603734784.923341885615624.596092224734516.533774883
#Sta/Elev= 30
8146.864235.62168223.593233.9996 8506.28 222.5028820.377218.67198862.257216.3783
8893.058218.93658925.076216.66458994.334217.95639129.368214.85359306.724214.3949
9636.629   207.89821.642207.70379922.723212.18579942.812209.73329962.824204.0503
9982.835194.636910002.84193.036410012.85196.531110022.85 197.601 10062.9197.0476
10072.94194.951210123.51200.645410238.42204.2317 10346.1202.430610551.96206.5672
10607.11205.091610812.73209.986811402.78212.480211508.15214.990711624.48214.4312
#Mann= 3 , 0 , 0
8146.864  0.0605       08146.864  0.0605       011624.48  0.0605       0
#XS Ineff= 2 , 0
       09910.469        10211.65       0
Bank Sta=8146.864,11624.48
Exp/Cntr=0.3,0.1

Type RM Length L Ch R = 1 ,45497.52,544.130800,544.130800,544.130800
XS GIS Cut Line= 6
617701.024701774736059.710304275617277.280665278735478.248987019
617106.347190797735319.265474379616754.499537855735088.510186493
 616523.78596586734728.960372984615629.029079974734343.647251755
#Sta/Elev= 30
8844.528219.36439044.932211.97639100.871  208.929166.785202.11879228.012200.2016
9326.323199.64649359.176202.87899552.278199.80659597.234201.10279824.579200.4889
9835.572199.41189871.274187.02849928.684182.25799951.555182.73769985.861186.3149
10009.08184.187110033.02192.264510080.82 200.82710116.82199.596810179.53201.2964
10266.84201.077910344.51204.416610512.13205.079710609.67208.632311083.91209.3101
11203.67211.252311215.96209.822111290.78211.064911392.94209.865111623.91213.6782
#Mann= 3 , 0 , 0
8844.528   0.064       08844.528   0.064       011623.91   0.064       0
#XS Ineff= 2 , 0
       09767.481        10166.65       0
Bank Sta=8844.528,11623.91
Exp/Cntr=0.3,0.1

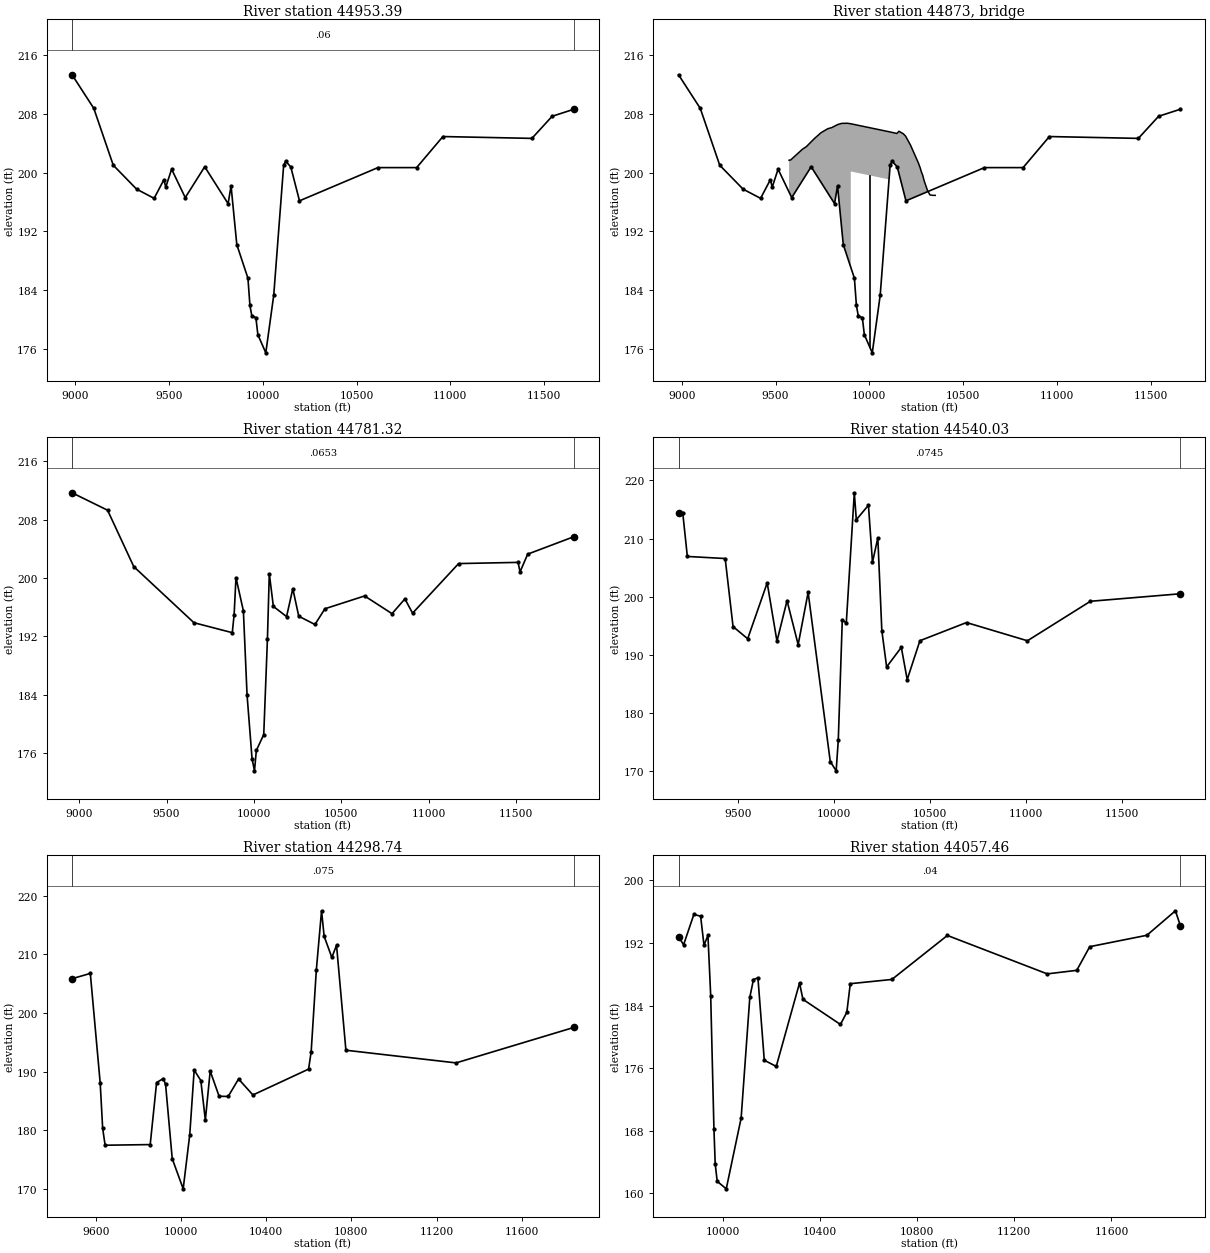
Type RM Length L Ch R = 1 ,44953.39,172.075200,172.075200,172.075200
XS GIS Cut Line= 5
617652.912995398735916.744228259617435.429615587735130.228991628
617324.525720716734809.506917283617152.102298498734708.362100765
615927.489209175734213.617838934
#Sta/Elev= 30
8982.879213.33629098.816208.75589202.569201.00889327.072 197.7499420.449196.4942
9472.326199.01939482.701198.03929513.827200.46919586.453196.59289690.206 200.796
9815.023195.77329830.822198.18359861.421 190.1869920.832185.60579931.413181.9025
9941.994180.41279963.156180.24919973.737177.909210016.06175.436310058.39 183.298
10111.29201.004510121.87201.559510149.31200.778110195.68196.1545 10614.1200.6832
10820.38200.682510960.58 204.91711435.14204.666811542.99207.676111658.94208.6384
#Mann= 3 , 0 , 0
8982.879    0.06       08982.879    0.06       011658.94    0.06       0
#XS Ineff= 2 , 0
       09873.009        10127.74       0
Bank Sta=8982.879,11658.94
Exp/Cntr=0.3,0.1

Type RM Length L Ch R = 3 ,   44873,,,
BEGIN DESCRIPTION:
END DESCRIPTION:
Bridge Culvert--1,0,-1,-1, 0
Deck Dist Width WeirC Skew NumUp NumDn MinLoCord MaxHiCord MaxSubmerge Is_Ogee
61.537600,49.000000,2.6,0, 30, 30, , , 0.95, 0, 0,0,,
 9572.17 9581.04 9643.65 9664.52 9707.29 9742.29 9758.43 9779.30 9800.17 9831.48
 9852.35 9883.65 9901.48 9901.4810102.4810102.4810147.4910158.0610180.9010193.87
10219.8110262.0110271.6910277.7110284.6610293.4210310.6010323.5810340.5210351.75
  201.69  201.73  203.19  203.54  204.64  205.43  205.68  205.99  206.14  206.55
  206.71  206.73  206.66  206.66  205.59  205.59  205.34  205.64  205.31  204.97
  203.76  201.32  200.65  200.12  199.67  198.84  197.57  196.96  196.90  196.90
 -798.31 -798.27 -796.81 -796.46 -795.36 -794.57 -794.32 -794.01 -793.86 -793.45
 -793.29 -793.27 -793.34  200.16  199.09 -794.41 -794.66 -794.36 -794.69 -795.03
 -796.24 -798.68 -799.35 -799.88 -800.33 -801.16 -802.43 -803.04 -803.10 -803.10
 9572.17 9581.04 9643.65 9664.52 9707.29 9742.29 9758.43 9779.30 9800.17 9831.48
 9852.35 9883.65 9905.13 9905.1310106.1310106.1310147.4910158.0610180.9010193.87
10219.8110262.0110271.6910277.7110284.6610293.4210310.6010323.5810340.5210351.75
  201.69  201.73  203.19  203.54  204.64  205.43  205.68  205.99  206.14  206.55
  206.71  206.73  206.64  206.64  205.57  205.57  205.34  205.64  205.31  204.97
  203.76  201.32  200.65  200.12  199.67  198.84  197.57  196.96  196.90  196.90
 -798.31 -798.27 -796.81 -796.46 -795.36 -794.57 -794.32 -794.01 -793.86 -793.45
 -793.29 -793.27 -793.36  200.14  199.07 -794.43 -794.66 -794.36 -794.69 -795.03
 -796.24 -798.68 -799.35 -799.88 -800.33 -801.16 -802.43 -803.04 -803.10 -803.10
Pier Skew, UpSta & Num, DnSta & Num=  ,10001.98, 2 ,10005.63, 2 , 0 , 0 , 0 ,,
    4.00    4.00
 -793.88  206.12
    4.00    4.00
 -793.90  206.10
BR Coef=-1 , 0 , 0 ,, 0 ,,,0.8,0,1,0,
WSPro=,,,, 1 ,,,, 0 ,,,, 0 ,,,,-1 ,-1 ,-1 , 0 , 0 , 0 , 0 , 0
BC Design=,, 0 ,, 0 ,,,,,,

Type RM Length L Ch R = 1 ,44781.32,241.286200,241.286200,241.286200
XS GIS Cut Line= 6
617832.384054184735883.426762924617582.302341223735034.312109575
617483.388056725734749.558866024617372.484161854734560.722504482
617152.102298498734471.816961899616034.352109015733967.011147022
#Sta/Elev= 30
8959.808211.67249162.921 209.2819312.607201.55449656.622193.86529876.014192.4979
  9886.6194.96689897.186200.04789939.531195.48899960.703183.90089989.139175.2306
10003.05173.562610013.63176.359910055.98178.529910077.15191.677110087.74  200.59
10111.04196.097910186.51 194.70410222.23198.530310256.09194.754310348.86193.6207
10405.84195.7765 10632.8197.531410789.69195.104510863.22197.129310907.11195.1717
11170.45201.9695 11510.6202.132511521.58200.823111565.47203.262311829.52205.6506
#Mann= 3 , 0 , 0
8959.808  0.0653       08959.808  0.0653       011829.52  0.0653       0
#XS Ineff= 2 , 0
       09886.138        10133.74       0
Bank Sta=8959.808,11829.52
Exp/Cntr=0.3,0.1

Type RM Length L Ch R = 1 ,44540.03,241.286200,241.286200,241.286200
XS GIS Cut Line= 6
618104.703083277735533.122234881617967.660893738735315.872412458
617869.100823969735121.003336459 617697.05171895734609.036336377
617505.772037476734443.784084722616276.848689467733901.249362513
#Sta/Elev= 30
 9189.99214.39289211.787214.43249235.841206.92359432.757206.5669 9473.78194.8739
9549.941192.78419651.506202.3837 9702.33 192.3629754.769199.33059812.685 191.773
9864.571200.74849979.793 171.68910010.51170.093510021.51175.366410042.37196.0067
10063.23195.491910104.96 217.86210115.39213.232610178.48215.720510199.55205.9147
 10227.3210.121310248.19194.195510273.19187.943310349.68191.305210380.27185.7737
10446.42192.446910689.01 195.56911006.01192.438411333.95199.221711801.96200.5124
#Mann= 3 , 0 , 0
 9189.99  0.0745       0 9189.99  0.0745       011801.96  0.0745       0
#XS Ineff= 2 , 0
       09880.433        10069.13       0
Bank Sta=9189.99,11801.96
Exp/Cntr=0.3,0.1

Type RM Length L Ch R = 1 ,44298.74,241.286200,241.286200,241.286200
XS GIS Cut Line= 6
618206.599476059 735217.04126017618073.895887086 734986.07325578
 618035.03664785734893.661153648617927.740211613 734560.23362064
 617518.10237205734275.269511923616482.354265988733798.496574208
#Sta/Elev= 30
9488.001205.86579573.691206.76189620.095188.10739631.696180.36389643.297177.4893
 9855.01177.59929885.064188.17539916.644188.8488 9927.17187.87199958.387175.2075
10009.94170.058410040.81 179.30210061.54190.2955 10092.8188.512610114.01181.7713
10136.78190.135910178.61185.833110221.33185.799910270.05188.770810337.55186.0524
10598.96190.457610611.14 193.43510635.24207.291610659.87217.436310672.05213.0891
10708.23209.490410730.25211.563410774.28193.675511291.69191.516611845.03197.5604
#Mann= 3 , 0 , 0
9488.001   0.075       09488.001   0.075       011845.03   0.075       0
#XS Ineff= 2 , 0
       0  9890.2        10073.45       0
Bank Sta=9488.001,11845.03
Exp/Cntr=0.3,0.1

Type RM Length L Ch R = 1 ,44057.46,432.302400,432.302400,432.302400
XS GIS Cut Line= 6
618340.064471036734799.400742024618143.864681423734588.458874196
618015.161664575734481.289511219617797.589956224734267.049288854
617082.430549681733872.478581786616626.208169609733699.853897437
#Sta/Elev= 30
9817.852192.77859838.728191.76689881.006195.64899908.779195.41639922.666191.7101
9938.905192.95449950.225185.27919963.608168.21269968.752163.7789 9976.99161.5208
 10014.3160.561110075.53169.611210111.31185.065610126.36187.316710144.72187.5406
10170.85177.004110220.08176.209410315.95186.874310329.98184.786810484.36181.5786
10510.62183.128510524.87186.789410696.13 187.33110924.55192.956111335.71 188.044
11457.15188.496711510.61191.521111745.84192.979911863.45196.111811883.54194.2046
#Mann= 3 , 0 , 0
9817.852    0.04       09817.852    0.04       011883.54    0.04       0
#XS Ineff= 2 , 0
       09901.518        10122.94       0
Bank Sta=9817.852,11883.54
Exp/Cntr=0.3,0.1

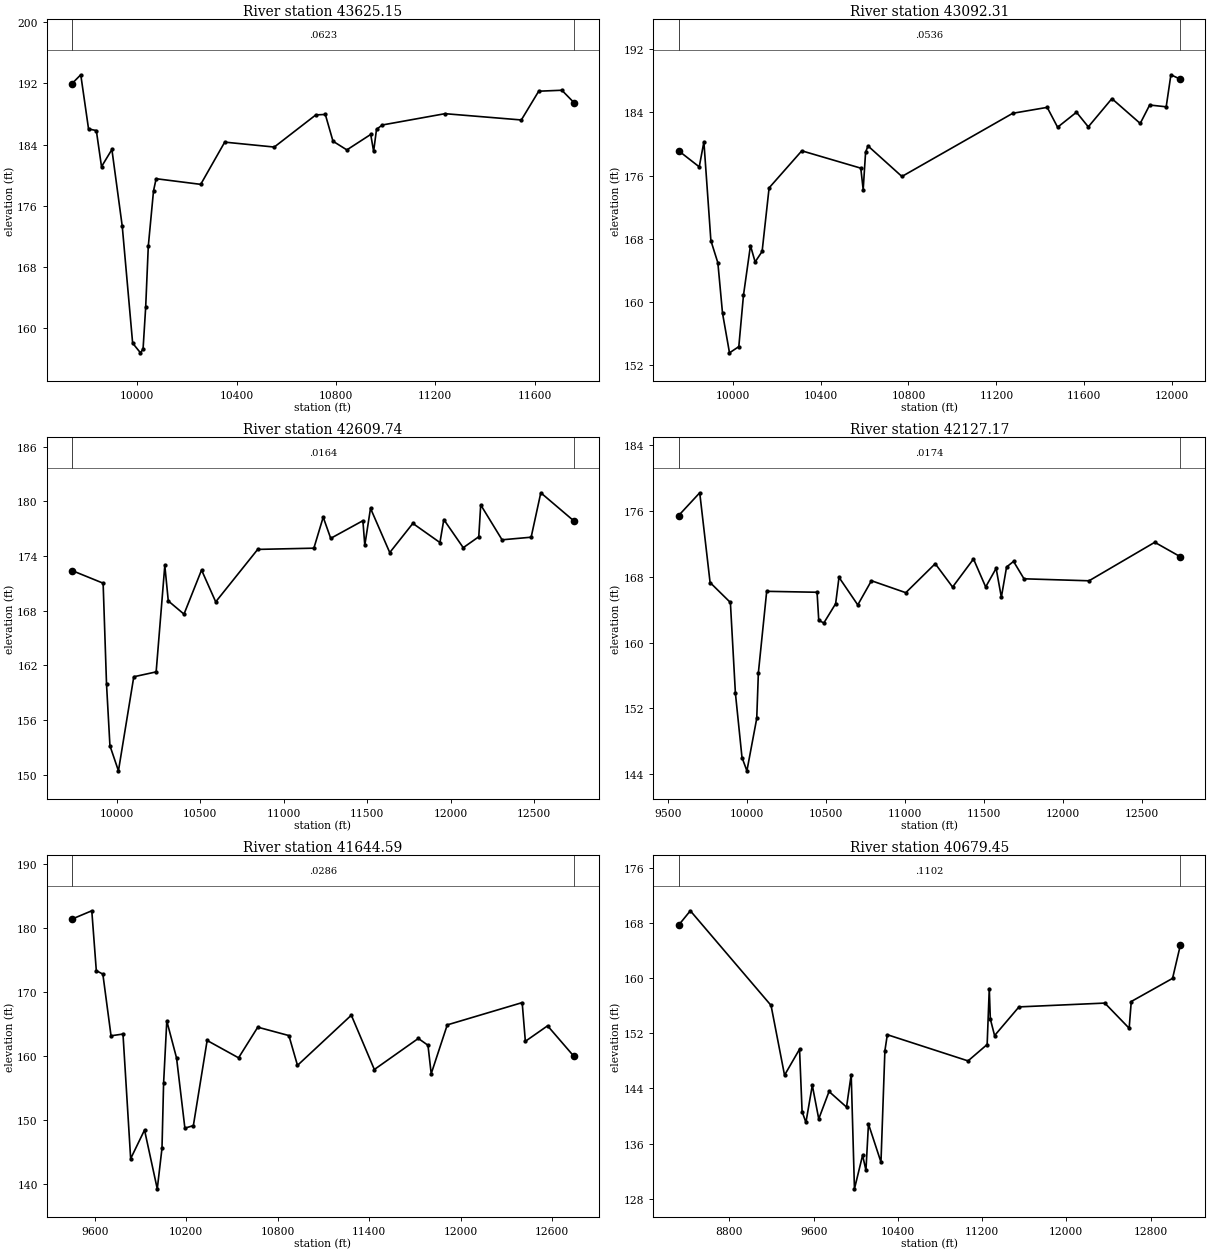
Type RM Length L Ch R = 1 ,43625.15,532.842400,532.842400,532.842400
XS GIS Cut Line= 6
618538.539050847734328.150113463618057.755452424734175.968970746
617843.360784322734082.070190638617717.715388745734009.080828905
617495.728360951733853.364164293616753.621627152733408.035978675
#Sta/Elev= 30
9737.438191.97529772.467193.1212  9803.8186.03829835.134185.82759856.023181.1056
  9897.8183.35319939.578173.29259981.357158.032110012.85156.762210023.35157.2683
10033.85162.731910044.37170.701810065.41177.942110075.93179.530910255.43178.7924
10352.12184.314710551.64183.670310718.84187.870810757.21187.935310788.13184.4351
10843.92183.297610940.07185.318910951.73183.101810963.39185.992310986.72186.5559
11239.21188.034311546.51187.212911616.48190.973911709.78191.098511758.04189.4936
#Mann= 3 , 0 , 0
9737.438  0.0623       09737.438  0.0623       011758.04  0.0623       0
#XS Ineff= 2 , 0
       0                10156.06       0
Bank Sta=9737.438,11758.04
Exp/Cntr=0.3,0.1

Type RM Length L Ch R = 1 ,43092.31,482.572300,482.572300,482.572300
XS GIS Cut Line= 6
618693.986041129733829.472900987618006.470706433733583.625031859
617800.643531054 733494.90698804617667.323692143733429.506961629
617420.216846764733291.198592365616585.107054293732964.143933222
#Sta/Elev= 30
9753.797179.14799848.017177.09989869.193180.27279900.958167.74269932.722164.9232
9953.898158.53079985.663153.496810028.04 154.28610049.24160.807810081.04167.1076
10102.24165.031110134.04 166.36610165.84174.431910314.57179.135910582.95176.9357
10593.87174.214410604.82178.962810615.77179.756110770.12175.878711274.35183.8991
11431.09184.6501 11478.4182.129711564.31184.031911618.01182.175811725.41185.7587
11854.28182.609711897.24184.948511972.42184.720511993.89188.785912036.74188.2235
#Mann= 3 , 0 , 0
9753.797  0.0536       09753.797  0.0536       012036.74  0.0536       0
#XS Ineff= 2 , 0
       0                10259.32       0
Bank Sta=9753.797,12036.74
Exp/Cntr=0.3,0.1

Type RM Length L Ch R = 1 ,42609.74,482.572400,482.572400,482.572400
XS GIS Cut Line= 6
618864.321694029733354.131767682618283.009889191733209.512391429
617986.475388698 733109.57382859617710.415690372732996.512240512
617197.771814768732737.311722326616143.685491886732119.384097459
#Sta/Elev= 30
9731.472172.39369917.588171.00889938.002159.91169958.416153.175110009.43 150.418
10101.32160.740610235.38161.276310287.28172.956410308.05 169.06210402.25167.6136
10507.45172.454410592.35168.960410843.96 174.71811180.58174.851411236.52178.2547
11281.53175.929511474.39 177.86711485.79175.168511520.02 179.22711635.36174.3688
11773.76177.570811936.11175.470211959.38177.989112075.73174.905512168.82176.1042
12180.45179.603512308.44175.770612482.73176.055412540.56180.930812738.71177.8449
#Mann= 3 , 0 , 0
9731.472  0.0164       09731.472  0.0164       012738.71  0.0164       0
#XS Ineff= 2 , 0
       0                10352.37       0
Bank Sta=9731.472,12738.71
Exp/Cntr=0.3,0.1

Type RM Length L Ch R = 1 ,42127.17,482.572400,482.572400,482.572400
XS GIS Cut Line= 6
619156.069570984732992.754230707618888.474777478732874.431444318
618661.015732346732806.665289887618469.573567668732740.467124777
617956.280678552 732540.12712136616233.942541568731759.960923221
#Sta/Elev= 30
9566.365175.42479700.485178.20229765.972167.29979894.436 164.8759926.093 153.869
9967.869146.04499998.936 144.42510061.09150.790410071.53156.344310124.08 166.231
 10442.8166.118710453.47162.7136 10485.5162.383510560.24164.7256 10581.6167.9313
10700.38164.580510786.77167.518611004.12 166.06611190.34169.588511300.24166.7494
11432.46170.161911509.59166.7626 11575.7169.025811608.75165.5147 11641.8169.1874
11685.88 169.86611751.99 167.75312163.42 167.51112579.38172.188112741.05170.4343
#Mann= 3 , 0 , 0
9566.365  0.0174       09566.365  0.0174       012741.05  0.0174       0
#XS Ineff= 2 , 0
       0                10208.92       0
Bank Sta=9566.365,12741.05
Exp/Cntr=0.3,0.1

Type RM Length L Ch R = 1 ,41644.59,965.144800,965.144800,965.144800
XS GIS Cut Line= 6
619343.800398976732692.407965048619014.219501131732414.188998893
618709.219326656732304.026552316 617880.67395322731867.476324958
617229.572325487731615.237995443616369.502372022 731357.00412216
#Sta/Elev= 30
 9451.25181.3337 9580.59182.62679610.182 173.2779653.133172.72939706.817163.0972
 9785.16163.36889835.471143.89599926.415148.374410009.93139.186310040.93145.5286
10051.43155.660410072.45165.413710136.44159.629110191.11148.664810246.68149.0672
10337.01162.364610543.08159.654210669.06164.442710873.14163.131610929.47158.4744
11282.51166.314611433.46157.828211721.79162.681711785.22161.615511806.36157.1654
11911.66164.798412402.96168.280712423.78162.233912569.58164.657712741.87159.8973
#Mann= 3 , 0 , 0
 9451.25  0.0286       0 9451.25  0.0286       012741.87  0.0286       0
#XS Ineff= 2 , 0
       0                10093.27       0
Bank Sta=9451.25,12741.87
Exp/Cntr=0.3,0.1

Type RM Length L Ch R = 1 ,40679.45,739.705000,739.705000,739.705000
XS GIS Cut Line= 6
621176.989815474732859.410536364620672.040757209732614.505063668
620174.258326858732323.442841142619793.775347054732044.460805759
619148.088810682731488.753664866 616861.65471819 731209.43246603
#Sta/Elev= 30
8316.545167.69078428.624169.79319195.234156.05349323.508 145.9229465.904149.6994
9490.162140.63849526.549139.06499587.194144.44889648.457139.5739 9746.22143.5557
9912.368141.28949956.674146.02029987.543129.422310064.84134.292910096.71132.1136
10120.65138.835110239.39133.302110276.71149.472510299.72151.799911066.49 147.998
11248.03150.376311268.17158.504911278.25154.082911318.54151.673711550.24155.8381
12365.47156.392212596.79152.7364 12616.9156.620613009.14159.9792 13082.9164.7858
#Mann= 3 , 0 , 0
8316.545  0.1102       08316.545  0.1102       0 13082.9  0.1102       0
#XS Ineff= 2 , 0
       09873.248        10414.51       0
Bank Sta=8316.545,13082.9
Exp/Cntr=0.3,0.1

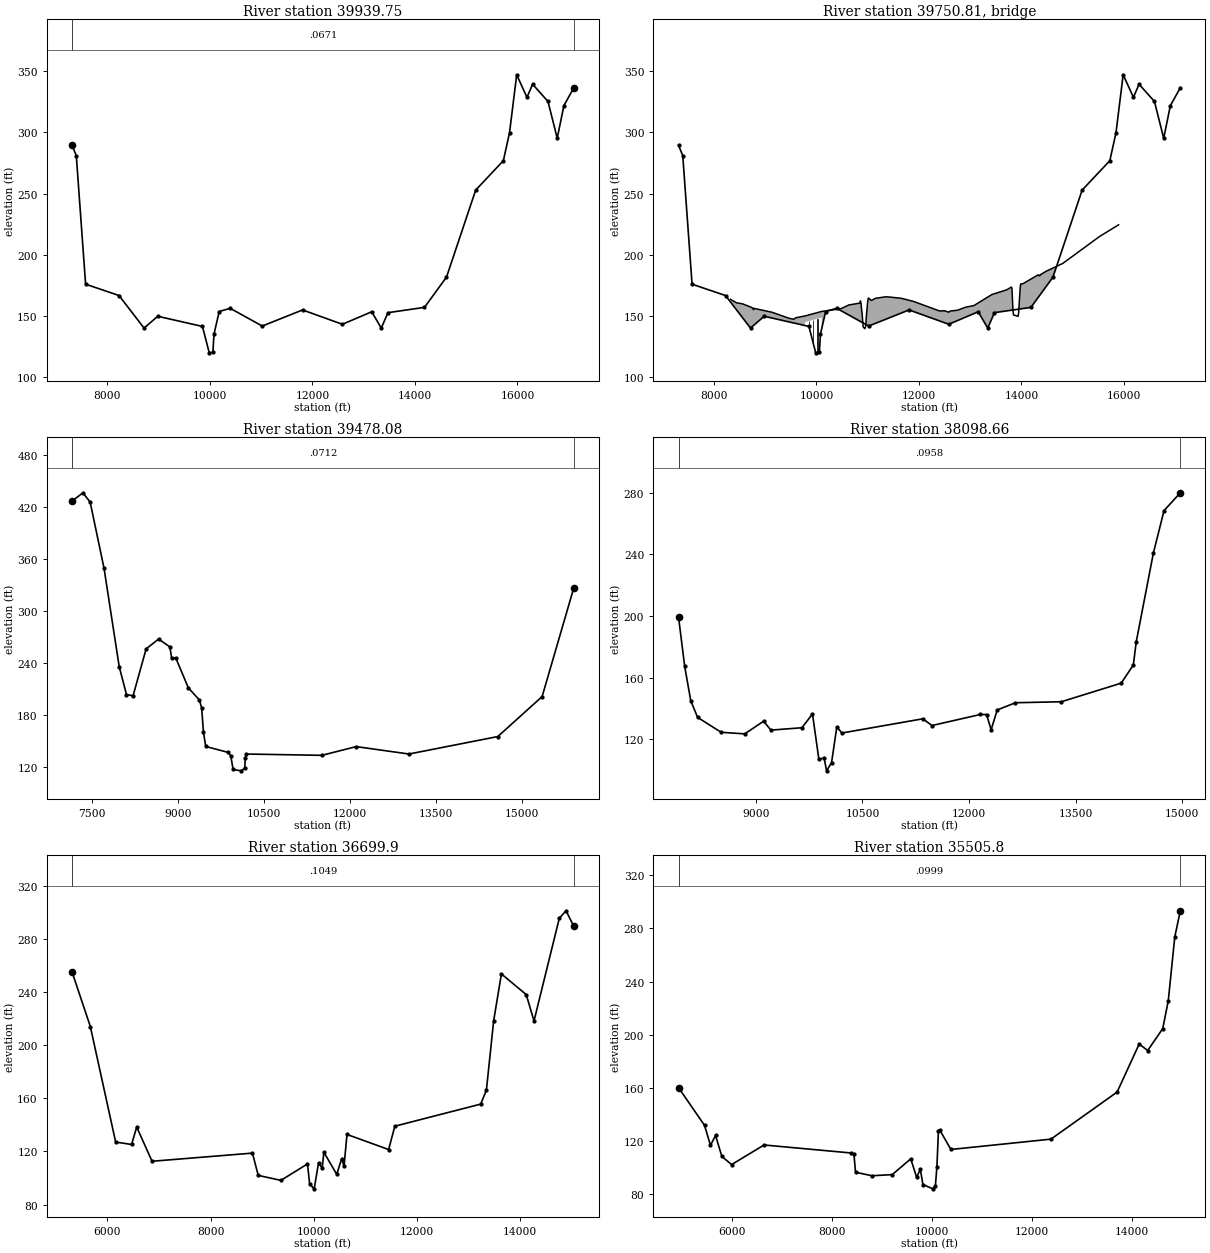
Type RM Length L Ch R = 1 ,39939.75,461.660400,461.660400,461.660400
XS GIS Cut Line= 6
622461.843272924732190.109051108 620375.44673413731384.766947985
619212.420929968731145.498969793617303.329598486 730314.15961571
 616052.90355283729981.015600502613080.665986747730238.018405154
#Sta/Elev= 30
7309.718289.34247391.924281.03457573.789175.88018226.362166.60968714.106140.0203
8982.246149.6539 9853.94141.35139986.604 119.77610058.04120.299310078.45134.9366
 10180.5153.5339 10394.8156.188211020.66141.667411807.59154.827612584.47 143.115
13157.11 153.34413343.39139.9817 13474.4152.603814186.48156.934814616.13181.6355
15185.38 252.77715725.85 276.83615845.96299.648215986.08347.028616186.26328.5824
16296.35339.306516596.62 325.20516776.77295.174716906.89321.785917101.39336.4715
#Mann= 3 , 0 , 0
7309.718  0.0671       07309.718  0.0671       017101.39  0.0671       0
#XS Ineff= 2 , 0
       09723.668        10199.56       0
Bank Sta=7309.718,17101.39
Exp/Cntr=0.3,0.1

Type RM Length L Ch R = 3 ,39750.81,,,
BEGIN DESCRIPTION:
END DESCRIPTION:
Bridge Culvert--1,0,-1,-1, 0
Deck Dist Width WeirC Skew NumUp NumDn MinLoCord MaxHiCord MaxSubmerge Is_Ogee
158.830200,144.000000,2.6,0, 60, 60, , , 0.95, 0, 0,0,,
 8323.79 8439.07 8557.84 8724.11 8759.74 8771.61 8783.49 9136.87 9468.07 9555.05
 9595.66 9775.72 9775.7210103.7210103.7210476.7610631.9110849.4310859.9810870.53
10881.0810891.6310912.7210944.3710954.9210965.4710976.0210997.1211007.6611018.21
11070.9611155.3511365.5011656.1911890.9812405.2712494.7212584.1612606.5212755.64
12911.2013073.4913424.8813715.7413805.3713815.4313835.5413845.5913936.0913946.15
13976.3213986.3714026.5914327.5114357.5414367.5514487.6514807.9115518.5015897.06
  163.49  160.71  159.82  157.12  156.30  155.05  156.11  152.92  147.98  147.21
  148.43  149.89  149.89  153.62  153.62  155.84  158.88  160.44  162.20  160.13
  155.53  152.15  140.92  139.52  140.34  143.04  150.26  160.01  163.93  164.62
  162.54  164.38  165.64  164.36  161.86  153.95  154.22  152.99  153.87  154.63
  157.06  158.41  167.44  171.31  173.58  172.67  154.67  150.78  149.60  152.52
  173.01  176.04  176.18  183.55  182.61  183.55  186.56  192.85  214.67  224.43
 -836.51 -839.29 -840.18 -842.88 -843.70 -844.95 -843.89 -847.08 -852.02 -852.79
 -851.57 -850.11  144.89  148.62 -846.38 -844.16 -841.12 -839.56 -837.80 -839.87
 -844.47 -847.85 -859.08 -860.48 -859.66 -856.96 -849.74 -839.99 -836.07 -835.38
 -837.46 -835.62 -834.36 -835.64 -838.14 -846.05 -845.78 -847.01 -846.13 -845.37
 -842.94 -841.59 -832.56 -828.69 -826.42 -827.33 -845.33 -849.22 -850.40 -847.48
 -826.99 -823.96 -823.82 -816.45 -817.39 -816.45 -813.44 -807.15 -785.33 -775.57
 8323.79 8439.07 8557.84 8724.11 8759.74 8771.61 8783.49 9136.87 9403.10 9555.05
 9595.66 9831.12 9831.1210159.1210159.1210476.7610631.9110849.4310859.9810870.53
10881.0810891.6310912.7210944.3710954.9210965.4710976.0210997.1211007.6611018.21
11070.9611155.3511365.5011656.1911890.9812405.2712494.7212584.1612606.5212755.64
12911.2013073.4913424.8813715.7413805.3713815.4313835.5413845.5913936.0913946.15
13976.3213986.3714026.5914327.5114357.5414367.5514487.6514807.9115518.5015897.06
  163.49  160.71  159.82  157.12  156.30  155.05  156.11  152.92  148.70  147.21
  148.43  150.52  150.52  154.25  154.25  155.84  158.88  160.44  162.20  160.13
  155.53  152.15  140.92  139.52  140.34  143.04  150.26  160.01  163.93  164.62
  162.54  164.38  165.64  164.36  161.86  153.95  154.22  152.99  153.87  154.63
  157.06  158.41  167.44  171.31  173.58  172.67  154.67  150.78  149.60  152.52
  173.01  176.04  176.18  183.55  182.61  183.55  186.56  192.85  214.67  224.43
 -836.51 -839.29 -840.18 -842.88 -843.70 -844.95 -843.89 -847.08 -851.30 -852.79
 -851.57 -849.48  145.52  149.25 -845.75 -844.16 -841.12 -839.56 -837.80 -839.87
 -844.47 -847.85 -859.08 -860.48 -859.66 -856.96 -849.74 -839.99 -836.07 -835.38
 -837.46 -835.62 -834.36 -835.64 -838.14 -846.05 -845.78 -847.01 -846.13 -845.37
 -842.94 -841.59 -832.56 -828.69 -826.42 -827.33 -845.33 -849.22 -850.40 -847.48
 -826.99 -823.96 -823.82 -816.45 -817.39 -816.45 -813.44 -807.15 -785.33 -775.57
Pier Skew, UpSta & Num, DnSta & Num=  ,9856.72, 2 ,9912.12, 2 , 0 , 0 , 0 ,,
    4.00    4.00
 -849.19  150.81
    4.00    4.00
 -848.56  151.44
Pier Skew, UpSta & Num, DnSta & Num=  ,9939.72, 2 ,9995.12, 2 , 0 , 0 , 0 ,,
    4.00    4.00
 -848.25  151.75
    4.00    4.00
 -847.62  152.38
Pier Skew, UpSta & Num, DnSta & Num=  ,10022.72, 2 ,10078.12, 2 , 0 , 0 , 0 ,,
    4.00    4.00
 -847.30  152.70
    4.00    4.00
 -846.68  153.32
BR Coef=-1 , 0 , 0 ,, 0 ,,,0.8,0,1,0,
WSPro=,,,, 1 ,,,, 0 ,,,, 0 ,,,,-1 ,-1 ,-1 , 0 , 0 , 0 , 0 , 0
BC Design=,, 0 ,, 0 ,,,,,,

Type RM Length L Ch R = 1 ,39478.08,1379.426300,1379.426300,1379.426300
XS GIS Cut Line= 6
622783.844821751 731586.11050503620869.241017818730995.657359779
619233.826874167730704.536517456 617208.82454443729736.987835586
616139.860815108 729458.42982614 614403.59309122729287.813922659
#Sta/Elev= 30
7147.829427.11897336.741436.74567463.495 425.9547706.441349.39087970.512235.9125
8097.266203.60728212.785202.14568440.981256.42518658.804267.70528855.882258.6064
    8887245.32988959.607245.74889176.908211.42019369.895197.37289410.524188.1025
9440.996160.31799481.624143.58459867.598136.85279918.384132.96149959.013116.9948
10101.21115.438410162.16118.577610172.31130.437910192.63134.862311510.11133.3633
12107.53143.4394 13029.4134.877714580.35155.053715354.06201.239715908.12327.1496
#Mann= 3 , 0 , 0
7147.829  0.0712       07147.829  0.0712       015908.12  0.0712       0
#XS Ineff= 2 , 0
       09770.338        10231.91       0
Bank Sta=7147.829,15908.12
Exp/Cntr=0.3,0.1

Type RM Length L Ch R = 1 ,38098.66,1398.761200,1398.761200,1398.761200
XS GIS Cut Line= 5
621236.024294138 730004.61735636619761.240397424 729447.28623262
618946.679524273730184.678180933616528.719879776729258.651083037
614736.685958803729087.164583415
#Sta/Elev= 30
7910.928199.33627997.545167.30468083.067145.01498179.279134.23488510.677124.5552
8843.351123.51839109.331131.75519211.096125.95639648.008127.50539797.013136.4265
9886.416107.07689960.919107.88959995.01599.5412510065.22104.827510139.72128.0892
10210.84124.075111348.35 133.289 11480.1128.941812162.18136.129712247.84136.0495
12312.09126.205812397.76139.039912654.76143.730113299.76144.3559 14143.6156.4387
14314.38168.248814354.56183.115514595.66240.690314746.34268.3988 14975.7279.9392
#Mann= 3 , 0 , 0
7910.928  0.0958       07910.928  0.0958       0 14975.7  0.0958       0
#XS Ineff= 2 , 0
       09684.062        10410.58       0
Bank Sta=7910.928,14975.7
Exp/Cntr=0.3,0.1

Type RM Length L Ch R = 1 , 36699.9,1194.098400,1194.098400,1194.098400
XS GIS Cut Line= 6
 622871.41467005729864.073256046620645.528735369728830.191810995
619133.332529627728350.629407317618779.708507131728522.810408074
617993.106800062729146.134983804613724.604708999728818.028499871
#Sta/Elev= 30
 5315.53255.29585669.407214.16836160.584127.05646469.314125.24156568.549138.3947
6866.253112.58928812.478118.73418924.352101.94039364.99998.194849879.122 110.589
9921.95295.3101810009.0991.8046910093.43111.307210165.04107.414310196.44119.4239
10446.33102.738410541.09114.481110587.93  108.94 10645.3132.806511452.37121.4315
11572.72139.021713237.62155.676713347.94166.180313488.35 218.464 13638.8253.7971
14120.21238.203214270.65218.3527 14762.1295.909914892.48301.397215043.32 289.568
#Mann= 3 , 0 , 0
 5315.53  0.1049       0 5315.53  0.1049       015043.32  0.1049       0
#XS Ineff= 2 , 0
       09724.122        10630.08       0
Bank Sta=5315.53,15043.32
Exp/Cntr=0.3,0.1

Type RM Length L Ch R = 1 , 35505.8,1696.918100,1696.918100,1696.918100
XS GIS Cut Line= 6
623005.211092353729438.357366905 619577.06447609728017.673612349
619159.961536295727890.180329954618555.981007231727588.247988205
616395.096268911727589.394837093613354.375579681727799.047632699
#Sta/Elev= 30
4925.963160.17325445.777 131.7815564.849116.7151  5666.1124.16835792.167108.4052
5987.012102.23416636.494117.00118379.271110.97588433.395110.24568465.86996.50177
8793.23493.82451 9200.9694.714149569.906106.56369688.63692.630769762.31598.75185
9812.92587.2383910013.1283.9834610063.1886.2986910093.22100.489210123.25127.2128
10153.29128.046610373.31 113.61812374.16121.3949 13697.4156.833514138.65192.9905
14309.13188.126414609.98204.628314720.29225.497114850.66273.6328 14961.6293.3126
#Mann= 3 , 0 , 0
4925.963  0.0999       04925.963  0.0999       0 14961.6  0.0999       0
#XS Ineff= 2 , 0
       09405.846                       0
Bank Sta=4925.963,14961.6
Exp/Cntr=0.3,0.1

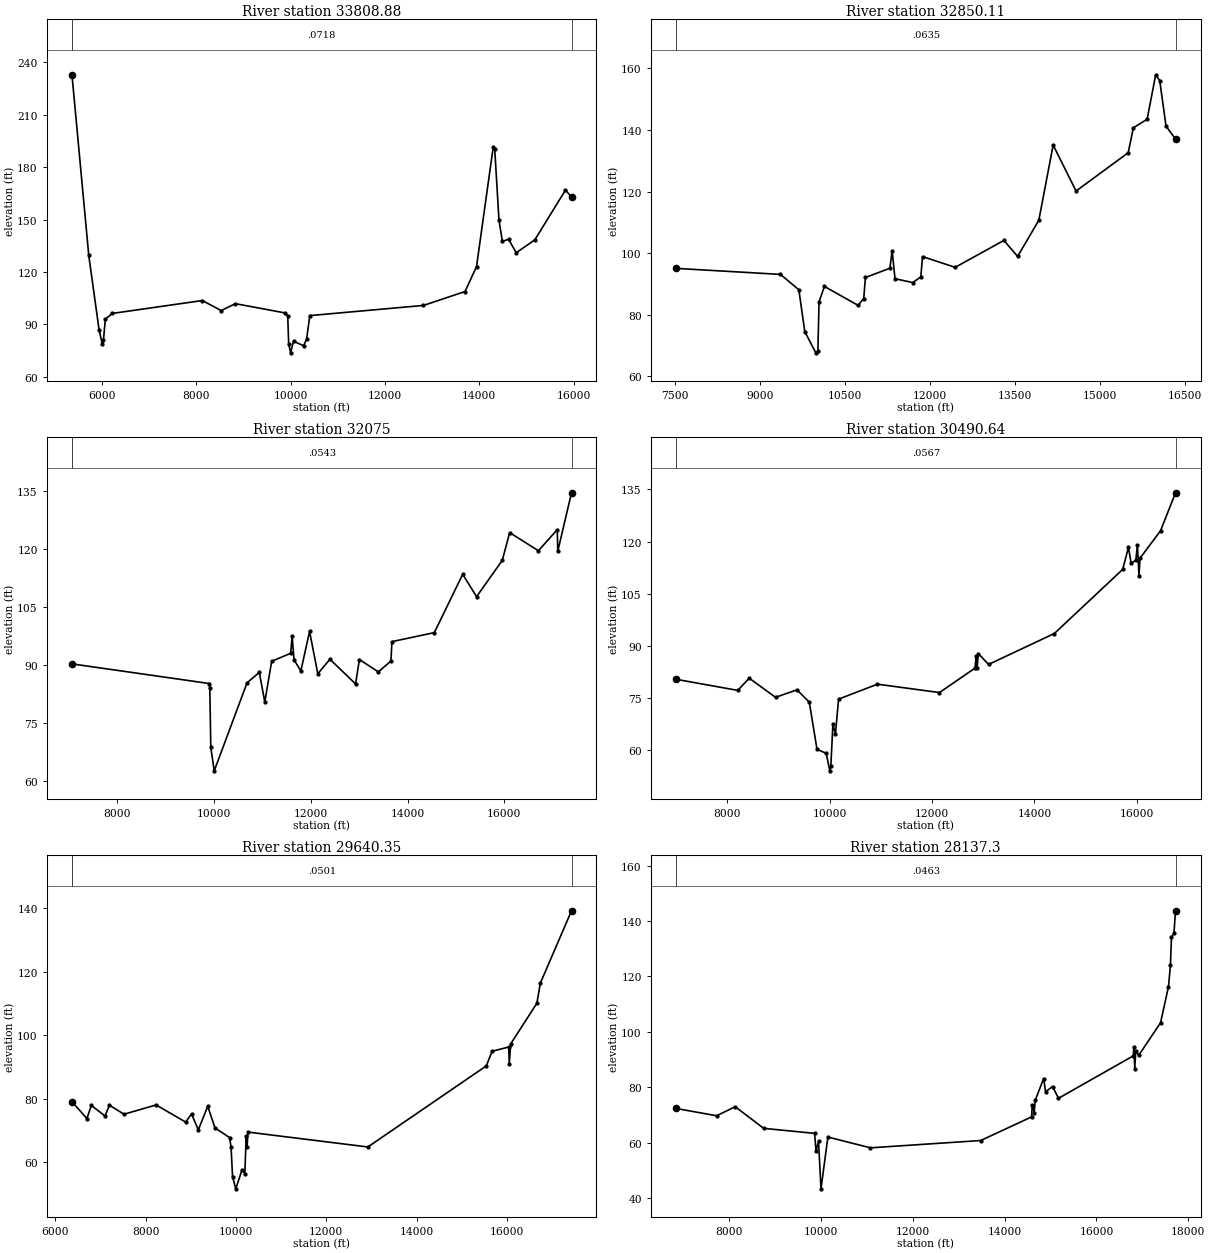
Type RM Length L Ch R = 1 ,33808.88,958.771800,958.771800,958.771800
XS GIS Cut Line= 6
623260.640625834 729049.13141112620523.227964605727003.392951695
619030.472334429726707.388921756618440.139537383726346.810566911
618077.110433048726178.344357147613578.644975603726944.878587633
#Sta/Elev= 30
5361.183232.94515717.776129.4637 5936.0586.922456002.86979.001946029.875 81.0904
6069.68992.983846217.13596.245358127.183103.63428525.30497.877898827.521101.8427
9877.26996.55526 9938.2494.806969958.61978.656369999.39973.6755210060.5480.28965
10275.1677.7381910339.1981.6260510405.9195.0066612816.75100.826613699.29108.8005
13942.75123.0666 14297.8191.696814328.23190.571814419.53149.623614490.54137.4982
14622.41138.725514784.72131.003615180.34138.421515829.56166.907815957.74162.8928
#Mann= 3 , 0 , 0
5361.183  0.0718       05361.183  0.0718       015957.74  0.0718       0
#XS Ineff= 2 , 0
       0                10441.53       0
Bank Sta=5361.183,15957.74
Exp/Cntr=0.3,0.1

Type RM Length L Ch R = 1 ,32850.11,775.104200,775.104200,775.104200
XS GIS Cut Line= 5
621570.422968328726892.137388393620112.787721634726146.171115085
619083.868723959725820.346765801618166.415951073725828.921090811
613038.969612658726617.758989021
#Sta/Elev= 30
7519.19695.01485 9364.0993.061059689.26288.054879794.15674.459499988.61367.55719
10024.9268.01919 10045.984.1554410140.3189.1489410734.7982.9971210834.7985.21734
10864.7992.0530911296.4795.0510911336.94100.700611387.5391.6424911701.1890.41331
11842.8292.2223311873.1898.8517312449.8895.3527913309.88104.107313552.7198.90309
13927.06 110.668   14180135.095614584.71120.160315505.41132.617815596.47140.7264
 15839.3143.475515991.06157.952316061.88156.089516173.18141.271816341.16137.0398
#Mann= 3 , 0 , 0
7519.196  0.0635       07519.196  0.0635       016341.16  0.0635       0
#XS Ineff= 2 , 0
       0                10215.62       0
Bank Sta=7519.196,16341.16
Exp/Cntr=0.3,0.1

Type RM Length L Ch R = 1 ,   32075,1584.360900,1584.360900,1584.360900
XS GIS Cut Line= 6
621990.277784466726751.249883744619819.415609831 725188.68424545
619429.484593882725141.811734033618423.436213527 725463.26556356
615439.174251056725665.876319906612297.937860719726289.923342389
#Sta/Elev= 30
7060.34490.335569900.17385.24296  9910.383.998219930.55468.7656910001.45 62.6239
10679.9285.4271810933.7588.1229511046.5780.4664111189.3391.00923 11582.393.07267
11612.3897.5029211651.56 91.371811792.6988.5176411972.8698.7487312142.9387.75798
12393.0291.54185 12923.385.1456713003.3991.4673313394.1288.2661413655.0291.07401
13675.1296.0950714551.8698.4313115138.37113.549815425.15107.7492   15956117.1341
16109.38124.343816703.72119.646717093.55125.1273 17103.8 119.51817388.03134.6618
#Mann= 3 , 0 , 0
7060.344  0.0543       07060.344  0.0543       017388.03  0.0543       0
#XS Ineff= 2 , 0
       0                10735.72       0
Bank Sta=7060.344,17388.03
Exp/Cntr=0.3,0.1

Type RM Length L Ch R = 1 ,30490.64,850.293000,850.293000,850.293000
XS GIS Cut Line= 5
621313.769899189725202.378218144619641.199847698724114.056094676
618479.245699048          724175615671.287381679 725100.10346745
612130.091164708725923.238665581
#Sta/Elev= 30
7002.753 80.42148208.08177.23688 8432.9680.731558945.97675.241979364.93577.38858
9605.26573.844849755.47260.318139935.71959.1402610005.8254.1193210025.8455.62681
 10065.9 67.473210115.9764.7096410176.7874.7189810934.8579.0133412145.6676.60843
12840.55 83.627512861.6187.0576212882.6783.7995912903.7287.8260113103.7784.68431
14387.4693.5655615722.11111.982615835.05118.322615886.38113.805815978.78114.5635
16009.58119.021616040.38110.126616060.91115.215516461.31  123.0916753.81134.0006
#Mann= 3 , 0 , 0
7002.753  0.0567       07002.753  0.0567       016753.81  0.0567       0
#XS Ineff= 2 , 0
       0                10245.06       0
Bank Sta=7002.753,16753.81
Exp/Cntr=0.3,0.1

Type RM Length L Ch R = 1 ,29640.35,1503.051500,1503.051500,1503.051500
XS GIS Cut Line= 6
621987.555026084725230.848012239619558.132596672723551.130160689
618765.640994221723327.112784207617433.384622782723368.399906263
616250.667343378723602.592712104611819.202935308725267.468427852
#Sta/Elev= 30
6366.31179.037486697.66973.704026794.92977.849647098.86674.517347196.12677.91736
7519.53475.068558229.511 77.99888886.01572.582369014.14875.171319165.63770.13681
 9373.47 77.56739534.85870.723799856.33667.71503 9889.7564.797229923.637 55.3729
9993.92451.5191210135.3957.5906210195.45 56.323810225.4868.1786110245.5164.84015
10265.5569.4232112920.1964.7325715544.8490.3351715670.3394.9258216040.5396.28784
 16051.390.7886716083.6397.2544816664.77110.119616739.85116.411417431.13139.2806
#Mann= 3 , 0 , 0
6366.311  0.0501       06366.311  0.0501       017431.13  0.0501       0
#XS Ineff= 2 , 0
       09322.617        10439.86       0
Bank Sta=6366.311,17431.13
Exp/Cntr=0.3,0.1

Type RM Length L Ch R = 1 , 28137.3,1485.470000,1485.470000,1485.470000
XS GIS Cut Line= 6
621778.776536047724405.223983496620838.311620593723485.810986862
 619692.64579767 722493.50867334619058.145749122722244.853248924
          618095722433.251609504612172.962789714724851.448043019
#Sta/Elev= 30
6833.34172.339557719.662 69.7052 8125.2272.966058745.48865.157469855.01463.33911
9887.23656.834819940.93860.520619994.64143.3088110145.0162.0187911072.3658.12309
13476.6160.7581914585.3869.2913414599.9773.6713414643.1870.8748614664.7475.24675
14848.4183.1503814891.6278.3836415042.8480.2530815172.4676.01993 16803.591.33822
 16814.394.42054 16835.986.71145 16857.593.2246816922.3191.5301217397.58 103.318
17570.41116.368417613.61124.231517635.22134.227917689.22135.595417723.83 143.736
#Mann= 3 , 0 , 0
6833.341  0.0463       06833.341  0.0463       017723.83  0.0463       0
#XS Ineff= 2 , 0
       09487.939        10909.96       0
Bank Sta=6833.341,17723.83
Exp/Cntr=0.3,0.1