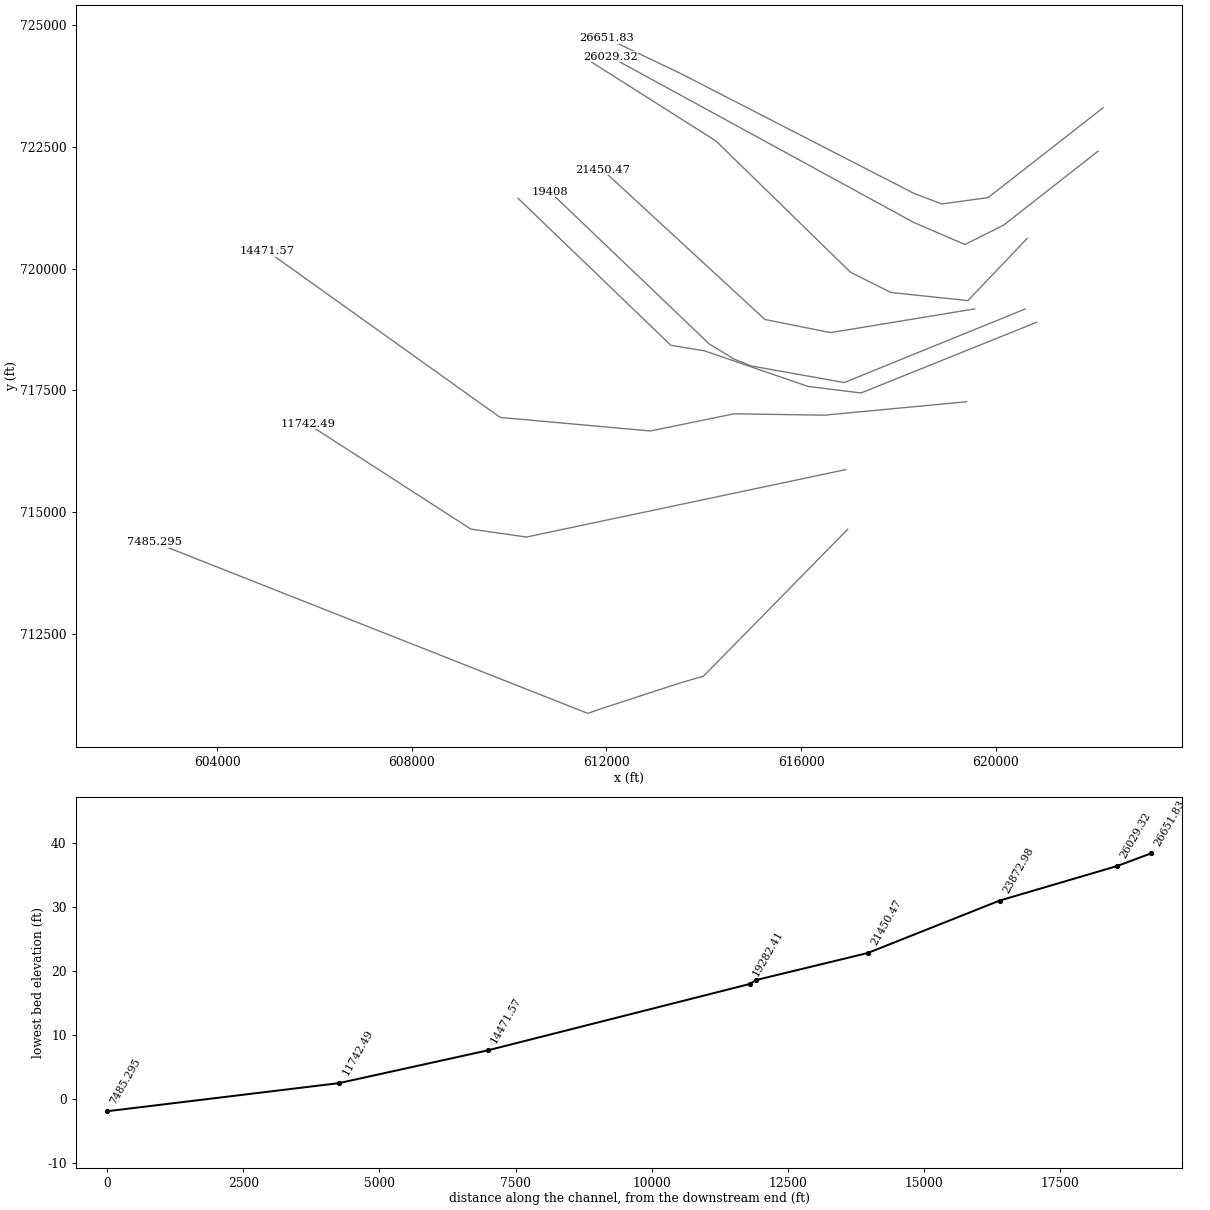
HEC-RAS study 3120_ras.prj: 3120

--- 3120_ras.g01 (geometry) --- (continued)

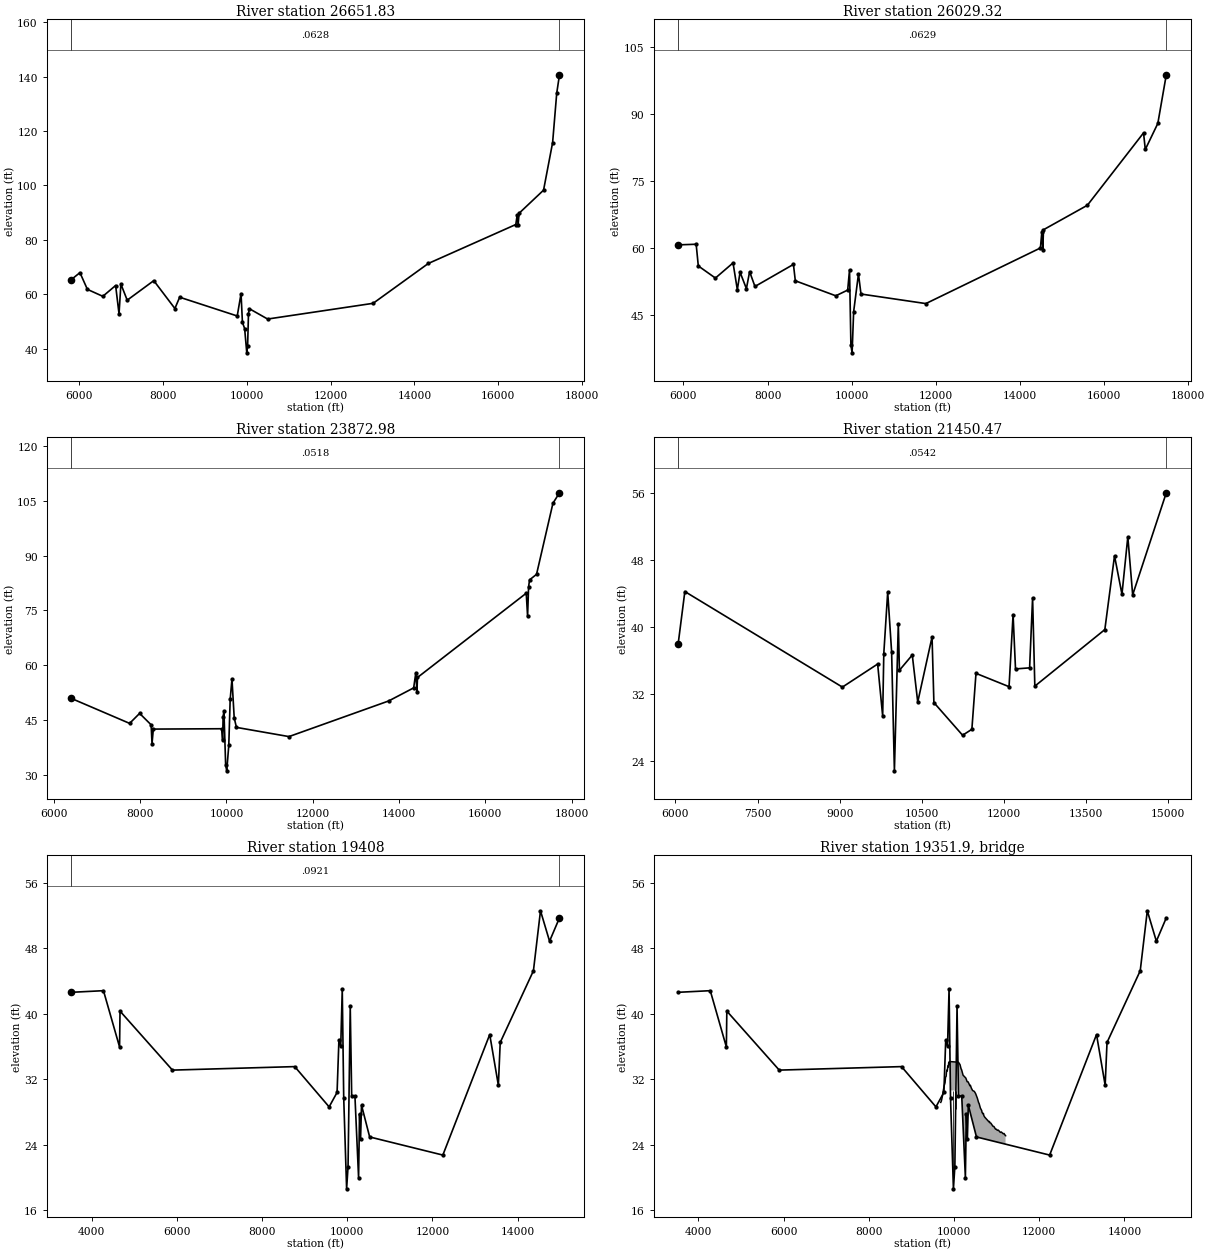
Type RM Length L Ch R = 1 ,26651.83,622.505200,622.505200,622.505200
XS GIS Cut Line= 6
622205.823447466723304.391945168619842.750201643721459.225273222
618894.023681641721329.097047344618332.906923413721539.261335462
613519.671284884724011.856507108612011.595621318724731.904836848
#Sta/Elev= 30
5818.97765.41209 6023.0267.936786200.64461.788436568.57959.227656874.14463.20709
6955.38752.77402 6999.95 63.73917150.36957.807097784.06264.991718287.76654.74588
8401.506 58.89939774.71251.997179865.41760.208399898.53449.686329951.41347.34833
10002.2838.4420210022.5241.0256810042.9252.8880210063.4754.6756410499.3350.87413
13015.8456.6558514332.14 71.311816419.2785.6390616451.2389.0895416474.1485.56149
16497.0589.7785317080.7498.2733817296.82115.767617394.78133.937817460.67140.7117
#Mann= 3 , 0 , 0
5818.977  0.0628       05818.977  0.0628       017460.67  0.0628       0
#XS Ineff= 2 , 0
       09027.752        10954.27       0
Bank Sta=5818.977,17460.67
Exp/Cntr=0.3,0.1

Type RM Length L Ch R = 1 ,26029.32,2156.346600,2156.346600,2156.346600
XS GIS Cut Line= 5
622101.434202462722412.338396862620165.058223128720894.809340283
619366.821448326720495.690952867618312.179475725720950.130176842
612078.645214826724354.137194142
#Sta/Elev= 30
5874.95960.64289  6302.460.78158 6353.2255.922226759.78153.206967179.04756.60099
7281.06250.600957345.90854.514197496.67350.839347572.90354.640787699.95351.32671
8614.70556.267218659.42652.597719621.56949.236479904.67950.516649948.23455.04823
9980.90138.2047410009.2236.4616510046.23 45.687310160.8454.1278310220.4649.63236
11762.8147.4931114485.9459.9446814520.1363.4985614542.91 59.5963 14559.164.02903
15602.5469.5117616937.6985.7175616979.4282.0077917277.4487.8455217478.3898.73362
#Mann= 3 , 0 , 0
5874.959  0.0629       05874.959  0.0629       017478.38  0.0629       0
#XS Ineff= 2 , 0
       09408.556        11525.76       0
Bank Sta=5874.959,17478.38
Exp/Cntr=0.3,0.1

Type RM Length L Ch R = 1 ,23872.98,2422.504800,2422.504800,2422.504800
XS GIS Cut Line= 6
620645.528735369720619.956806064619429.197623521719342.809138611
617847.843182087719508.887260079617015.681474864719925.566799834
614251.870428145722622.153095573611596.917252153724305.593400076
#Sta/Elev= 30
6407.344 50.9002 7756.6144.064987988.47446.801348255.68443.662018275.79438.47098
8305.95942.500819889.31542.597139912.044 39.45849923.40845.889279942.33247.50015
9982.10432.6810310007.31 31.058310054.6238.0309210086.9750.6264110128.64 56.2329
10180.1845.5999810231.78 42.965111449.13  40.444 13759.750.2087414338.8653.79176
14389.4657.9629114414.7652.7353814427.4156.6382416947.8879.73561 16978.973.38382
17002.0281.5204517025.1483.3979117186.2284.9103817566.12104.381117717.94107.2592
#Mann= 3 , 0 , 0
6407.344  0.0518       06407.344  0.0518       017717.94  0.0518       0
#XS Ineff= 2 , 0
       09045.121        11985.25       0
Bank Sta=6407.344,17717.94
Exp/Cntr=0.3,0.1

Type RM Length L Ch R = 1 ,21450.47,2042.477200,2042.477200,2042.477200
XS GIS Cut Line= 4
          619565719171.688364461          616605718684.790078714
615257.261452824718955.000000015 611919.86520794 722030.99889718
#Sta/Elev= 30
6049.26538.047096170.87744.28143 9047.7532.85808 9691.5835.616139783.37129.39467
9803.76936.850319875.16244.218699946.55537.09705 9997.5522.8506910068.9440.43859
10089.3434.8709610323.9236.69314 10423.631.0729810685.0738.8454710718.7131.00863
11242.6527.1049111412.2127.8148711487.4534.5029412090.9532.9091512164.7241.52138
12208.9935.0307312466.6235.1592712521.0143.5334912561.8132.9730613840.1739.73214
14016.9748.5483814152.9643.9575214259.9750.82353 14348.543.8844914962.3256.08471
#Mann= 3 , 0 , 0
6049.265  0.0542       06049.265  0.0542       014962.32  0.0542       0
#XS Ineff= 2 , 0
       07324.636        11802.57       0
Bank Sta=6049.265,14962.32
Exp/Cntr=0.3,0.1

Type RM Length L Ch R = 1 ,   19408,125.584800,125.584800,125.584800
XS GIS Cut Line= 6
620602.766113847 719168.97634685616886.208700329717658.648251206
614975.451014578718000.120352298614624.769400835718140.392997906
614115.613507241718449.978514507 610842.70203504721575.990315512
#Sta/Elev= 30
3524.987 42.61074278.168 42.80814655.965 35.94324666.75940.315365897.295 33.1187
8767.80133.546139575.26328.632969761.86130.397029804.94336.762139848.02436.04042
9883.48842.974669917.88129.705659985.88818.63519 10019.521.34564 10070.940.88769
 10104.929.9917710181.1429.9448210266.76  19.998 10289.227.7794710313.4824.73999
10335.5328.8386110526.7924.9641812244.8922.7535613345.24 37.457613547.93 31.2708
13591.3736.4884414371.0845.2373814537.03 52.555614749.6348.8451814982.7151.69372
#Mann= 3 , 0 , 0
3524.987  0.0921       03524.987  0.0921       014982.71  0.0921       0
#XS Ineff= 2 , 0
       08010.683        10149.94       0
Bank Sta=3524.987,14982.71
Exp/Cntr=0.3,0.1

Type RM Length L Ch R = 3 , 19351.9,,,
BEGIN DESCRIPTION:
END DESCRIPTION:
Bridge Culvert--1,0,-1,-1, 0
Deck Dist Width WeirC Skew NumUp NumDn MinLoCord MaxHiCord MaxSubmerge Is_Ogee
45.792400,34.000000,2.6,0, 60, 60, , , 0.95, 0, 0,0,,
 9688.44 9702.81 9735.34 9746.19 9767.87 9789.56 9800.40 9815.88 9822.09 9832.94
 9841.74 9855.72 9866.19 9876.85 9887.98 9899.10 9928.61 9928.6110091.6110091.61
10105.7710141.5510165.4010177.3310212.6510276.9710309.1210330.5610373.4410384.16
10405.6010436.3510476.9610507.4210548.0210578.3610588.4710618.8110649.1510659.26
10679.4910689.6010699.7210719.9410821.2210831.5010841.7810862.3510913.7710934.33
10975.4710996.1211016.6011039.0111089.1311110.3111152.0811173.0711209.4111209.72
   29.18   29.34   30.14   30.56   31.19   31.58   32.23   32.38   32.85   33.11
   33.03   33.62   33.52   34.09   33.78   34.17   34.15   34.15   34.09   34.09
   34.07   33.78   33.28   33.17   32.50   32.15   31.70   31.69   31.20   31.27
   30.94   30.63   30.52   30.25   29.69   29.14   29.06   28.49   28.19   27.94
   27.79   27.84   27.57   27.39   26.80   26.86   26.69   26.66   26.27   26.25
   25.91   25.91   25.77   25.80   25.52   25.57   25.36   25.39   25.11   25.11
 -970.82 -970.66 -969.86 -969.44 -968.81 -968.42 -967.77 -967.62 -967.15 -966.89
 -966.97 -966.38 -966.48 -965.91 -966.22 -965.83 -965.85   30.65   30.59 -965.91
 -965.93 -966.22 -966.72 -966.83 -967.50 -967.85 -968.30 -968.31 -968.80 -968.73
 -969.06 -969.37 -969.48 -969.75 -970.31 -970.86 -970.94 -971.51 -971.81 -972.06
 -972.21 -972.16 -972.43 -972.61 -973.20 -973.14 -973.31 -973.34 -973.73 -973.75
 -974.09 -974.09 -974.23 -974.20 -974.48 -974.43 -974.64 -974.61 -974.89 -974.89
 9688.44 9702.81 9735.34 9746.19 9767.87 9789.56 9800.40 9815.88 9822.09 9832.94
 9841.74 9855.72 9866.19 9876.85 9887.98 9899.10 9926.55 9926.5510089.5510089.55
10105.7710141.5510165.4010177.3310212.6510276.9710309.1210330.5610373.4410384.16
10405.6010436.3510476.9610507.4210548.0210578.3610588.4710618.8110649.1510659.26
10679.4910689.6010699.7210719.9410821.2210831.5010841.7810862.3510913.7710934.33
10975.4710996.1211016.6011039.0111089.1311110.3111152.0811173.0711209.4111209.72
   29.18   29.34   30.14   30.56   31.19   31.58   32.23   32.38   32.85   33.11
   33.03   33.62   33.52   34.09   33.78   34.17   34.15   34.15   34.09   34.09
   34.07   33.78   33.28   33.17   32.50   32.15   31.70   31.69   31.20   31.27
   30.94   30.63   30.52   30.25   29.69   29.14   29.06   28.49   28.19   27.94
   27.79   27.84   27.57   27.39   26.80   26.86   26.69   26.66   26.27   26.25
   25.91   25.91   25.77   25.80   25.52   25.57   25.36   25.39   25.11   25.11
 -970.82 -970.66 -969.86 -969.44 -968.81 -968.42 -967.77 -967.62 -967.15 -966.89
 -966.97 -966.38 -966.48 -965.91 -966.22 -965.83 -965.85   30.65   30.59 -965.91
 -965.93 -966.22 -966.72 -966.83 -967.50 -967.85 -968.30 -968.31 -968.80 -968.73
 -969.06 -969.37 -969.48 -969.75 -970.31 -970.86 -970.94 -971.51 -971.81 -972.06
 -972.21 -972.16 -972.43 -972.61 -973.20 -973.14 -973.31 -973.34 -973.73 -973.75
 -974.09 -974.09 -974.23 -974.20 -974.48 -974.43 -974.64 -974.61 -974.89 -974.89
Pier Skew, UpSta & Num, DnSta & Num=  ,9982.27, 2 ,9980.21, 2 , 0 , 0 , 0 ,,
    4.00    4.00
 -965.87   34.13
    4.00    4.00
 -965.87   34.13
Pier Skew, UpSta & Num, DnSta & Num=  ,10037.94, 2 ,10035.88, 2 , 0 , 0 , 0 ,,
    4.00    4.00
 -965.89   34.11
    4.00    4.00
 -965.89   34.11
BR Coef=-1 , 0 , 0 ,, 0 ,,,0.8,0,1,0,
WSPro=,,,, 1 ,,,, 0 ,,,, 0 ,,,,-1 ,-1 ,-1 , 0 , 0 , 0 , 0 , 0
BC Design=,, 0 ,, 0 ,,,,,,

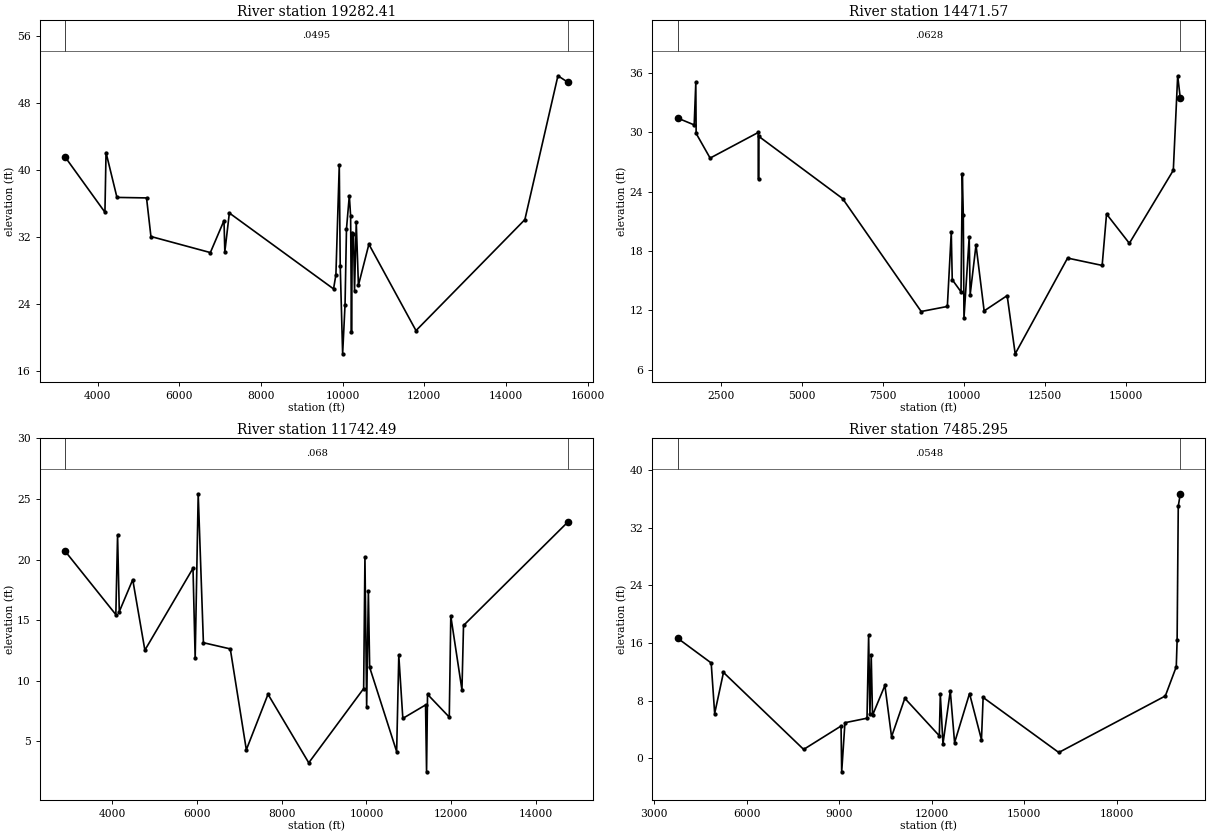
Type RM Length L Ch R = 1 ,19282.41,4810.840800,4810.840800,4810.840800
XS GIS Cut Line= 6
 620841.78490755718898.088380635617233.198891282          717445
616142.128020018717579.743325457614015.468280047718310.765899837
613324.765454352718424.238506898610183.403886229 721445.98786363
#Sta/Elev= 30
3207.61541.510554179.66334.925644206.71642.063114474.15236.699315198.50336.63968
5306.30632.025576761.64630.104697095.83533.929957116.11430.203517226.94934.83473
9778.83325.763259836.60427.453759919.03340.591029942.58428.4914910001.4617.99939
10060.3423.8725310095.6732.95243   1016536.9045410196.8834.4917810218.1320.63414
10239.3832.4956810267.4332.36989 10292.525.54304   1033533.7113810388.13 26.1931
10644.3131.1016611798.0420.77648 14464.334.0425915274.4151.2406615521.0550.45561
#Mann= 3 , 0 , 0
3207.615  0.0495       03207.615  0.0495       015521.05  0.0495       0
#XS Ineff= 2 , 0
       08189.894        10148.26       0
Bank Sta=3207.615,15521.05
Exp/Cntr=0.3,0.1

Type RM Length L Ch R = 1 ,14471.57,2729.076300,2729.076300,2729.076300
XS GIS Cut Line= 6
619398.113051474 717264.11996603616481.218033701716988.568309084
614622.059029549717016.618609622612904.169486612  716663.7548116
609817.453925252716942.106788844605029.735257268720359.538801327
#Sta/Elev= 30
1140.91631.428161656.31430.731521706.53635.026471716.58129.872372148.49527.38021
3635.08429.966813645.12925.270483655.17329.570786243.63823.292558673.13811.88541
9481.34512.395319602.57619.894459632.884 15.09799903.70213.873399944.30925.78408
9974.82921.588369995.17611.2198710156.7919.39566 10186.913.5944710366.9818.59845
10618.5311.9444911330.2513.4903111578.477.60901113197.7417.2815514266.6416.53924
14401.7921.7328515107.0418.7730416465.8626.1481716601.0135.69454 16681.233.43189
#Mann= 3 , 0 , 0
1140.916  0.0628       01140.916  0.0628       0 16681.2  0.0628       0
#XS Ineff= 2 , 0
       07661.966        11500.69       0
Bank Sta=1140.916,16681.2
Exp/Cntr=0.3,0.1

Type RM Length L Ch R = 1 ,11742.49,4257.198800,4257.198800,4257.198800
XS GIS Cut Line= 4
616921.876690775715870.516993672610356.827156991714484.207990199
          609215 714647.63704361605863.273835301716810.657582268
#Sta/Elev= 30
2899.33120.674354091.93915.456254132.82222.027194173.704  15.703 4490.5418.33687
4776.71412.521595911.19219.277685962.29511.853026033.83925.420966156.48513.13756
6790.15712.626087168.3174.3055927679.3438.8845458640.0723.2326429934.2619.354229
9964.56720.1968310004.977.87079510045.3817.4143810075.6911.1064610712.114.157333
10762.6212.0848910857.836.893806 11393.48.005597 11417.22.48701211440.118.878975
11952.776.99974111988.4815.3372712251.579.24702212288.4514.5586714751.6923.10508
#Mann= 3 , 0 , 0
2899.331   0.068       02899.331   0.068       014751.69   0.068       0
#XS Ineff= 2 , 0
       07084.251        11700.82       0
Bank Sta=2899.331,14751.69
Exp/Cntr=0.3,0.1

Type RM Length L Ch R = 1 ,7485.295,0.000000,0.000000,0.000000
XS GIS Cut Line= 6
 616958.24987027714643.490561917613995.001213342711625.539529935
613516.004934102711486.615103617611846.079218447 710941.34758094
611616.571697205710860.937561989602724.160344601714372.665886447
#Sta/Elev= 30
3763.80916.677164854.82913.226154967.4026.1984625252.867 11.90767850.6021.204578
9061.8374.455322 9082.93-1.911949188.393 4.91744 9903.275.5436719955.72717.06902
9997.6926.13858810039.59 14.299610081.56 5.9533210483.0910.1027210698.022.961543
11128.088.30757712246.243.09957212278.498.842039 12364.51.98367812601.049.337746
12740.812.14944513224.638.97724513611.682.55263213665.448.43164216116.790.779442
19568.048.63581219922.8412.6983919950.2116.3534819987.3534.9887920052.7636.74621
#Mann= 3 , 0 , 0
3763.809  0.0548       03763.809  0.0548       020052.76  0.0548       0
#XS Ineff= 2 , 0
       07960.479           14502       0
Bank Sta=3763.809,20052.76
Exp/Cntr=0.3,0.1